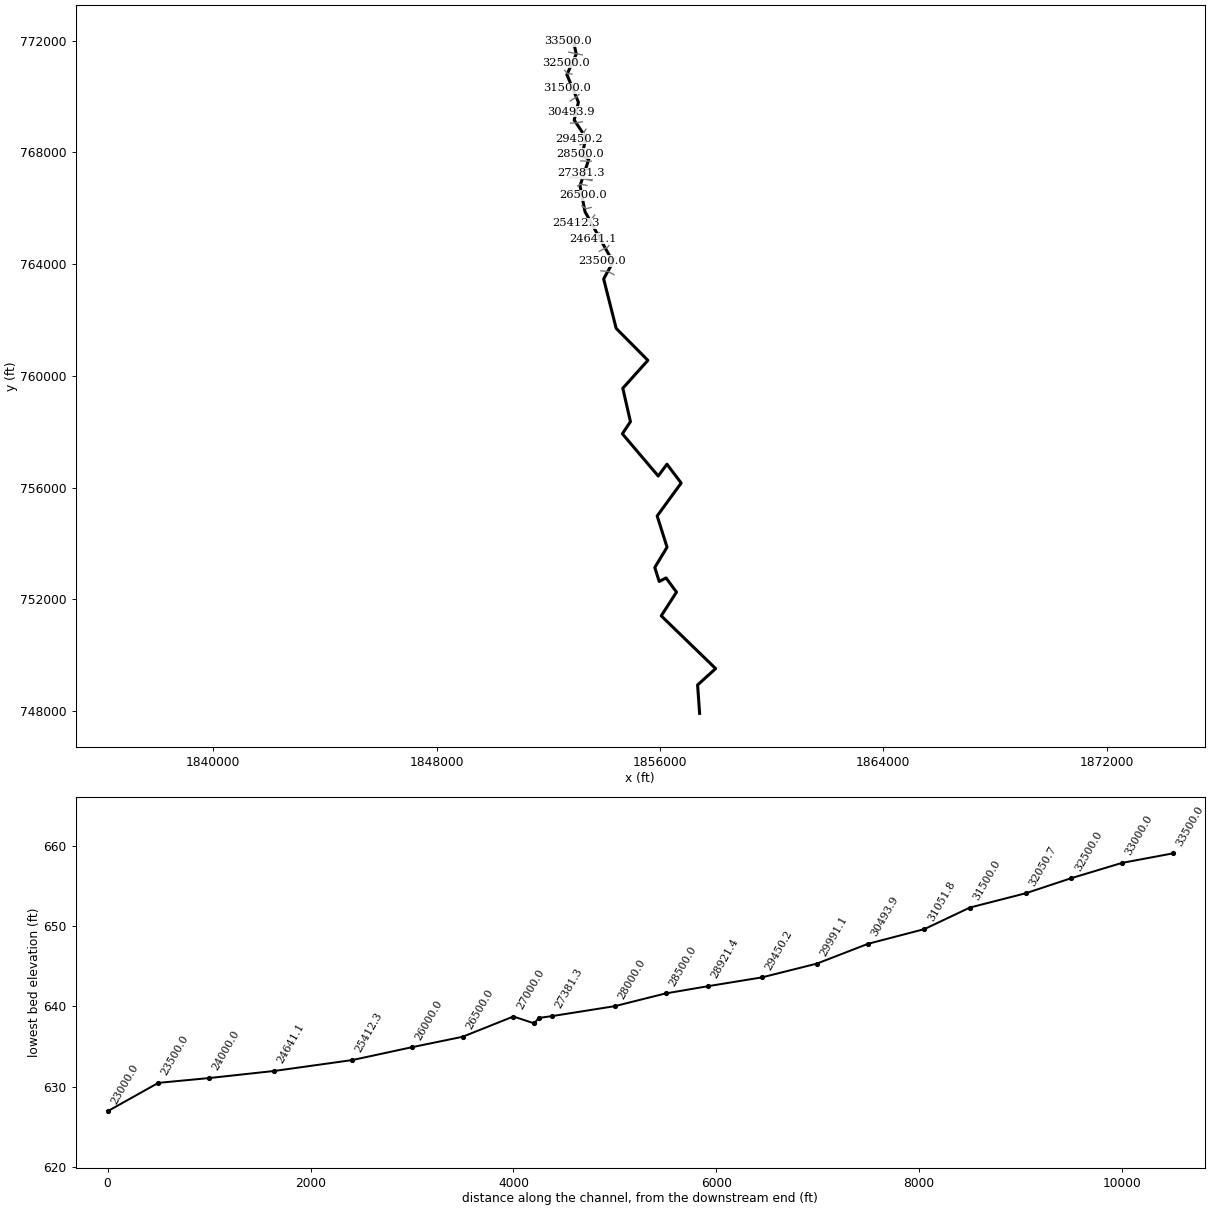
--- GREENBRIAR CREEK.PRJ (project) ---

Proj Title=Greenbriar Creek
Current Plan=p01
Default Exp/Contr=0.3,0.1
English Units
Geom File=g01
Flow File=f01
Plan File=p01
Y Axis Title=Elevation
X Axis Title(PF)=Main Channel Distance
X Axis Title(XS)=Station
BEGIN DESCRIPTION:
####(Watershed Name)####
GREENBRIAR CREEK
HCFCD Unit X###-##-##
(Flood Hazard, Floodway) Model
10, 2, 1, 0.2% Event
Filename:  N:\NC_flood\60273\Approximates\Eng\Rocky_River\Eng\Greenbriar Creek\Greenbriar Creek.prj
Prepared by:  ________     Date: ________
Reviewed by:  ________     Date: ________
STATUS (Draft RAS, SVSQ, FINAL)
END DESCRIPTION:
DSS Export Rating Curves= 0
DSS Export Rating Curve Sorted= 0
DSS Export Volume Flow Curves= 0
DXF OffsetX= 0
DXF OffsetY= 0
DXF ScaleX= 1
DXF ScaleY= 10

--- GREENBRIAR CREEK.p01 (plan) ---

Plan Title=100-Year-Single
Program Version=3.10
Short Identifier=Plan01
Geom File=g01
Flow File=f01
Subcritical Flow
K Sum by GR= 0
Std Step Tol= 0.01
Critical Tol= 0.01
Num of Std Step Trials= 20
Max Error Tol= 0.3
Flow Tol Ratio= 0.001
Split Flow NTrial= 30
Split Flow Tol= 0.02
Split Flow Ratio= 0.02
Log Output Level= 0
Friction Slope Method= 1
Unsteady Friction Slope Method= 2
Parabolic Critical Depth
Global Vel Dist= 0 , 0 , 0
Global Log Level= 0
CheckData=True
Encroach Param=-1 ,0,0, 2
Encroach River=Greenbriar Creek
Encroach Reach=Reach - 1
Encroach Node=33500.0
       1 4935.12 5081.56
Encroach Node=33000.0
       1 4916.18  5155.6
Encroach Node=32500.0
       1  4848.9 5014.71
Encroach Node=32050.7
       1 4919.48 5074.14
Encroach Node=31500.0
       1 4938.44 5057.32
Encroach Node=31051.8
       1  4907.1 5182.82
Encroach Node=30493.9
       1 4987.83 5107.62
Encroach Node=29991.1
       1 4856.31 5060.44
Encroach Node=29450.2
       1 4851.47 5089.94
Encroach Node=28921.4
       1 4954.46 5077.63
Encroach Node=28500.0
       1 4883.95    5015
Encroach Node=28000.0
       1 4985.63 5113.88
Encroach Node=27381.3
       1 4863.98    5020
Encroach Node=27248.2
       1    4969    5029
Encroach Node=27227.7
       1    4969    5029
Encroach Node=27207.2
       1    4969    5029
Encroach Node=27000.0
       1    4900 5051.31
Encroach Node=26500.0
       1    4925  5041.7
Encroach Node=26000.0
       1    4900  5087.1
Encroach Node=25412.3
       1    4920 5234.44
Encroach Node=24641.1
       1    4920 5076.57
Encroach Node=24000.0
       1    4965 5149.68
Encroach Node=23500.0
       1    4950 5226.22
Encroach Node=23000.0
       1 4898.95 5130.83
Encroach Node=22300.2
       1 4963.27 5160.16
Encroach Node=21570.6
       1 4890.55    5030
Encroach Node=20787.7
       1  4894.4 5146.41
Encroach Node=20111.6
       1 4812.39 5120.35
Encroach Node=19731.7
       1  4974.8  5026.8
Encroach Node=19704.7
       1  4974.8  5026.8
Encroach Node=19677.7
       1  4974.8  5026.8
Encroach Node=19447.2
       1 4943.45    5015
Encroach Node=19000.0
       1 4752.61 5042.58
Encroach Node=18500.0
       1 4983.46 5149.36
Encroach Node=18000.0
       1  4916.1 5079.29
Encroach Node=17500.0
       1 4965.24  5157.5
Encroach Node=16845.1
       1    4985  5229.4
Encroach Node=16190.0
       1 4935.66 5073.46
Encroach Node=15500.0
       1    4980 5206.77
Encroach Node=15000.0
       1 4897.38 5087.86
Encroach Node=14500.0
       1    4985 5193.87
Encroach Node=14000.0
       1 4957.87 5015.06
Encroach Node=13400.4
       1 4979.28 5058.45
Encroach Node=12583.6
       1 4937.53 5061.02
Encroach Node=12000.0
       1 4990.44    5012
Encroach Node=11500.0
       1 4983.06 5066.93
Encroach Node=11000.0
       1 4968.59 5017.15
Encroach Node=10500.0
       1 4978.05 5022.81
Encroach Node=10000.0
       1    4970 5016.41
Encroach Node=9500.0
       1    4965    5030
Encroach Node=8987.4
       1    4947    5053
Encroach Node=8964.4
       1    4947    5053
Encroach Node=8941.4
       1    4947    5053
Encroach Node=8317.0
       1    4910    5035
Encroach Node=8000.0
       1    4915    5045
Encroach Node=7604.6
       1    4950 5137.58
Encroach Node=7000.0
       1 4725.05 5042.55
Encroach Node=6475.9
       1    4988 5039.68
Encroach Node=6057.5
       1 4984.37 5085.71
Encroach Node=5500.0
       1 4937.51 5073.19
Encroach Node=5000.0
       1 4943.41 5060.57
Encroach Node=4500.0
       1 4968.95    5061
Encroach Node=4000.0
       1 4967.12 5058.71
Encroach Node=3500.0
       1 4921.41  5036.3
Encroach Node=3090.3
       1 4973.35 5083.46
Encroach Node=2586.4
       1 4919.63 5082.58
Encroach Node=2232.9
       1 4894.51 5322.37
Encroach Node=1500.0
       1 4928.34 5059.76
Encroach Node=1000.0
       1 4939.47 5064.22
Encroach Node=532.9
       1 4885.96 5048.43
Encroach Node=239.0
       1 4717.47 5244.02
Computation Interval=1HOUR
Output Interval=1HOUR
Run HTab= 0
Run UNet= 0
Run PostProcess= 0
UNET Theta= 1
UNET Theta Warmup= 1
UNET ZTol= 0.02
UNET ZSATol= 0.05
UNET MxIter= 20
UNET MaxInSteps= 1
UNET DtIC= 0
UNET DtMin= 0
UNET MaxCRTS= 20
UNET WFStab= 2
UNET SFStab= 1
UNET WFX= 1
UNET SFX= 1
UNET DSS MLevel= 4
UNET Convert EG Bridges=-1
UNET Use Existing IB Tables=-1
UNET Froude Reduction=False
UNET Froude Limit= 1
UNET Froude Power= 10
Instantaneous Interval=1HOUR
Write IC File= 0
Echo Input=False
Echo Output=False
Write Detailed= 0

--- GREENBRIAR CREEK.f01 (steady flow) ---

Flow Title= 100-Year-Single
Program Version=3.10
Number of Profiles= 2
Profile Names=100-Year,FW
River Rch & RM=Greenbriar Creek,Reach - 1       ,33500.0
     737     737
River Rch & RM=Greenbriar Creek,Reach - 1       ,33000
    1278    1278
River Rch & RM=Greenbriar Creek,Reach - 1       ,29450.2
    1583    1583
River Rch & RM=Greenbriar Creek,Reach - 1       ,24000
    1693    1693
River Rch & RM=Greenbriar Creek,Reach - 1       ,20111.6
    2218    2218
River Rch & RM=Greenbriar Creek,Reach - 1       ,14500
    2339    2339
River Rch & RM=Greenbriar Creek,Reach - 1       ,8987.4
    2699    2699
River Rch & RM=Greenbriar Creek,Reach - 1       ,8000
    2878    2878
River Rch & RM=Greenbriar Creek,Reach - 1       ,1500.0
    2951    2951
Boundary for River Rch & Prof#=Greenbriar Creek,Reach - 1       , 1
Up Type= 0
Dn Type= 3
Dn Slope=0.0001
Boundary for River Rch & Prof#=Greenbriar Creek,Reach - 1       , 2
Up Type= 0
Dn Type= 1
Dn Known WS=585.79
DSS Import GetInterval= 0
DSS Import GetPeak= 0
DSS Import FillOption= 0

--- GREENBRIAR CREEK.g01 (geometry) ---

Geom Title=Geom 01 by CodeH2 for Windows

River Reach=Greenbriar Creek,Reach - 1
Reach XY= 30
      1852901.43       771982.58      1853002.12       771514.19
      1852668.12       770779.88      1853080.13       769793.06
      1852929.63       769151.88       1853350.5       768526.81
       1853205.5       767873.06      1853454.38       767760.25
      1853137.37       766800.25      1853314.75       765877.88
       1854319.5       764074.38       1853984.5          763469
       1854432.5       761698.94      1855568.25       760554.75
      1854669.75       759555.56      1854943.62       758360.94
      1854654.88       757926.69      1855937.88       756416.13
         1856251       756837.62         1856761          756164
      1855901.25       754985.69         1856255       753867.44
      1855816.25       753140.94      1855974.25       752641.69
      1856218.13       752768.06      1856593.87       752260.81
      1856046.75       751410.87       1857995.5       749523.37
         1857349       748937.69      1857421.62       747920.44

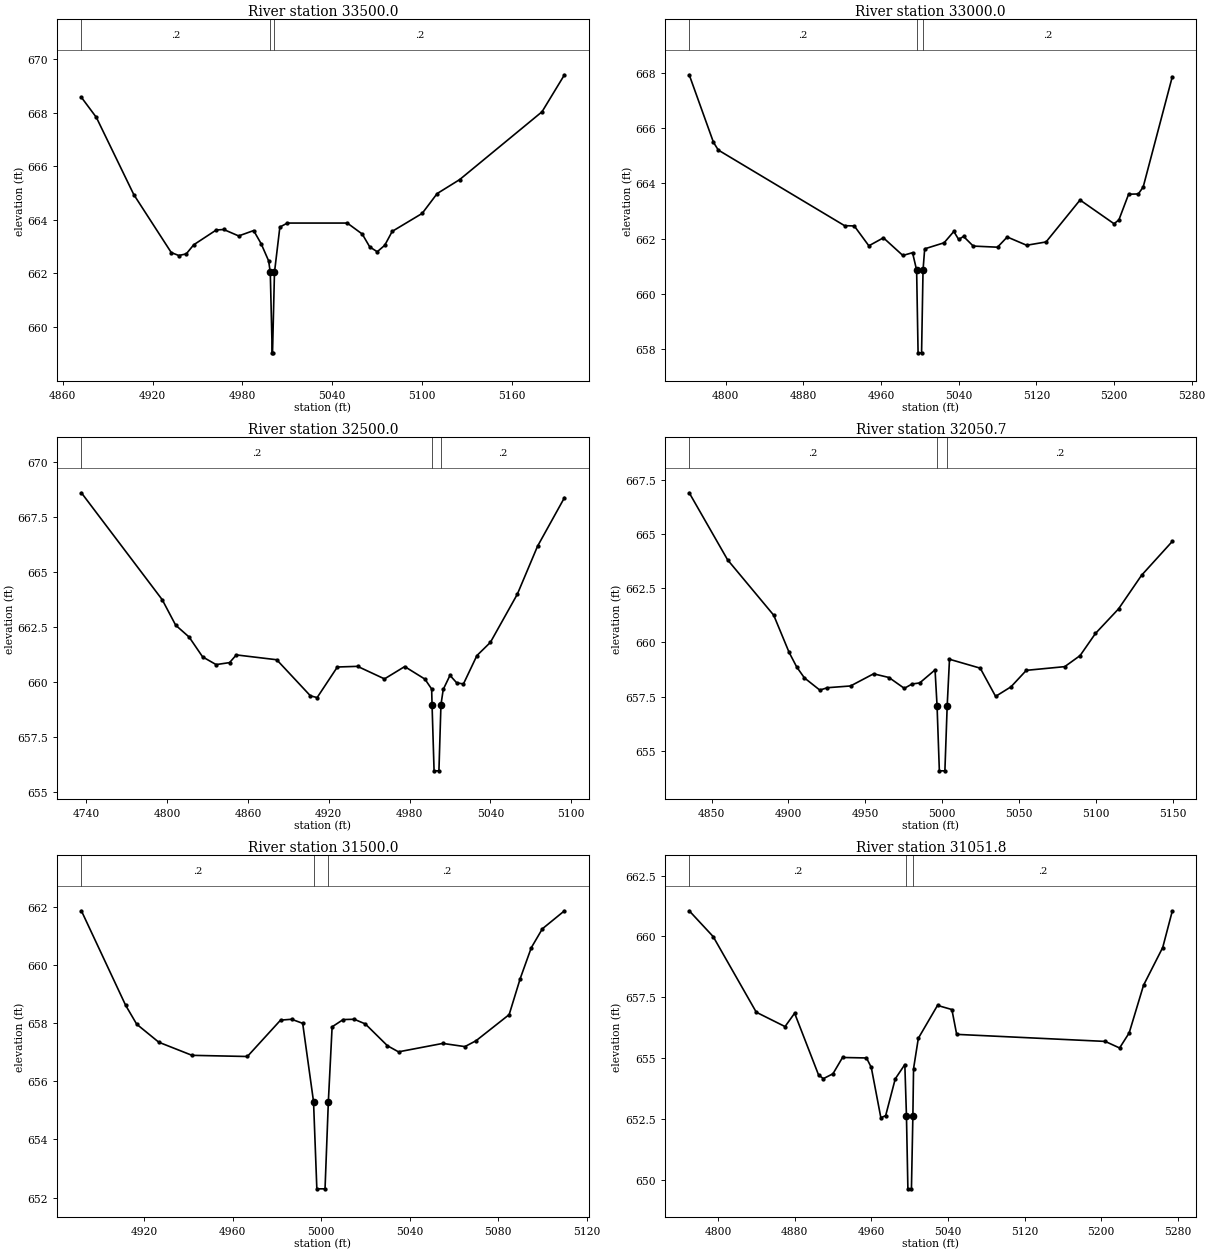
Type RM Length L Ch R = 1 ,33500.0,500,500,500
XS GIS Cut Line= 3
      1852984.57       772079.23      1852901.43       771982.57
      1852706.76       771971.33
BEGIN DESCRIPTION:
Greenbriar Creek 67.0
END DESCRIPTION:
#Sta/Elev= 30
  4872.5  668.57  4882.5  667.82  4907.5  664.94  4932.5  662.78  4937.5  662.67
  4942.5  662.73  4947.5  663.07  4962.5  663.62  4967.5  663.64  4977.5   663.4
  4987.5   663.6  4992.5  663.11  4997.5  662.47  4998.6  662.04  4999.9  659.04
  5000.1  659.04  5001.4  662.04    5005  663.73    5010  663.88    5050  663.88
    5060  663.47    5065  662.99    5070  662.81    5075  663.05    5080  663.57
    5100  664.24    5110  664.98    5125   665.5    5180  668.03    5195  669.41
#Mann= 3 , 1 , 0
 4872.50     0.2       0  4998.6   0.055       0  5001.4     0.2       0
Bank Sta=4998.60,5001.40
Exp/Cntr=0.3,0.1

Type RM Length L Ch R = 1 ,33000.0,500,500,500
XS GIS Cut Line= 3
      1853220.39       771487.50      1852987.26       771532.85
      1852732.82       771586.32
BEGIN DESCRIPTION:
Greenbriar Creek 66.0
END DESCRIPTION:
#Sta/Elev= 30
  4762.5  667.94  4787.5  665.49  4792.5  665.21  4922.5  662.47  4932.5  662.46
  4947.5  661.74  4962.5  662.03  4982.5  661.39  4992.5  661.49  4996.7  660.86
  4998.2  657.86  5001.8  657.86  5003.3  660.86    5005  661.63    5025  661.85
    5035  662.26    5040  661.97    5045  662.08    5055  661.73    5080  661.69
    5090  662.06    5110  661.76    5130  661.88    5165   663.4    5200  662.54
    5205  662.68    5215  663.61    5225  663.62    5230  663.87    5260  667.87
#Mann= 3 , 1 , 0
 4762.50     0.2       0  4996.7   0.055       0  5003.3     0.2       0
Bank Sta=4996.70,5003.30
Exp/Cntr=0.3,0.1

Type RM Length L Ch R = 1 ,32500.0,449.3,449.3,449.3
XS GIS Cut Line= 3
      1852999.67       771156.77      1852738.39       771191.69
      1852645.31       771210.67
BEGIN DESCRIPTION:
Greenbriar Creek 65.0
END DESCRIPTION:
#Sta/Elev= 30
  4736.4   668.6  4796.4  663.74  4806.4  662.58  4816.4  662.04  4826.4  661.14
  4836.4  660.79  4846.4  660.88  4851.4  661.23  4881.4  661.01  4906.4  659.37
  4911.4  659.29  4926.4  660.68  4941.4  660.71  4961.4  660.14  4976.4   660.7
  4991.4  660.13  4996.4  659.68  4996.7  658.96  4998.2  655.96  5001.8  655.96
  5003.3  658.96    5005  659.66    5010   660.3    5015  659.96    5020  659.91
    5030   661.2    5040   661.8    5060  663.99    5075  666.17    5095  668.38
#Mann= 3 , 1 , 0
 4736.40     0.2       0  4996.7   0.055       0  5003.3     0.2       0
Bank Sta=4996.70,5003.30
Exp/Cntr=0.3,0.1

Type RM Length L Ch R = 1 ,32050.7,550.7,550.7,550.7
XS GIS Cut Line= 3
      1852849.33       770799.50      1852685.90       770817.08
      1852590.45       770932.83
BEGIN DESCRIPTION:
Greenbriar Creek 64.0
END DESCRIPTION:
#Sta/Elev= 30
  4835.4  666.89  4860.4   663.8  4890.4  661.25  4900.4  659.54  4905.4  658.86
  4910.4  658.36  4920.4   657.8  4925.4  657.91  4940.4  657.99  4955.4  658.55
  4965.4  658.38  4975.4  657.88  4980.4  658.08  4985.4  658.13  4995.4  658.73
  4996.7  657.08  4998.2  654.08  5001.8  654.08  5003.3  657.08  5004.8  659.22
  5024.8  658.81  5034.8  657.51  5044.8  657.95  5054.8  658.71  5079.8  658.88
  5089.8  659.39  5099.8  660.41  5114.8  661.54  5129.8  663.09  5149.8  664.65
#Mann= 3 , 1 , 0
 4835.40     0.2       0  4996.7   0.055       0  5003.3     0.2       0
Bank Sta=4996.70,5003.30
Exp/Cntr=0.3,0.1

Type RM Length L Ch R = 1 ,31500.0,448.2,448.2,448.2
XS GIS Cut Line= 3
      1852838.83       770398.52      1852779.99       770307.60
      1852672.56       770283.96
BEGIN DESCRIPTION:
Greenbriar Creek 63.0
END DESCRIPTION:
#Sta/Elev= 27
  4891.7  661.86  4911.7  658.61  4916.7  657.96  4926.7  657.34  4941.7  656.89
  4966.7  656.85  4981.7   658.1  4986.7  658.13  4991.7  657.99  4996.6   655.3
  4998.1   652.3  5001.8   652.3  5003.3   655.3    5005  657.87    5010  658.12
    5015  658.13    5020  657.97    5030  657.22    5035  657.01    5055   657.3
    5065  657.19    5070  657.39    5085  658.29    5090  659.53    5095  660.59
    5100  661.24    5110  661.86
#Mann= 3 , 1 , 0
 4891.70     0.2       0  4996.6   0.055       0  5003.3     0.2       0
Bank Sta=4996.60,5003.30
Exp/Cntr=0.3,0.1

Type RM Length L Ch R = 1 ,31051.8,557.9,557.9,557.9
XS GIS Cut Line= 3
      1853176.36       770148.06      1853015.55       769984.95
      1852784.29       769836.06
BEGIN DESCRIPTION:
Greenbriar Creek 62.0
END DESCRIPTION:
#Sta/Elev= 30
    4770  661.05    4795  659.99    4840  656.88    4870  656.29    4880  656.84
    4905   654.3    4910  654.15    4920  654.35    4930  655.02    4955     655
    4960  654.61    4970  652.54    4975  652.63    4985  654.14    4995  654.73
  4996.7  652.62  4998.2  649.62  5001.9  649.62  5003.4  652.62  5004.1  654.56
  5009.1  655.81  5029.1  657.16  5044.1  656.99  5049.1  655.97  5204.1  655.68
  5219.1  655.41  5229.1  656.03  5244.1  657.99  5264.1  659.54  5274.1  661.04
#Mann= 3 , 1 , 0
 4770.00     0.2       0  4996.7   0.055       0  5003.4     0.2       0
Bank Sta=4996.70,5003.40
Exp/Cntr=0.3,0.1

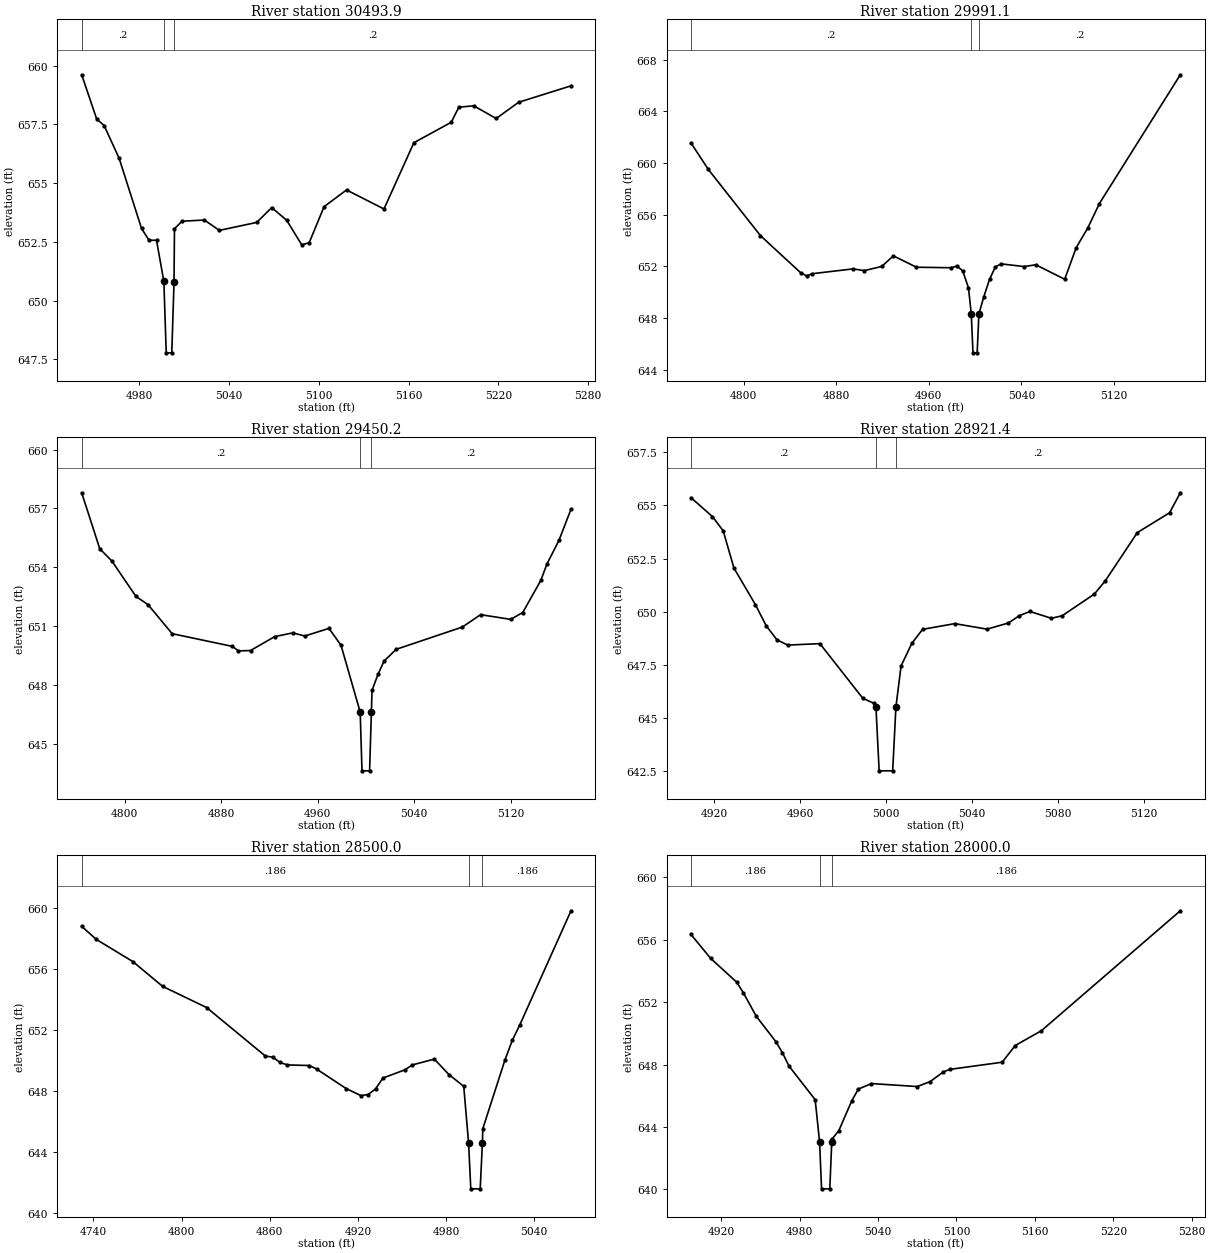
Type RM Length L Ch R = 1 ,30493.9,502.8,502.8,502.8
XS GIS Cut Line= 3
      1853155.42       769458.01      1853093.41       769460.68
      1852828.62       769451.80
BEGIN DESCRIPTION:
Greenbriar Creek 61.0
END DESCRIPTION:
#Sta/Elev= 30
  4941.6  659.61  4951.6  657.73  4956.6  657.45  4966.6  656.06  4981.6  653.07
  4986.6  652.57  4991.6  652.57  4996.5  650.82  4998.1  647.78  5001.8  647.78
  5003.3  650.78  5003.6  653.06  5008.6  653.38  5023.6  653.43  5033.6  652.99
  5058.6  653.33  5068.6  653.96  5078.6  653.42  5088.6  652.38  5093.6  652.46
  5103.6     654  5118.6  654.71  5143.6   653.9  5163.6  656.72  5188.6  657.59
  5193.6  658.23  5203.6  658.29  5218.6  657.75  5233.6  658.44  5268.6  659.14
#Mann= 3 , 1 , 0
 4941.60     0.2       0  4996.5   0.055       0  5003.3     0.2       0
Bank Sta=4996.50,5003.30
Exp/Cntr=0.3,0.1

Type RM Length L Ch R = 1 ,29991.1,540.9,540.9,540.9
XS GIS Cut Line= 3
      1853219.33       769095.75      1852980.55       769049.81
      1852800.52       769046.80
BEGIN DESCRIPTION:
Greenbriar Creek 60.0
END DESCRIPTION:
#Sta/Elev= 30
  4754.3  661.55  4769.3   659.5  4814.3  654.39  4849.3   651.5  4854.3  651.27
  4859.3  651.44  4894.3  651.81  4904.3  651.68  4919.3     652  4929.3  652.82
  4949.3  651.94  4979.3   651.9  4984.3  652.03  4989.3  651.66  4994.3  650.35
  4996.7  648.32  4998.2  645.32  5001.8  645.32  5003.3  648.32  5007.5  649.64
  5012.5     651  5017.5  651.96  5022.5   652.2  5042.5  651.99  5052.5  652.13
  5077.5  651.01  5087.5  653.46  5097.5  654.98  5107.5  656.86  5177.5  666.82
#Mann= 3 , 1 , 0
 4754.30     0.2       0  4996.7   0.055       0  5003.3     0.2       0
Bank Sta=4996.70,5003.30
Exp/Cntr=0.3,0.1

Type RM Length L Ch R = 1 ,29450.2,528.8,528.8,528.8
XS GIS Cut Line= 3
      1853349.10       768827.49      1853216.71       768632.39
      1853118.26       768493.89
BEGIN DESCRIPTION:
Greenbriar Creek 59.0
END DESCRIPTION:
#Sta/Elev= 30
  4764.4   657.8  4779.4  654.94  4789.4  654.32  4809.4  652.51  4819.4  652.09
  4839.4  650.61  4889.4  649.96  4894.4  649.73  4904.4  649.75  4924.4  650.46
  4939.4  650.65  4949.4  650.49  4969.4  650.88  4979.4  650.02  4995.3  646.61
  4996.8  643.61  5003.1  643.61  5004.6  646.61  5005.1  647.71  5010.1  648.54
  5015.1  649.21  5025.1  649.81  5080.1  650.95  5095.1  651.58  5120.1  651.34
  5130.1  651.69  5145.1  653.33  5150.1  654.16  5160.1  655.37  5170.1  656.96
#Mann= 3 , 1 , 0
 4764.40     0.2       0  4995.3   0.055       0  5004.6     0.2       0
Bank Sta=4995.30,5004.60
Exp/Cntr=0.3,0.1

Type RM Length L Ch R = 1 ,28921.4,421.4,421.4,421.4
XS GIS Cut Line= 3
      1853356.61       768325.81      1853269.07       768318.25
      1853138.28       768268.51
BEGIN DESCRIPTION:
Greenbriar Creek 58.0
END DESCRIPTION:
#Sta/Elev= 30
  4909.2  655.36  4919.2  654.47  4924.2   653.8  4929.2  652.05  4939.2  650.33
  4944.2  649.34  4949.2  648.68  4954.2  648.43  4969.2   648.5  4989.2  645.93
  4994.2   645.7  4995.3  645.52  4996.8  642.52  5003.1  642.52  5004.6  645.52
    5007  647.45    5012  648.51    5017  649.17    5032  649.44    5047  649.18
    5057  649.47    5062  649.81    5067  650.01    5077  649.69    5082  649.81
    5097  650.83    5102  651.44    5117  653.72    5132  654.65    5137  655.59
#Mann= 3 , 1 , 0
 4909.20     0.2       0  4995.3   0.055       0  5004.6     0.2       0
Bank Sta=4995.30,5004.60
Exp/Cntr=0.3,0.1

Type RM Length L Ch R = 1 ,28500.0,500,500,500
XS GIS Cut Line= 3
      1853405.15       768116.48      1853194.27       767951.09
      1853129.32       767953.63
BEGIN DESCRIPTION:
Greenbriar Creek 57.0
END DESCRIPTION:
#Sta/Elev= 30
    4732  658.81    4742  657.95    4767  656.49    4787  654.88    4817  653.49
    4857  650.31    4862  650.24    4867  649.89    4872  649.73    4887  649.69
    4892  649.45    4912  648.18    4922  647.72    4927  647.79    4932  648.16
    4937  648.87    4952  649.41    4957  649.73    4972  650.11    4982  649.09
    4992  648.33  4995.3  644.61  4996.8  641.61  5003.2  641.61  5004.7  644.61
    5005  645.56    5020  650.04    5025  651.33    5030  652.32    5065  659.83
#Mann= 3 , 1 , 0
 4732.00   0.186       0  4995.3   0.055       0  5004.7   0.186       0
Bank Sta=4995.30,5004.70
Exp/Cntr=0.3,0.1

Type RM Length L Ch R = 1 ,28000.0,618.7,618.7,618.7
XS GIS Cut Line= 3
      1853541.09       767682.54      1853438.01       767680.38
      1853166.97       767692.58
BEGIN DESCRIPTION:
Greenbriar Creek 56.0
END DESCRIPTION:
#Sta/Elev= 26
  4896.9  656.34  4911.9  654.81  4931.9  653.28  4936.9  652.61  4946.9  651.09
  4961.9  649.46  4966.9  648.75  4971.9   647.9  4991.9  645.75  4995.3  643.03
  4996.8  640.03  5003.1  640.03  5004.6  643.03    5005  643.24    5010  643.76
    5020  645.69    5025  646.43    5035  646.78    5070  646.59    5080  646.91
    5090  647.53    5095  647.69    5135  648.15    5145  649.22    5165  650.17
  5271.3  657.86
#Mann= 3 , 1 , 0
 4896.90   0.186       0  4995.3   0.055       0  5004.6   0.186       0
Bank Sta=4995.30,5004.60
Exp/Cntr=0.3,0.1

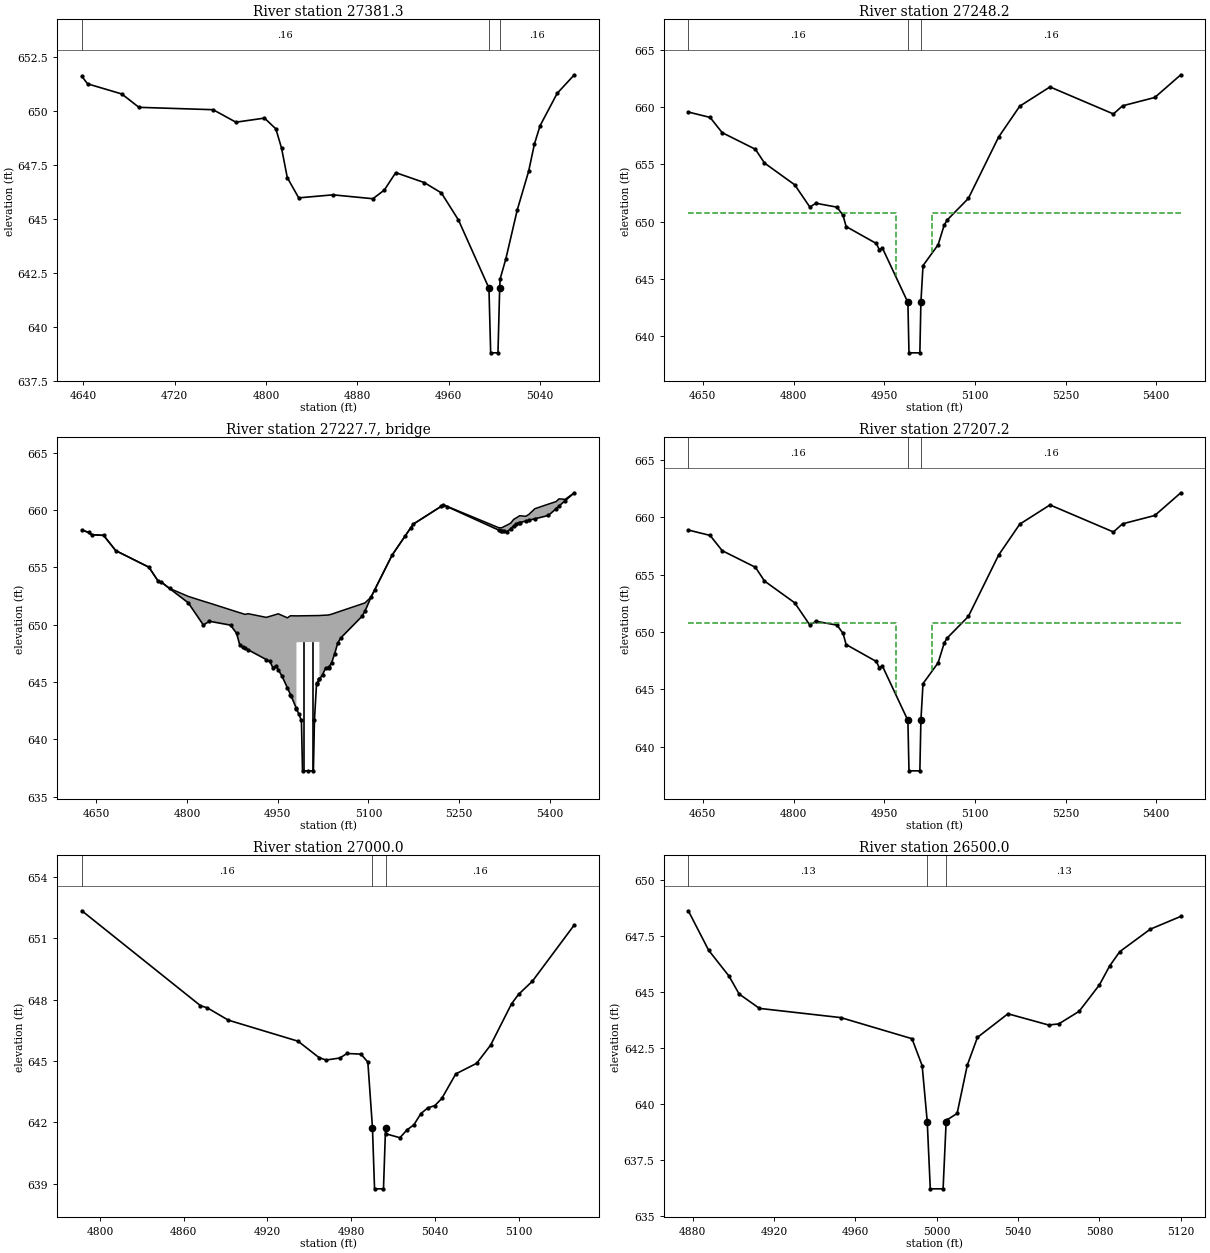
Type RM Length L Ch R = 1 ,27381.3,133.1,133.1,133.1
XS GIS Cut Line= 3
      1853588.40       767228.88      1853221.95       767226.60
      1853160.78       767248.71
BEGIN DESCRIPTION:
Greenbriar Creek 55.0
END DESCRIPTION:
#Sta/Elev= 30
  4638.6  651.62  4643.6  651.27  4673.6   650.8  4688.6  650.18  4753.6  650.07
  4773.6  649.49  4798.6  649.68  4808.6  649.18  4813.6  648.28  4818.6  646.92
  4828.6  645.98  4858.6  646.12  4893.6  645.94  4903.6  646.34  4913.6  647.15
  4938.6  646.69  4953.6  646.21  4968.6  644.95  4995.3  641.79  4996.8  638.79
  5003.2  638.79  5004.7  641.79  5005.1  642.22  5010.1  643.15  5020.1  645.42
  5030.1  647.22  5035.1  648.47  5040.1  649.33  5055.1  650.83  5070.1  651.69
#Mann= 3 , 1 , 0
 4638.60    0.16       0  4995.3   0.055       0  5004.7    0.16       0
Bank Sta=4995.30,5004.70
Exp/Cntr=0.5,0.3

Type RM Length L Ch R = 1 ,27248.2,41,41,41
XS GIS Cut Line= 3
      1853574.05       767025.03      1853212.46       767100.30
      1852767.76       767121.89
BEGIN DESCRIPTION:
Upstream Section of Bridge/Culvert/Weir
END DESCRIPTION:
#Sta/Elev= 30
    4626  659.57    4662   659.1    4682  657.77    4737  656.32    4752  655.12
    4802  653.22    4827  651.28    4837  651.61    4872  651.27    4882  650.55
    4887  649.58    4937   648.1    4942  647.55    4947  647.71  4989.2  642.96
    4991  638.56    5009  638.56  5010.7  642.96  5014.2  646.17  5039.2  647.99
  5049.2   649.7  5054.2  650.15  5089.2  652.03  5139.2  657.38  5174.2  660.08
  5224.2  661.76  5329.2   659.4  5344.2  660.11  5397.6  660.84  5440.6  662.82
#Mann= 3 , 1 , 0
 4626.00    0.16       0  4989.2   0.055       0  5010.7    0.16       0
#XS Ineff= 2 , 0
       0    4969  650.78    5029       0  650.78
Bank Sta=4989.20,5010.70
Exp/Cntr=0.5,0.3

Type RM Length L Ch R = 3 ,27227.7,,,
BEGIN DESCRIPTION:
Staley Store Rd
Structure ID: NCF-0032
Approximate Survey Structure
END DESCRIPTION:
Bridge Culvert--1,0,-1,-1, 0
Deck Dist Width WeirC Skew NumUp NumDn MinLoCord MaxHiCord MaxSubmerge Is_Ogee
10,21,2.6,, 58, 58,,,0.95,0,1,1,,
    4626    4637    4642    4662    4682    4737    4752    4757    4771    4802
    4827    4837    4872    4882    4887    4896    4901    4931    4937    4942
    4947    4951    4957    4966    4971 4980.91    4981 5018.89    5019  5024.2
  5029.2  5034.2  5039.2  5044.2  5049.2  5054.2  5089.2  5094.2  5104.2  5139.2
  5174.2  5224.2  5315.3  5320.3  5324.2  5329.2  5335.3  5340.3  5344.2  5350.3
  5360.3  5365.3  5375.3  5397.6  5410.3  5415.3  5425.3  5440.6
  658.26  658.06  657.86   657.8  656.47  655.02  653.82  653.74  653.17  652.47
  652.05  651.89   651.3  651.13  651.05   650.9  650.96  650.64  650.73  650.81
  650.89  650.95  650.81   650.6  650.78  650.77  650.77   650.8   650.8  650.82
  650.83  650.85  650.92  651.01   651.1  651.19  651.81   651.9   652.4  656.08
  658.78  660.46  658.47  658.45  658.56  658.69  658.86  659.19  659.31  659.51
  659.46  659.62  660.12  660.52  660.74  660.98  660.94  661.51
  658.26  658.05  657.85  657.79  656.46  655.01  653.81  653.73  653.16  651.91
  649.97   650.3  649.96  649.24  648.27  647.95  647.81  646.96  646.79  646.24
   646.4  646.05  645.52  644.49  643.91  642.69  648.47   648.5  645.23  645.64
  646.22  646.26  646.68  647.47  648.39  648.84  650.72  651.16  652.39  656.07
  658.77  660.45  658.26  658.18   658.2  658.09  658.38  658.62   658.8  658.91
  659.04  659.11  659.24  659.53  660.11  660.35  660.81  661.51
    4626    4637    4642    4662    4682    4737    4752    4757    4771    4802
    4827    4837    4872    4882    4887    4896    4901    4931    4937    4942
    4947    4951    4957    4966    4971 4980.91    4981 5018.89    5019  5024.2
  5029.2  5034.2  5039.2  5044.2  5049.2  5054.2  5089.2  5094.2  5104.2  5139.2
  5174.2  5224.2  5315.3  5320.3  5324.2  5329.2  5335.3  5340.3  5344.2  5350.3
  5360.3  5365.3  5375.3  5397.6  5410.3  5415.3  5425.3  5440.6
  658.26  658.06  657.86   657.8  656.47  655.02  653.82  653.74  653.17  652.47
  652.05  651.89   651.3  651.13  651.05   650.9  650.96  650.64  650.73  650.81
  650.89  650.95  650.81   650.6  650.78  650.77  650.77   650.8   650.8  650.82
  650.83  650.85  650.92  651.01   651.1  651.19  651.81   651.9   652.4  656.08
  658.78  660.46  658.47  658.45  658.56  658.69  658.86  659.19  659.31  659.51
  659.46  659.62  660.12  660.52  660.74  660.98  660.94  661.51
  658.01   657.8   657.6  657.54  656.21  654.76  653.56  653.48  652.91  651.66
  649.72  650.05  649.71  648.99  648.02   647.7  647.56  646.71  646.54  645.99
  646.15   645.8  645.27  644.24  643.66  642.44  648.22  648.25  644.98  645.39
  645.97  646.01  646.43  647.22  648.14  648.59  650.47  650.91  652.14  655.82
  658.52   660.2  658.01  657.93  657.95  657.84  658.13  658.37  658.55  658.66
  658.79  658.86  658.99  659.28  659.86   660.1  660.56  661.26
Pier Skew, UpSta & Num, DnSta & Num=,4992.5, 2 ,4992.5, 2 , 0 , 0 , 0 ,,
       1       1
  636.25  649.46
       1       1
     636  649.21
Pier Skew, UpSta & Num, DnSta & Num=,5007.5, 2 ,5007.5, 2 , 0 , 0 , 0 ,,
       1       1
  636.25  649.48
       1       1
     636  649.23
Abutment Skew #Up #Dn=, 2 , 2
 4980.80 4985.00
  648.47  642.18
 4980.80 4985.00
  648.22  641.93
Abutment Skew #Up #Dn=, 2 , 2
 5015.00 5019.09
  644.92  648.50
 5015.00 5019.09
  644.67  648.25
BR Coef= 1 , 1 , 0 ,1.25, 0 ,,,0.8,0,2,0,
Wspro=,,,, 1 ,,,, 0 ,,,, 0 ,,,,-1 ,-1 ,-1 , 0 , 0 , 0 , 0 , 0
BC Design=,, 0 ,, 0 ,,,,,,
BR U #Sta/Elev= 76
    4626  658.26    4637  658.05    4642  657.85    4662  657.79    4682  656.46
    4737  655.01    4752  653.81    4757  653.73    4771  653.16    4802  651.91
    4827  649.97    4837   650.3    4872  649.96    4882  649.24    4887  648.27
    4892  648.06    4896  647.95    4901  647.81    4931  646.96    4937  646.79
    4942  646.24    4947   646.4    4951  646.05    4957  645.52    4966  644.49
    4971  643.91    4972   643.8 4980.91  642.69    4981  642.68    4985  642.18
  4989.2  641.65    4991  637.25    5000  637.25    5009  637.25  5010.7  641.65
  5014.2  644.86    5015  644.92 5018.89  645.23    5019  645.23  5024.2  645.64
  5029.2  646.22  5034.2  646.26  5035.3  646.35  5039.2  646.68  5044.2  647.47
  5049.2  648.39  5054.2  648.84  5089.2  650.72  5094.2  651.16  5104.2  652.39
  5110.3  653.03  5139.2  656.07  5160.3   657.7  5170.3  658.47  5174.2  658.77
  5220.3  660.32  5224.2  660.45  5230.3   660.3  5315.3  658.26  5319.2  658.17
  5320.3  658.18  5324.2   658.2  5329.2  658.09  5335.3  658.38  5340.3  658.62
  5344.2   658.8  5349.2   658.9  5350.3  658.91  5360.3  659.04  5365.3  659.11
  5375.3  659.24  5397.6  659.53  5410.3  660.11  5415.3  660.35  5425.3  660.81
  5440.6  661.51
BR U #Mann= 3
 4626.00    0.16  4989.2   0.055  5010.7    0.16
BR U Banks=4989.20,5010.70
BR D #Sta/Elev= 76
    4626  658.01    4637   657.8    4642   657.6    4662  657.54    4682  656.21
    4737  654.76    4752  653.56    4757  653.48    4771  652.91    4802  651.66
    4827  649.72    4837  650.05    4872  649.71    4882  648.99    4887  648.02
    4892  647.81    4896   647.7    4901  647.56    4931  646.71    4937  646.54
    4942  645.99    4947  646.15    4951   645.8    4957  645.27    4966  644.24
    4971  643.66    4972  643.55 4980.91  642.44    4981  642.43    4985  641.93
  4989.2   641.4    4991     637    5000     637    5009     637  5010.7   641.4
  5014.2  644.61    5015  644.67 5018.89  644.98    5019  644.98  5024.2  645.39
  5029.2  645.97  5034.2  646.01  5035.3   646.1  5039.2  646.43  5044.2  647.22
  5049.2  648.14  5054.2  648.59  5089.2  650.47  5094.2  650.91  5104.2  652.14
  5110.3  652.78  5139.2  655.82  5160.3  657.45  5170.3  658.22  5174.2  658.52
  5220.3  660.07  5224.2   660.2  5230.3  660.05  5315.3  658.01  5319.2  657.92
  5320.3  657.93  5324.2  657.95  5329.2  657.84  5335.3  658.13  5340.3  658.37
  5344.2  658.55  5349.2  658.65  5350.3  658.66  5360.3  658.79  5365.3  658.86
  5375.3  658.99  5397.6  659.28  5410.3  659.86  5415.3   660.1  5425.3  660.56
  5440.6  661.26
BR D #Mann= 3
 4626.00    0.16  4989.2   0.055  5010.7    0.16
BR D Banks=4989.20,5010.70

Type RM Length L Ch R = 1 ,27207.2,207.2,207.2,207.2
XS GIS Cut Line= 3
      1853555.71       766988.37      1853194.12       767063.64
      1852749.42       767085.23
BEGIN DESCRIPTION:
Downstream Section of Bridge/Culvert/Weir
END DESCRIPTION:
#Sta/Elev= 30
    4626  658.89    4662  658.42    4682  657.09    4737  655.64    4752  654.44
    4802  652.54    4827   650.6    4837  650.93    4872  650.59    4882  649.87
    4887   648.9    4937  647.42    4942  646.87    4947  647.03  4989.2  642.28
    4991  637.88    5009  637.88  5010.7  642.28  5014.2  645.49  5039.2  647.31
  5049.2  649.02  5054.2  649.47  5089.2  651.35  5139.2   656.7  5174.2   659.4
  5224.2  661.08  5329.2  658.72  5344.2  659.43  5397.6  660.16  5440.6  662.14
#Mann= 3 , 1 , 0
 4626.00    0.16       0  4989.2   0.055       0  5010.7    0.16       0
#XS Ineff= 2 , 0
       0    4969  650.78    5029       0  650.78
Bank Sta=4989.20,5010.70
Exp/Cntr=0.5,0.3

Type RM Length L Ch R = 1 ,27000.0,500,500,500
XS GIS Cut Line= 3
      1853382.06       766814.36      1853173.71       766858.64
      1853047.45       766798.15
BEGIN DESCRIPTION:
Greenbriar Creek 54.0
END DESCRIPTION:
#Sta/Elev= 30
    4787  652.34    4872   647.7    4877  647.59    4892  646.99    4942  645.96
    4957  645.16    4962  645.04    4972  645.14    4977  645.36    4987  645.33
    4992  644.94  4995.3  641.74  4996.8  638.74  5003.2  638.74  5004.7  641.74
    5005  641.43    5015  641.24    5020  641.62    5025  641.87    5030  642.42
    5035   642.7    5040  642.81    5045  643.16    5055  644.36    5070  644.88
    5080  645.77    5095  647.79    5100  648.25    5110   648.9    5140  651.65
#Mann= 3 , 1 , 0
 4787.00    0.16       0  4995.3   0.055       0  5004.7    0.16       0
Bank Sta=4995.30,5004.70
Exp/Cntr=0.3,0.1

Type RM Length L Ch R = 1 ,26500.0,500,500,500
XS GIS Cut Line= 3
      1853450.80       766527.16      1853351.19       766456.39
      1853231.19       766455.20
BEGIN DESCRIPTION:
Greenbriar Creek 53.0
END DESCRIPTION:
#Sta/Elev= 25
  4877.8  648.61  4887.8  646.85  4897.8   645.7  4902.8   644.9  4912.8  644.26
  4952.8  643.85  4987.8  642.91  4992.8  641.71  4995.3  639.22  4996.8  636.22
  5003.1  636.22  5004.6  639.22    5005  639.29    5010  639.58    5015  641.73
    5020  642.97    5035  644.02    5055  643.52    5060  643.57    5070  644.13
    5080  645.31    5085  646.15    5090  646.79    5105  647.79    5120  648.36
#Mann= 3 , 1 , 0
 4877.80    0.13       0  4995.3    0.05       0  5004.6    0.13       0
Bank Sta=4995.30,5004.60
Exp/Cntr=0.3,0.1

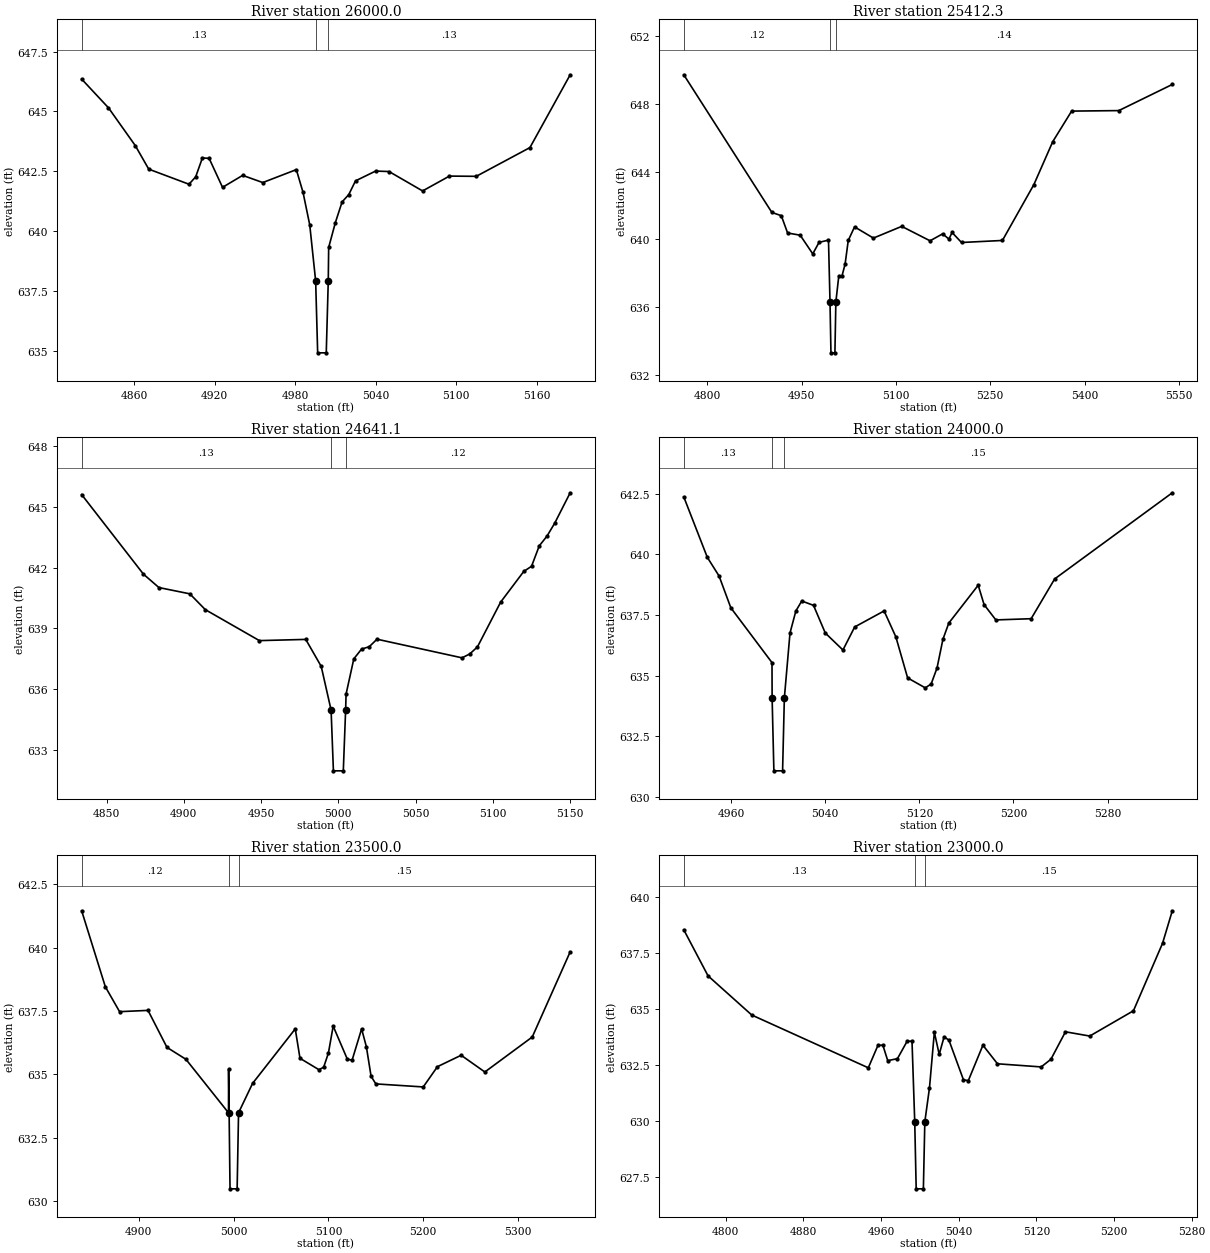
Type RM Length L Ch R = 1 ,26000.0,587.7,587.7,587.7
XS GIS Cut Line= 3
      1853534.64       766027.26      1853360.98       765983.48
      1853205.42       766083.62
BEGIN DESCRIPTION:
Greenbriar Creek 52.0
END DESCRIPTION:
#Sta/Elev= 30
  4820.9  646.35  4840.9  645.15  4860.9  643.57  4870.9  642.59  4900.9  641.96
  4905.9  642.27  4910.9  643.06  4915.9  643.04  4925.9  641.83  4940.9  642.33
  4955.9  642.03  4980.9  642.57  4985.9  641.62  4990.9  640.26  4995.3  637.92
  4996.8  634.92  5003.2  634.92  5004.7  637.92    5005  639.32    5010  640.36
    5015  641.22    5020  641.53    5025   642.1    5040  642.51    5050  642.49
    5075  641.68    5095   642.3    5115  642.29    5155  643.49    5185  646.53
#Mann= 3 , 1 , 0
 4820.90    0.13       0  4995.3    0.05       0  5004.7    0.13       0
Bank Sta=4995.30,5004.70
Exp/Cntr=0.3,0.1

Type RM Length L Ch R = 1 ,25412.3,771.2,771.2,771.2
XS GIS Cut Line= 3
      1853666.70       765755.04      1853507.62       765566.88
      1852987.07       765467.20
BEGIN DESCRIPTION:
Greenbriar Creek 51.0
END DESCRIPTION:
#Sta/Elev= 30
  4762.9   649.7  4902.9  641.59  4917.9   641.4  4927.9  640.38  4947.9  640.25
  4967.9  639.15  4977.9  639.83  4992.9  639.96  4995.3  636.32  4996.8  633.32
  5003.1  633.32  5004.6  636.32  5009.3  637.86  5014.3  637.84  5019.3  638.55
  5024.3  639.94  5034.3  640.74  5064.3  640.08  5109.3  640.77  5154.3  639.92
  5174.3  640.33  5184.3  640.02  5189.3  640.41  5204.3  639.82  5269.3  639.94
  5319.3  643.23  5349.3  645.76  5379.3  647.56  5454.3  647.59  5539.3  649.13
#Mann= 3 , 1 , 0
 4762.90    0.12       0  4995.3    0.05       0  5004.6    0.14       0
Bank Sta=4995.30,5004.60
Exp/Cntr=0.3,0.1

Type RM Length L Ch R = 1 ,24641.1,641.1,641.1,641.1
XS GIS Cut Line= 3
      1853823.65       765124.23      1853720.32       764994.23
      1853593.09       764914.71
BEGIN DESCRIPTION:
Greenbriar Creek 49.0
END DESCRIPTION:
#Sta/Elev= 27
  4833.9   645.6  4873.9  641.67  4883.9  641.01  4903.9   640.7  4913.9  639.92
  4948.9  638.39  4978.9  638.45  4988.9  637.12  4995.3  634.96  4996.8  631.96
  5003.2  631.96  5004.7  634.96    5005  635.75    5010  637.49    5015  637.97
    5020  638.09    5025  638.46    5080  637.54    5085  637.73    5090  638.08
    5105  640.29    5120  641.81    5125  642.06    5130  643.07    5135  643.55
    5140  644.19    5150  645.69
#Mann= 3 , 1 , 0
 4833.90    0.13       0  4995.3    0.05       0  5004.7    0.12       0
Bank Sta=4995.30,5004.70
Exp/Cntr=0.3,0.1

Type RM Length L Ch R = 1 ,24000.0,500,500,500
XS GIS Cut Line= 3
      1854175.91       764667.18      1854123.68       764606.18
      1853823.84       764456.78
BEGIN DESCRIPTION:
Greenbriar Creek 48.0
END DESCRIPTION:
#Sta/Elev= 30
  4919.7  642.37  4939.7  639.88  4949.7  639.11  4959.7   637.8  4994.7  635.54
  4994.8  634.08  4996.3  631.08  5003.7  631.08  5005.2  634.08    5010  636.76
    5015  637.67    5020  638.08    5030   637.9    5040  636.76    5055  636.06
    5065  637.01    5090  637.67    5100   636.6    5110  634.91    5125   634.5
    5130  634.66    5135  635.32    5140   636.5    5145  637.17    5170  638.73
    5175  637.93    5185   637.3    5215  637.35    5235  638.99    5335  642.54
#Mann= 3 , 1 , 0
 4919.70    0.13       0  4994.8    0.05       0  5005.2    0.15       0
Bank Sta=4994.80,5005.20
Exp/Cntr=0.3,0.1

Type RM Length L Ch R = 1 ,23500.0,500,500,500
XS GIS Cut Line= 3
      1854419.47       764226.37      1854279.41       764148.40
      1853926.47       764110.18
BEGIN DESCRIPTION:
Greenbriar Creek 47.0
END DESCRIPTION:
#Sta/Elev= 30
  4839.7  641.45  4864.7  638.45  4879.7  637.47  4909.7  637.52  4929.7  636.06
  4949.7  635.59  4994.6  633.48  4994.7  635.19  4996.2  630.48  5003.7  630.48
  5005.2  633.48    5020  634.64    5065  636.79    5070  635.63    5090  635.18
    5095  635.28    5100  635.84    5105   636.9    5120  635.59    5125  635.56
    5135  636.79    5140  636.09    5145  634.92    5150  634.62    5200   634.5
    5215   635.3    5240  635.75    5265  635.09    5315  636.47    5355  639.83
#Mann= 3 , 1 , 0
 4839.70    0.12       0  4994.6    0.05       0  5005.2    0.15       0
Bank Sta=4994.60,5005.20
Exp/Cntr=0.3,0.1

Type RM Length L Ch R = 1 ,23000.0,699.8,699.8,699.8
XS GIS Cut Line= 3
      1854356.44       763617.59      1854144.93       763737.21
      1853885.87       763759.38
BEGIN DESCRIPTION:
Greenbriar Creek 46.0
END DESCRIPTION:
#Sta/Elev= 30
    4757  638.53    4782  636.47    4827  634.72    4947  632.36    4957  633.37
    4962  633.37    4967  632.68    4977  632.77    4987  633.55    4992  633.55
  4994.8  629.95  4996.3  626.95  5003.7  626.95  5005.2  629.95    5010  631.47
    5015  633.95    5020  632.96    5025  633.74    5030   633.6    5045  631.82
    5050  631.79    5065  633.37    5080  632.54    5125   632.4    5135  632.74
    5150  633.97    5175  633.78    5220  634.91    5250  637.93    5260  639.38
#Mann= 3 , 1 , 0
 4757.00    0.13       0  4994.8    0.05       0  5005.2    0.15       0
Bank Sta=4994.80,5005.20
Exp/Cntr=0.3,0.1