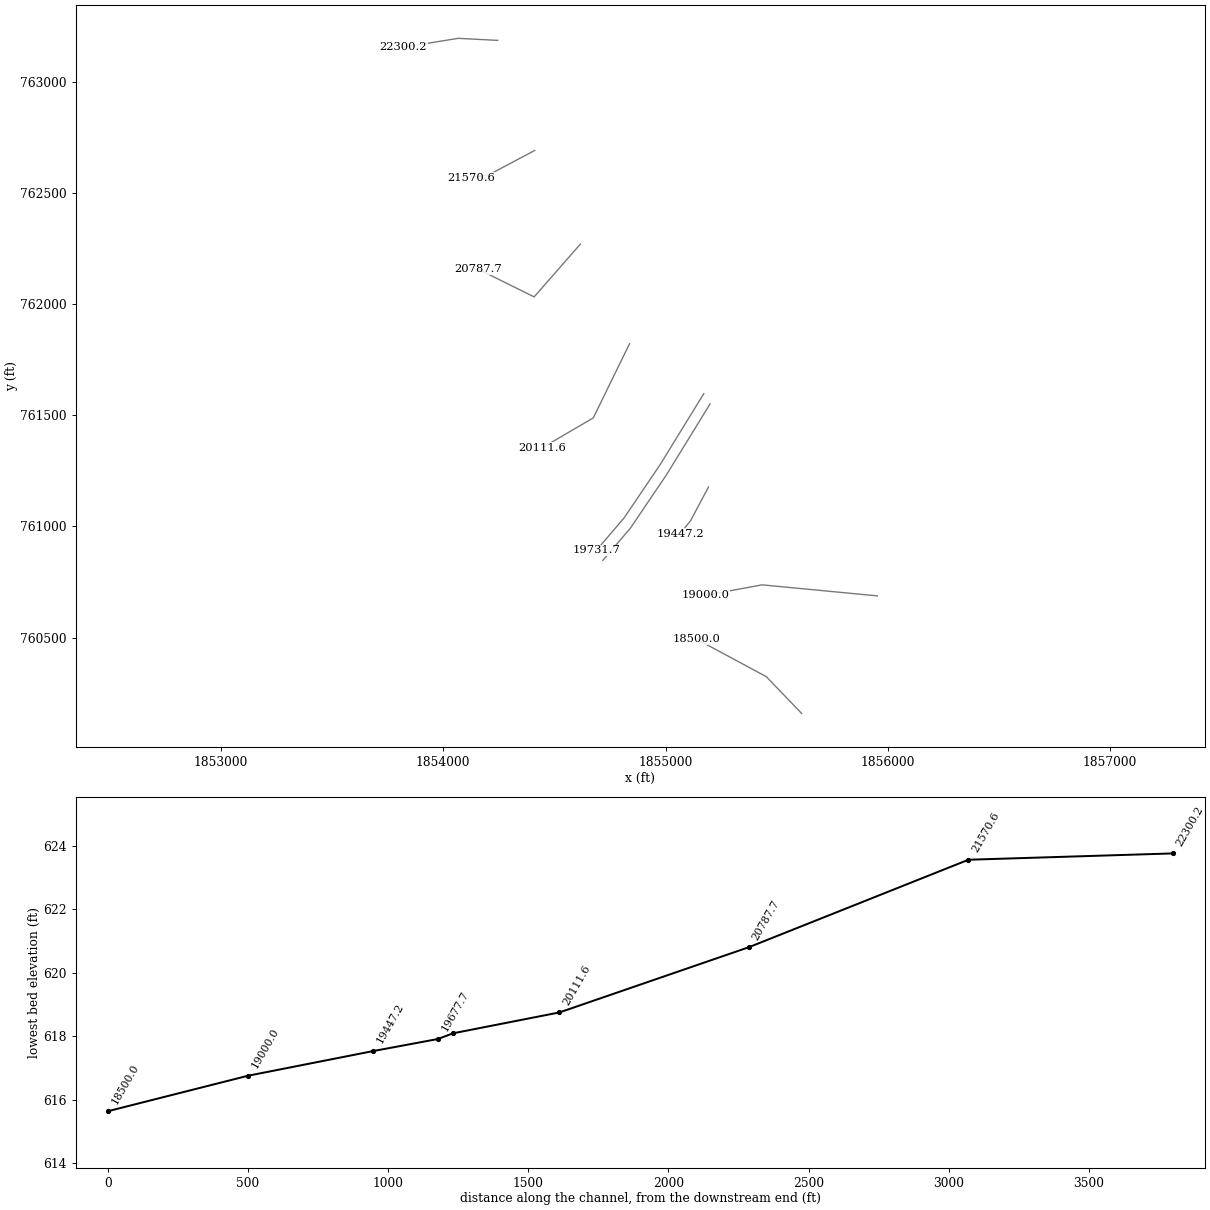
HEC-RAS study GREENBRIAR CREEK.PRJ: Greenbriar Creek

--- GREENBRIAR CREEK.g01 (geometry) --- (continued)

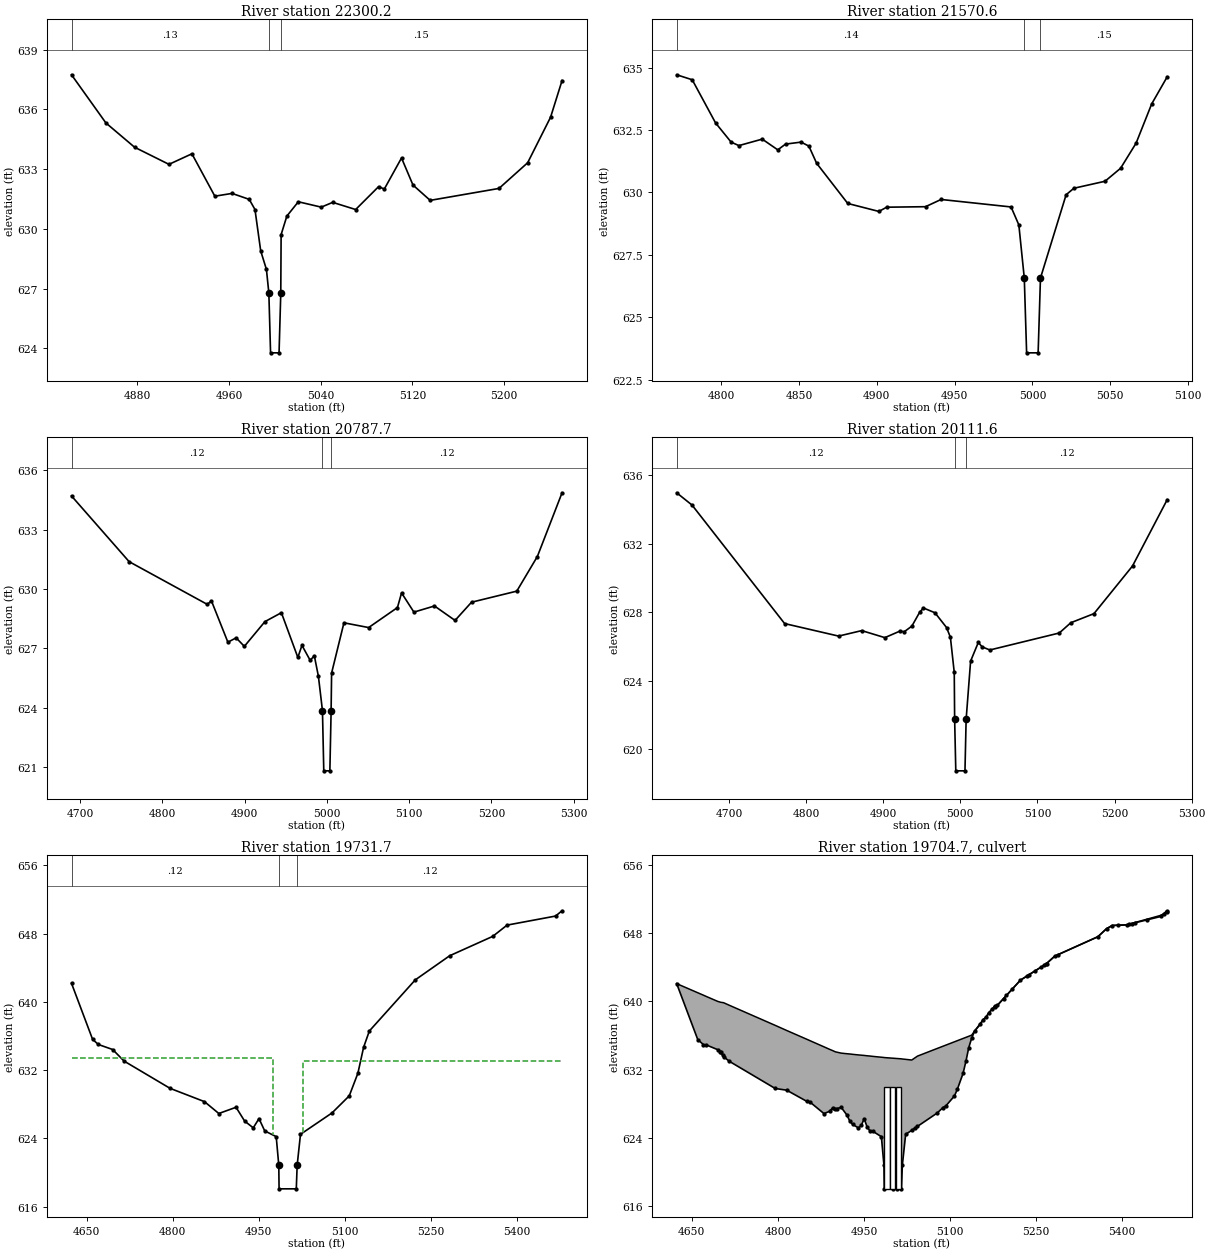
Type RM Length L Ch R = 1 ,22300.2,729.6,729.6,729.6
XS GIS Cut Line= 3
      1854244.78       763185.30      1854067.18       763194.46
      1853820.44       763154.44
BEGIN DESCRIPTION:
Greenbriar Creek 45.0
END DESCRIPTION:
#Sta/Elev= 30
  4822.7  637.74  4852.7  635.32  4877.7   634.1  4907.7  633.24  4927.7  633.77
  4947.7  631.64  4962.7  631.78  4977.7  631.48  4982.7  630.97  4987.7  628.89
  4992.7  627.96  4994.8  626.77  4996.3  623.77  5003.7  623.77  5005.2  626.77
  5005.5  629.71  5010.5  630.64  5020.5  631.36  5040.5  631.09  5050.5  631.33
  5070.5  630.97  5090.5  632.12  5095.5     632  5110.5  633.56  5120.5   632.2
  5135.5  631.43  5195.5  632.03  5220.5  633.32  5240.5  635.61  5250.5  637.45
#Mann= 3 , 1 , 0
 4822.70    0.13       0  4994.8    0.05       0  5005.2    0.15       0
Bank Sta=4994.80,5005.20
Exp/Cntr=0.3,0.1

Type RM Length L Ch R = 1 ,21570.6,782.9,782.9,782.9
XS GIS Cut Line= 3
      1854411.41       762690.40      1854207.89       762582.53
      1854124.39       762566.33
BEGIN DESCRIPTION:
Greenbriar Creek 43.0
END DESCRIPTION:
#Sta/Elev= 29
  4771.3  634.72  4781.3  634.52  4796.3  632.79  4806.3  632.02  4811.3  631.88
  4826.3  632.14  4836.3  631.71  4841.3  631.94  4851.3  632.02  4856.3  631.86
  4861.3  631.17  4881.3  629.56  4901.3  629.24  4906.3  629.41  4931.3  629.43
  4941.3  629.72  4986.3  629.42  4991.3   628.7  4994.8  626.57  4996.3  623.57
  5003.7  623.57  5005.2  626.57  5021.7  629.91  5026.7  630.17  5046.7  630.45
  5056.7  630.97  5066.7  631.98  5076.7  633.55  5086.7  634.64
#Mann= 3 , 1 , 0
 4771.30    0.14       0  4994.8    0.05       0  5005.2    0.15       0
Bank Sta=4994.80,5005.20
Exp/Cntr=0.3,0.1

Type RM Length L Ch R = 1 ,20787.7,676.1,676.1,676.1
XS GIS Cut Line= 3
      1854617.01       762269.67      1854408.73       762031.97
      1854157.87       762156.25
BEGIN DESCRIPTION:
Greenbriar Creek 42.0
END DESCRIPTION:
#Sta/Elev= 30
  4689.8   634.7  4759.8  631.38  4854.8  629.22  4859.8   629.4  4879.8  627.31
  4889.8  627.53  4899.8   627.1  4924.8  628.35  4944.8   628.8  4964.8  626.54
  4969.8  627.15  4979.8  626.39  4984.8  626.63  4989.8  625.58  4994.7  623.85
  4996.3  620.81  5003.7  620.81  5005.2  623.81  5005.8  625.75  5020.8  628.29
  5050.8  628.05  5085.8  629.06  5090.8   629.8  5105.8  628.83  5130.8  629.14
  5155.8  628.41  5175.8  629.33  5230.8  629.89  5255.8  631.64  5285.8  634.86
#Mann= 3 , 1 , 0
 4689.80    0.12       0  4994.7    0.05       0  5005.2    0.12       0
Bank Sta=4994.70,5005.20
Exp/Cntr=0.3,0.1

Type RM Length L Ch R = 1 ,20111.6,379.9,379.9,379.9
XS GIS Cut Line= 3
      1854837.83       761821.37      1854674.61       761487.94
      1854445.88       761354.20
BEGIN DESCRIPTION:
Greenbriar Creek 40.0
END DESCRIPTION:
#Sta/Elev= 28
  4632.1  634.97  4652.1  634.25  4772.1  627.34  4842.1  626.61  4872.1  626.93
  4902.1  626.52  4922.1  626.91  4927.1  626.86  4937.1  627.19  4947.1  627.99
  4952.1  628.25  4967.1  627.97  4982.1  627.11  4987.1  626.54  4992.1  624.49
  4992.6  621.75  4994.1  618.75    5006  618.75  5007.5  621.75  5013.3  625.15
  5023.3  626.24  5028.3  625.98  5038.3   625.8  5128.3  626.79  5143.3  627.39
  5173.3  627.92  5223.3   630.7  5268.3  634.57
#Mann= 3 , 1 , 0
 4632.10    0.12       0  4992.6    0.05       0  5007.5    0.12       0
Bank Sta=4992.60,5007.50
Exp/Cntr=0.5,0.3

Type RM Length L Ch R = 1 ,19731.7,54,54,54
XS GIS Cut Line= 4
      1855171.77       761596.84      1854975.43       761277.79
      1854813.41       761038.39      1854689.10       760893.29
BEGIN DESCRIPTION:
Upstream Section of Bridge/Culvert/Weir
END DESCRIPTION:
#Sta/Elev= 30
  4623.6  642.18  4660.3  635.62  4670.3  635.01  4695.3  634.42  4715.3  633.06
  4795.3  629.87  4855.3  628.31  4880.3  626.92  4910.3  627.65  4925.3  626.03
  4940.3  625.24  4950.3  626.32  4960.3  624.88  4980.3  624.21  4984.8  620.84
  4985.3  618.09  5015.3  618.09  5016.8  620.84  5022.6  624.48  5077.6  626.99
  5107.6  628.99  5122.6  631.63  5132.6  634.68  5142.6  636.59  5222.6  642.58
  5282.6  645.41  5357.6  647.68  5382.6     649    5467  650.06  5478.4  650.68
#Mann= 3 , 1 , 0
 4623.60    0.12       0  4984.8    0.05       0  5016.8    0.12       0
#XS Ineff= 2 , 0
       0  4974.8  633.42  5026.8       0  633.12
Bank Sta=4984.80,5016.80
Exp/Cntr=0.5,0.3

Type RM Length L Ch R = 2 ,19704.7,,,
BEGIN DESCRIPTION:
Staley Snow Camp Rd
Structure ID: NCF-0279
Approximate Survey Structure
END DESCRIPTION:
Bridge Culvert--1,0,-1,-1, 0
Deck Dist Width WeirC Skew NumUp NumDn MinLoCord MaxHiCord MaxSubmerge Is_Ogee
10,34,3,, 60, 60,,,0.95,0,1,1,,
  4623.6  4660.3  4670.3  4675.3  4695.3  4700.3  4705.3  4715.3  4795.3  4815.3
  4850.3  4855.3  4880.3  4890.3  4895.3  4900.3  4910.3  4920.3  4925.3  4930.3
  4940.3  4945.3  4950.3  4955.3  4960.3  4965.3  4980.3  4984.8  4985.3  5015.3
  5016.8  5022.6  5033.2  5043.2  5077.6  5087.6  5092.6  5107.6  5112.6  5122.6
  5127.6  5132.6  5137.6  5142.6  5157.6  5162.6  5167.6  5177.6  5182.6  5222.6
  5267.6  5282.6  5357.6  5372.6  5382.6  5407.6    5467  5472.3  5477.3  5478.4
  642.09  641.02  640.73  640.58     640   639.9  639.85  639.55  637.19  636.59
  635.56  635.41  634.67  634.37  634.23  634.08  633.93  633.86  633.83  633.79
  633.72  633.69  633.66  633.62  633.59  633.55  633.45  633.42  633.41  633.26
  633.24   633.2  633.12  633.58  634.48  634.74  634.87  635.26  635.39  635.65
  635.78  635.91  636.04  636.51  637.85  638.14  638.68  639.41  639.56   642.5
  644.42  645.33   647.6  648.54  648.92  648.99   650.1  650.29  650.64  650.59
  642.09  635.53  634.92  634.89  634.33  634.01  633.52  632.97  629.78  629.58
  628.27  628.22  626.83  627.11  627.49  627.36  627.56  626.66  625.94  625.56
  625.15  625.44  626.23  625.29  624.79  624.76  624.12  620.75     618     618
  620.75  624.39  624.87  625.33   626.9  627.54  627.73   628.9  629.67  631.54
  632.96  634.59  635.68   636.5  637.84  638.13  638.67   639.4  639.55  642.49
  644.41  645.32  647.59  648.53  648.91  648.98  649.97  650.26  650.53  650.59
  4623.6  4660.3  4670.3  4675.3  4695.3  4700.3  4705.3  4715.3  4795.3  4815.3
  4850.3  4855.3  4880.3  4890.3  4895.3  4900.3  4910.3  4920.3  4925.3  4930.3
  4940.3  4945.3  4950.3  4955.3  4960.3  4965.3  4980.3  4984.8  4985.3  5015.3
  5016.8  5022.6  5033.2  5043.2  5077.6  5087.6  5092.6  5107.6  5112.6  5122.6
  5127.6  5132.6  5137.6  5142.6  5157.6  5162.6  5167.6  5177.6  5182.6  5222.6
  5267.6  5282.6  5357.6  5372.6  5382.6  5407.6    5467  5472.3  5477.3  5478.4
  642.09  641.02  640.73  640.58     640   639.9  639.85  639.55  637.19  636.59
  635.56  635.41  634.67  634.37  634.23  634.08  633.93  633.86  633.83  633.79
  633.72  633.69  633.66  633.62  633.59  633.55  633.45  633.42  633.41  633.26
  633.24   633.2  633.12  633.58  634.48  634.74  634.87  635.26  635.39  635.65
  635.78  635.91  636.04  636.51  637.85  638.14  638.68  639.41  639.56   642.5
  644.42  645.33   647.6  648.54  648.92  648.99   650.1  650.29  650.64  650.59
  641.92  635.36  634.75  634.72  634.16  633.84  633.35   632.8  629.61  629.41
   628.1  628.05  626.66  626.94  627.32  627.19  627.39  626.49  625.77  625.39
  624.98  625.27  626.06  625.12  624.62  624.59  623.95  620.58  617.83  617.83
  620.58  624.22   624.7  625.16  626.73  627.37  627.56  628.73   629.5  631.37
  632.79  634.42  635.51  636.33  637.67  637.96   638.5  639.23  639.38  642.32
  644.24  645.15  647.42  648.36  648.74  648.81   649.8  650.09  650.36  650.42
BR Coef= 1 , 0 , 0 ,1.25, 0 ,,,0.8,-1,2,0,
Wspro=,,,, 1 ,,,, 0 ,,,, 0 ,,,,-1 ,-1 ,-1 , 0 , 0 , 0 , 0 , 0
Culvert=2,12.0,9.0,34.0,0.015,0.5,1.0,10,1,618.00,4989.97,617.83,4989.97,Culvert #1  ,0,10
Culvert=2,12.0,9.0,34.0,0.015,0.5,1.0,10,1,618.00,4999.97,617.83,4999.97,Culvert #2  ,0,10
Culvert=2,12.0,9.0,34.0,0.015,0.5,1.0,10,1,618.00,5009.97,617.83,5009.97,Culvert #3  ,0,10
BC Design=,, 0 ,, 0 ,,,,,,
BR U #Sta/Elev= 84
  4623.6  642.09  4660.3  635.53  4670.3  634.92  4675.3  634.89  4695.3  634.33
  4698.6  634.12  4700.3  634.01  4703.6  633.69  4705.3  633.52  4715.3  632.97
  4795.3  629.78  4815.3  629.58  4850.3  628.27  4855.3  628.22  4880.3  626.83
  4890.3  627.11  4895.3  627.49  4900.3  627.36  4903.6  627.43  4910.3  627.56
  4920.3  626.66  4925.3  625.94  4930.3  625.56  4940.3  625.15  4945.3  625.44
  4950.3  626.23  4955.3  625.29  4960.3  624.79  4965.3  624.76  4980.3  624.12
  4984.8  620.75  4985.3     618    5000     618  5008.2     618  5015.3     618
  5016.8  620.75  5022.6  624.39  5033.2  624.87  5038.2   625.1  5043.2  625.33
  5077.6   626.9  5087.6  627.54  5092.6  627.73  5107.6   628.9  5112.6  629.67
  5122.6  631.54  5127.6  632.96  5132.6  634.59  5137.6  635.68  5142.6   636.5
  5152.6  637.31  5157.6  637.84  5162.6  638.13  5167.6  638.67  5173.2  639.08
  5177.6   639.4  5178.2  639.42  5182.6  639.55  5193.2  640.33  5198.2   640.7
  5208.2  641.43  5222.6  642.49  5233.2  642.94  5238.2  643.16  5248.2  643.58
  5258.2  644.01  5263.2  644.22  5267.6  644.41  5268.2  644.45  5282.6  645.32
  5287.3  645.46  5357.6  647.59  5372.6  648.53  5382.6  648.91  5392.3  648.94
  5407.6  648.98  5412.3  649.06  5417.3  649.14  5422.3  649.23  5442.3  649.56
    5467  649.97  5472.3  650.26  5477.3  650.53  5478.4  650.59
BR U #Mann= 3
 4623.60    0.12  4984.8    0.05  5016.8    0.12
BR U Banks=4984.80,5016.80
BR D #Sta/Elev= 84
  4623.6  641.92  4660.3  635.36  4670.3  634.75  4675.3  634.72  4695.3  634.16
  4698.6  633.95  4700.3  633.84  4703.6  633.52  4705.3  633.35  4715.3   632.8
  4795.3  629.61  4815.3  629.41  4850.3   628.1  4855.3  628.05  4880.3  626.66
  4890.3  626.94  4895.3  627.32  4900.3  627.19  4903.6  627.26  4910.3  627.39
  4920.3  626.49  4925.3  625.77  4930.3  625.39  4940.3  624.98  4945.3  625.27
  4950.3  626.06  4955.3  625.12  4960.3  624.62  4965.3  624.59  4980.3  623.95
  4984.8  620.58  4985.3  617.83    5000  617.83  5008.2  617.83  5015.3  617.83
  5016.8  620.58  5022.6  624.22  5033.2   624.7  5038.2  624.93  5043.2  625.16
  5077.6  626.73  5087.6  627.37  5092.6  627.56  5107.6  628.73  5112.6   629.5
  5122.6  631.37  5127.6  632.79  5132.6  634.42  5137.6  635.51  5142.6  636.33
  5152.6  637.14  5157.6  637.67  5162.6  637.96  5167.6   638.5  5173.2  638.91
  5177.6  639.23  5178.2  639.25  5182.6  639.38  5193.2  640.16  5198.2  640.53
  5208.2  641.26  5222.6  642.32  5233.2  642.77  5238.2  642.99  5248.2  643.41
  5258.2  643.84  5263.2  644.05  5267.6  644.24  5268.2  644.28  5282.6  645.15
  5287.3  645.29  5357.6  647.42  5372.6  648.36  5382.6  648.74  5392.3  648.77
  5407.6  648.81  5412.3  648.89  5417.3  648.97  5422.3  649.06  5442.3  649.39
    5467   649.8  5472.3  650.09  5477.3  650.36  5478.4  650.42
BR D #Mann= 3
 4623.60    0.12  4984.8    0.05  5016.8    0.12
BR D Banks=4984.80,5016.80

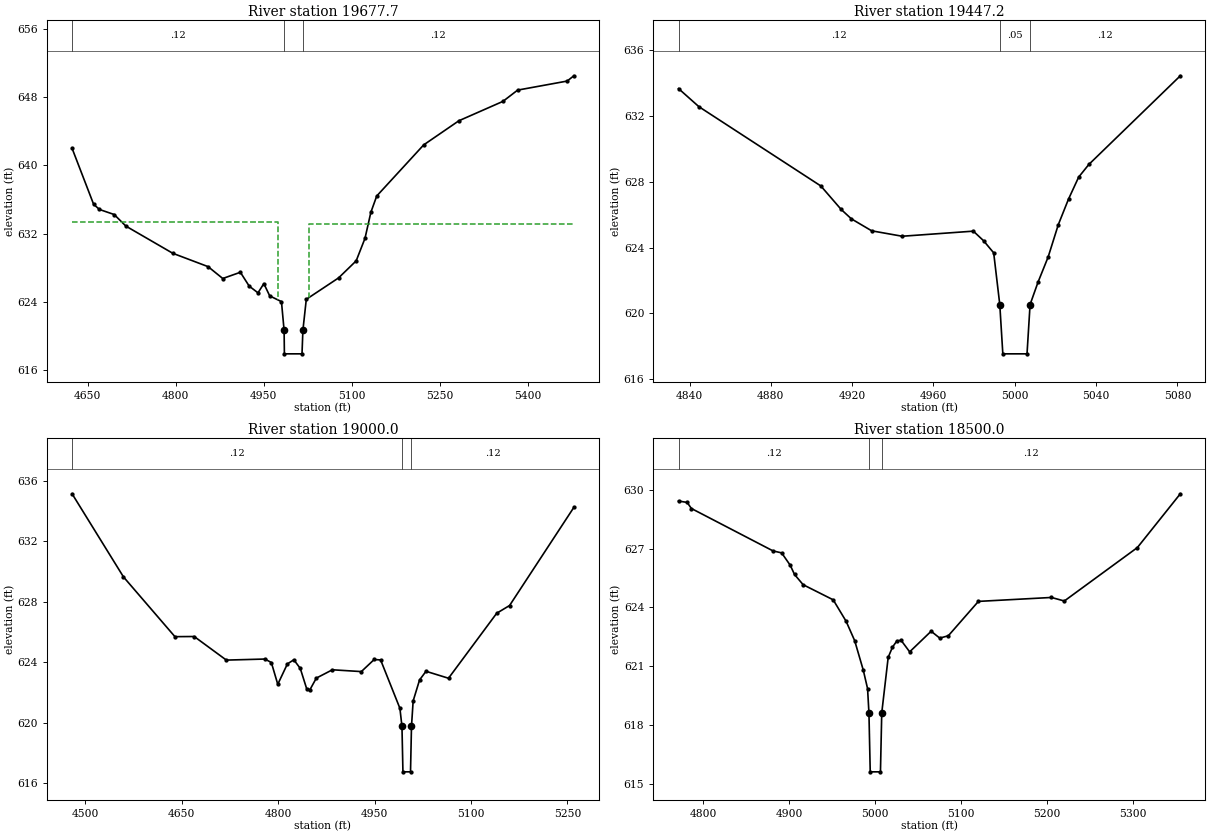
Type RM Length L Ch R = 1 ,19677.7,230.5,230.5,230.5
XS GIS Cut Line= 4
      1855200.05       761550.84      1855003.71       761231.79
      1854841.69       760992.39      1854717.38       760847.29
BEGIN DESCRIPTION:
Downstream Section of Bridge/Culvert/Weir
END DESCRIPTION:
#Sta/Elev= 30
  4623.6     642  4660.3  635.44  4670.3  634.83  4695.3  634.24  4715.3  632.88
  4795.3  629.69  4855.3  628.13  4880.3  626.74  4910.3  627.47  4925.3  625.85
  4940.3  625.06  4950.3  626.14  4960.3   624.7  4980.3  624.03  4984.8  620.66
  4985.3  617.91  5015.3  617.91  5016.8  620.66  5022.6   624.3  5077.6  626.81
  5107.6  628.81  5122.6  631.45  5132.6   634.5  5142.6  636.41  5222.6   642.4
  5282.6  645.23  5357.6   647.5  5382.6  648.82    5467  649.88  5478.4   650.5
#Mann= 3 , 1 , 0
 4623.60    0.12       0  4984.8    0.05       0  5016.8    0.12       0
#XS Ineff= 2 , 0
       0  4974.8  633.42  5026.8       0  633.12
Bank Sta=4984.80,5016.80
Exp/Cntr=0.5,0.3

Type RM Length L Ch R = 1 ,19447.2,447.2,447.2,447.2
XS GIS Cut Line= 3
      1855193.03       761177.39      1855112.28       761025.73
      1855065.44       760967.18
BEGIN DESCRIPTION:
Greenbriar Creek 39.0
END DESCRIPTION:
#Sta/Elev= 21
  4834.6  633.68  4844.6  632.58  4904.6  627.75  4914.6  626.32  4919.6  625.75
  4929.6  625.02  4944.6  624.69  4979.6     625  4984.6  624.42  4989.6  623.68
  4992.6  620.53  4994.1  617.53    5006  617.53  5007.5  620.53  5011.4  621.89
  5016.4  623.43  5021.4   625.4  5026.4  626.95  5031.4  628.29  5036.4  629.06
  5081.4  634.46
#Mann= 3 , 1 , 0
 4834.60    0.12       0  4992.6    0.05       0  5007.5    0.12       0
Bank Sta=4992.60,5007.50
Exp/Cntr=0.3,0.1

Type RM Length L Ch R = 1 ,19000.0,500,500,500
XS GIS Cut Line= 3
      1855952.44       760687.85      1855434.20       760737.41
      1855178.52       760690.26
BEGIN DESCRIPTION:
Greenbriar Creek 38.0
END DESCRIPTION:
#Sta/Elev= 30
  4479.4  635.14  4559.4  629.64  4639.4  625.69  4669.4   625.7  4719.4  624.14
  4779.4  624.21  4789.4  623.98  4799.4  622.54  4814.4  623.89  4824.4  624.16
  4834.4  623.59  4844.4  622.24  4849.4  622.18  4859.4  622.95  4884.4   623.5
  4929.4  623.38  4949.4  624.18  4959.4  624.15  4989.4  620.95  4992.6  619.75
  4994.1  616.75  5005.9  616.75  5007.4  619.75    5010  621.44    5020  622.83
    5030   623.4    5065  622.94    5140  627.24    5160  627.75    5260  634.24
#Mann= 3 , 1 , 0
 4479.40    0.12       0  4992.6    0.05       0  5007.4    0.12       0
Bank Sta=4992.60,5007.40
Exp/Cntr=0.3,0.1

Type RM Length L Ch R = 1 ,18500.0,500,500,500
XS GIS Cut Line= 3
      1855611.74       760159.61      1855453.04       760324.70
      1855140.34       760492.76
BEGIN DESCRIPTION:
Greenbriar Creek 37.0
END DESCRIPTION:
#Sta/Elev= 30
    4771  629.42    4781  629.35    4786  629.04    4881  626.88    4891  626.78
    4901  626.15    4906  625.68    4916  625.16    4951  624.39    4966   623.3
    4976  622.31    4986  620.81    4991  619.87  4992.6  618.63  4994.1  615.63
    5006  615.63  5007.5  618.63    5015  621.46    5020  621.98    5025  622.29
    5030  622.33    5040  621.74    5065  622.79    5075  622.44    5085  622.56
    5120  624.31    5205  624.51    5220  624.33    5305  627.05    5355  629.79
#Mann= 3 , 1 , 0
 4771.00    0.12       0  4992.6    0.05       0  5007.5    0.12       0
Bank Sta=4992.60,5007.50
Exp/Cntr=0.3,0.1