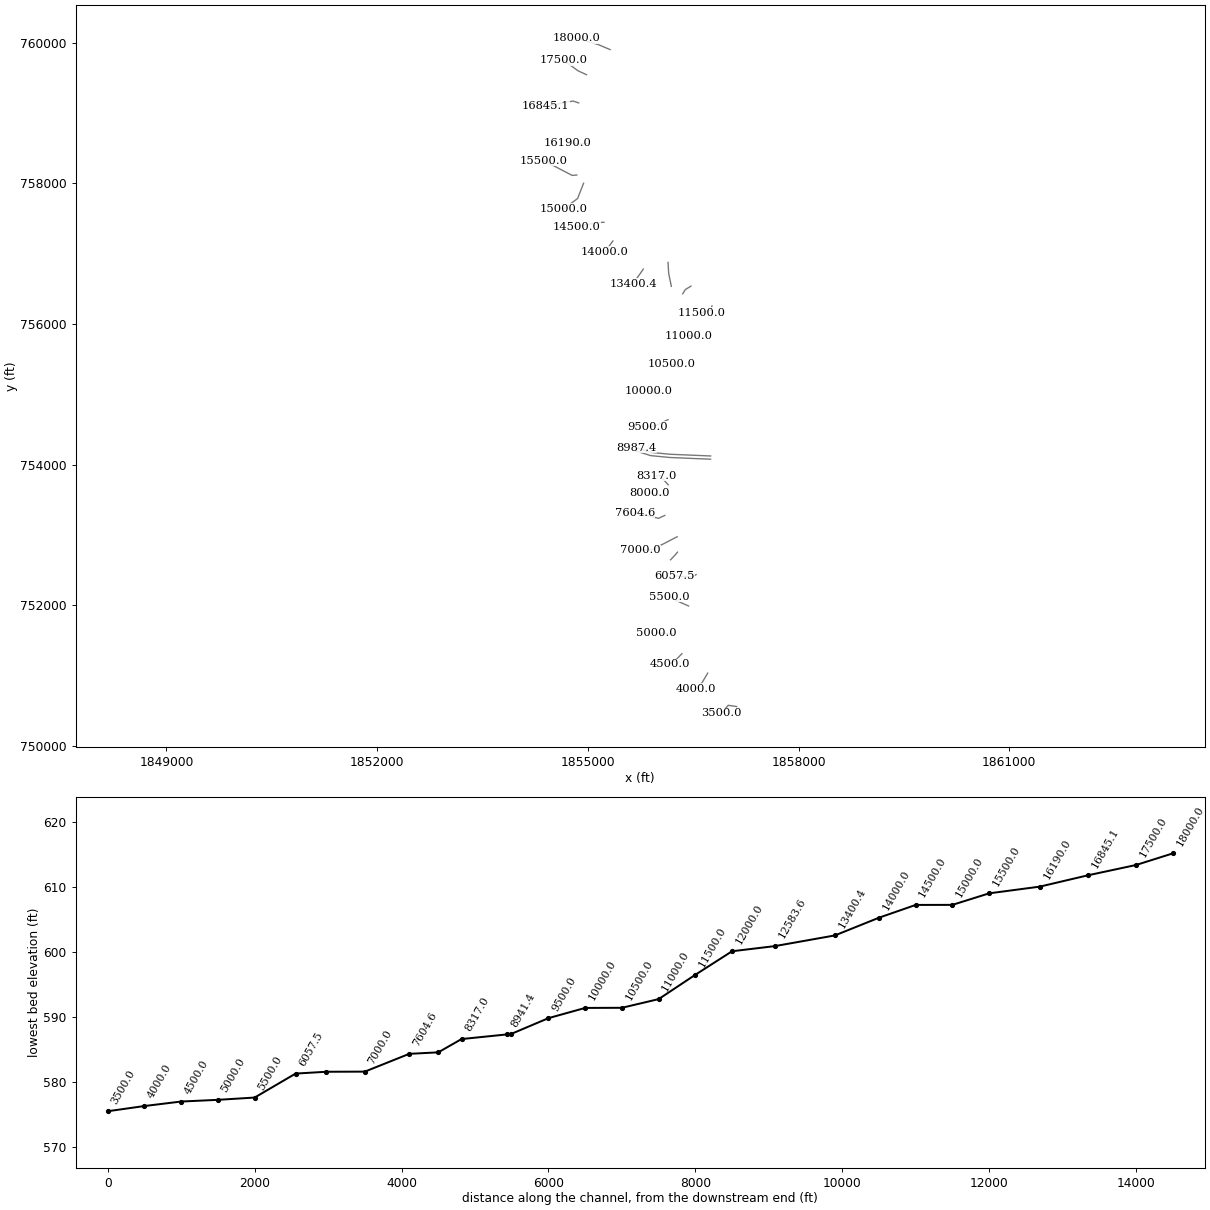
HEC-RAS study GREENBRIAR CREEK.PRJ: Greenbriar Creek

--- GREENBRIAR CREEK.g01 (geometry) --- (continued)

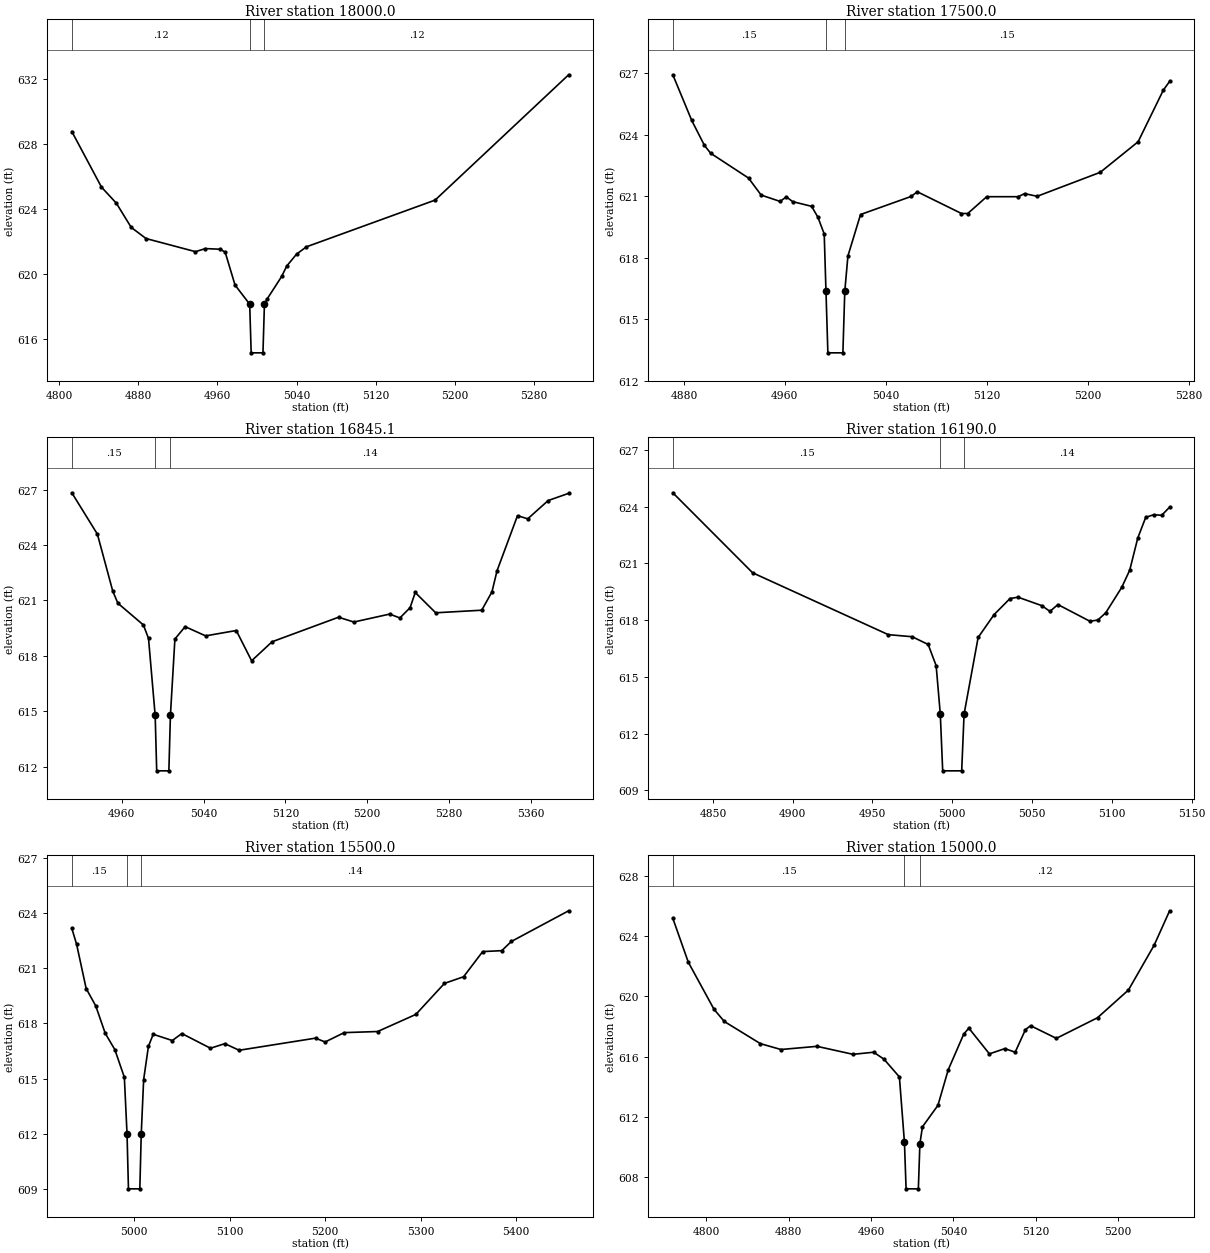
Type RM Length L Ch R = 1 ,18000.0,500,500,500
XS GIS Cut Line= 3
      1855317.60       759904.43      1855145.14       759977.23
      1854842.49       760064.57
BEGIN DESCRIPTION:
Greenbriar Creek 36.0
END DESCRIPTION:
#Sta/Elev= 21
  4812.8  628.78  4842.8  625.35  4857.8  624.36  4872.8  622.87  4887.8  622.18
  4937.8  621.37  4947.8  621.56  4962.8  621.52  4967.8  621.34  4977.8  619.31
  4992.6  618.13  4994.1  615.13    5006  615.13  5007.5  618.13    5010  618.43
    5025  619.85    5030  620.48    5040  621.22    5050  621.67    5180  624.55
    5315  632.28
#Mann= 3 , 1 , 0
 4812.80    0.12       0  4992.6    0.05       0  5007.5    0.12       0
Bank Sta=4992.60,5007.50
Exp/Cntr=0.3,0.1

Type RM Length L Ch R = 1 ,17500.0,654.9,654.9,654.9
XS GIS Cut Line= 3
      1854982.08       759547.65      1854864.68       759600.63
      1854649.91       759755.87
BEGIN DESCRIPTION:
Greenbriar Creek 35.0
END DESCRIPTION:
#Sta/Elev= 30
  4871.2  626.92  4886.2  624.69  4896.2  623.48  4901.2  623.09  4931.2  621.88
  4941.2  621.05  4956.2  620.74  4961.2  620.96  4966.2  620.73  4981.2   620.5
  4986.2  619.97  4991.2  619.15  4992.6  616.35  4994.1  613.35    5006  613.35
  5007.5  616.35    5010  618.08    5020   620.1    5060  620.98    5065  621.21
    5100  620.15    5105  620.15    5120  620.97    5145  620.97    5150  621.12
    5160  620.99    5210  622.16    5240  623.65    5260  626.17    5265   626.6
#Mann= 3 , 1 , 0
 4871.20    0.15       0  4992.6    0.05       0  5007.5    0.15       0
Bank Sta=4992.60,5007.50
Exp/Cntr=0.3,0.1

Type RM Length L Ch R = 1 ,16845.1,655.1,655.1,655.1
XS GIS Cut Line= 3
      1854870.72       759146.14      1854789.14       759172.78
      1854396.81       759094.94
BEGIN DESCRIPTION:
Greenbriar Creek 34.0
END DESCRIPTION:
#Sta/Elev= 30
  4911.1  626.83  4936.1  624.59  4951.1  621.51  4956.1  620.85  4981.1  619.67
  4986.1  618.94  4992.6  614.77  4994.1  611.77    5006  611.77  5007.5  614.77
  5011.9  618.91  5021.9  619.58  5041.9  619.08  5071.9  619.37  5086.9  617.73
  5106.9  618.76  5171.9  620.09  5186.9  619.83  5221.9  620.26  5231.9  620.05
  5241.9  620.61  5246.9  621.43  5266.9  620.33  5311.9  620.47  5321.9  621.46
  5326.9  622.61  5346.9  625.59  5356.9  625.42  5376.9  626.41  5396.9   626.8
#Mann= 3 , 1 , 0
 4911.10    0.15       0  4992.6    0.05       0  5007.5    0.14       0
Bank Sta=4992.60,5007.50
Exp/Cntr=0.3,0.1

Type RM Length L Ch R = 1 ,16190.0,690,690,690
XS GIS Cut Line= 3
      1855019.69       758570.72      1854843.75       758559.19
      1854709.45       758572.68
BEGIN DESCRIPTION:
Greenbriar Creek 32.0
END DESCRIPTION:
#Sta/Elev= 27
  4824.9  624.73  4874.9   620.5  4959.9  617.23  4974.9  617.12  4984.9  616.71
  4989.9  615.59  4992.5  613.03    4994  610.03  5005.9  610.03  5007.4  613.03
  5016.2  617.08  5026.2  618.29  5036.2  619.14  5041.2  619.21  5056.2  618.76
  5061.2  618.46  5066.2  618.82  5086.2  617.94  5091.2     618  5096.2  618.39
  5106.2  619.73  5111.2  620.64  5116.2  622.33  5121.2  623.43  5126.2  623.57
  5131.2  623.54  5136.2  623.97
#Mann= 3 , 1 , 0
 4824.90    0.15       0  4992.5    0.05       0  5007.4    0.14       0
Bank Sta=4992.50,5007.40
Exp/Cntr=0.3,0.1

Type RM Length L Ch R = 1 ,15500.0,500,500,500
XS GIS Cut Line= 3
      1854842.98       758120.09      1854778.02       758114.52
      1854374.35       758324.46
BEGIN DESCRIPTION:
Greenbriar Creek 31.0
END DESCRIPTION:
#Sta/Elev= 30
  4934.8  623.17  4939.8  622.31  4949.8   619.9  4959.8  618.96  4969.8  617.46
  4979.8  616.58  4989.8  615.07  4992.6     612  4994.1     609    5006     609
  5007.5     612    5010  614.94    5015  616.75    5020  617.41    5040  617.07
    5050  617.45    5080  616.65    5095   616.9    5110  616.54    5190   617.2
    5200  616.99    5220   617.5    5255  617.56    5295  618.49    5325  620.18
    5345  620.54    5365  621.91    5385  621.96    5395  622.46    5455  624.13
#Mann= 3 , 1 , 0
 4934.80    0.15       0  4992.6    0.05       0  5007.5    0.14       0
Bank Sta=4992.60,5007.50
Exp/Cntr=0.3,0.1

Type RM Length L Ch R = 1 ,15000.0,500,500,500
XS GIS Cut Line= 3
      1854939.99       758003.04      1854855.31       757786.61
      1854655.00       757637.02
BEGIN DESCRIPTION:
Greenbriar Creek 30.0
END DESCRIPTION:
#Sta/Elev= 30
  4767.6  625.19  4782.6  622.28  4807.6  619.15  4817.6  618.34  4852.6  616.87
  4872.6  616.48  4907.6  616.69  4942.6  616.16  4962.6   616.3  4972.6  615.84
  4987.6  614.66  4992.5  610.32  4994.1  607.23    5006  607.23  5007.5  610.23
    5010  611.35    5025  612.77    5035  615.13    5050  617.49    5055   617.9
    5075  616.19    5090  616.54    5100   616.3    5110   617.8    5115  618.06
    5140  617.22    5180  618.59    5210  620.43    5235  623.41    5250  625.69
#Mann= 3 , 1 , 0
 4767.60    0.15       0  4992.5    0.05       0  5007.5    0.12       0
Bank Sta=4992.50,5007.50
Exp/Cntr=0.3,0.1

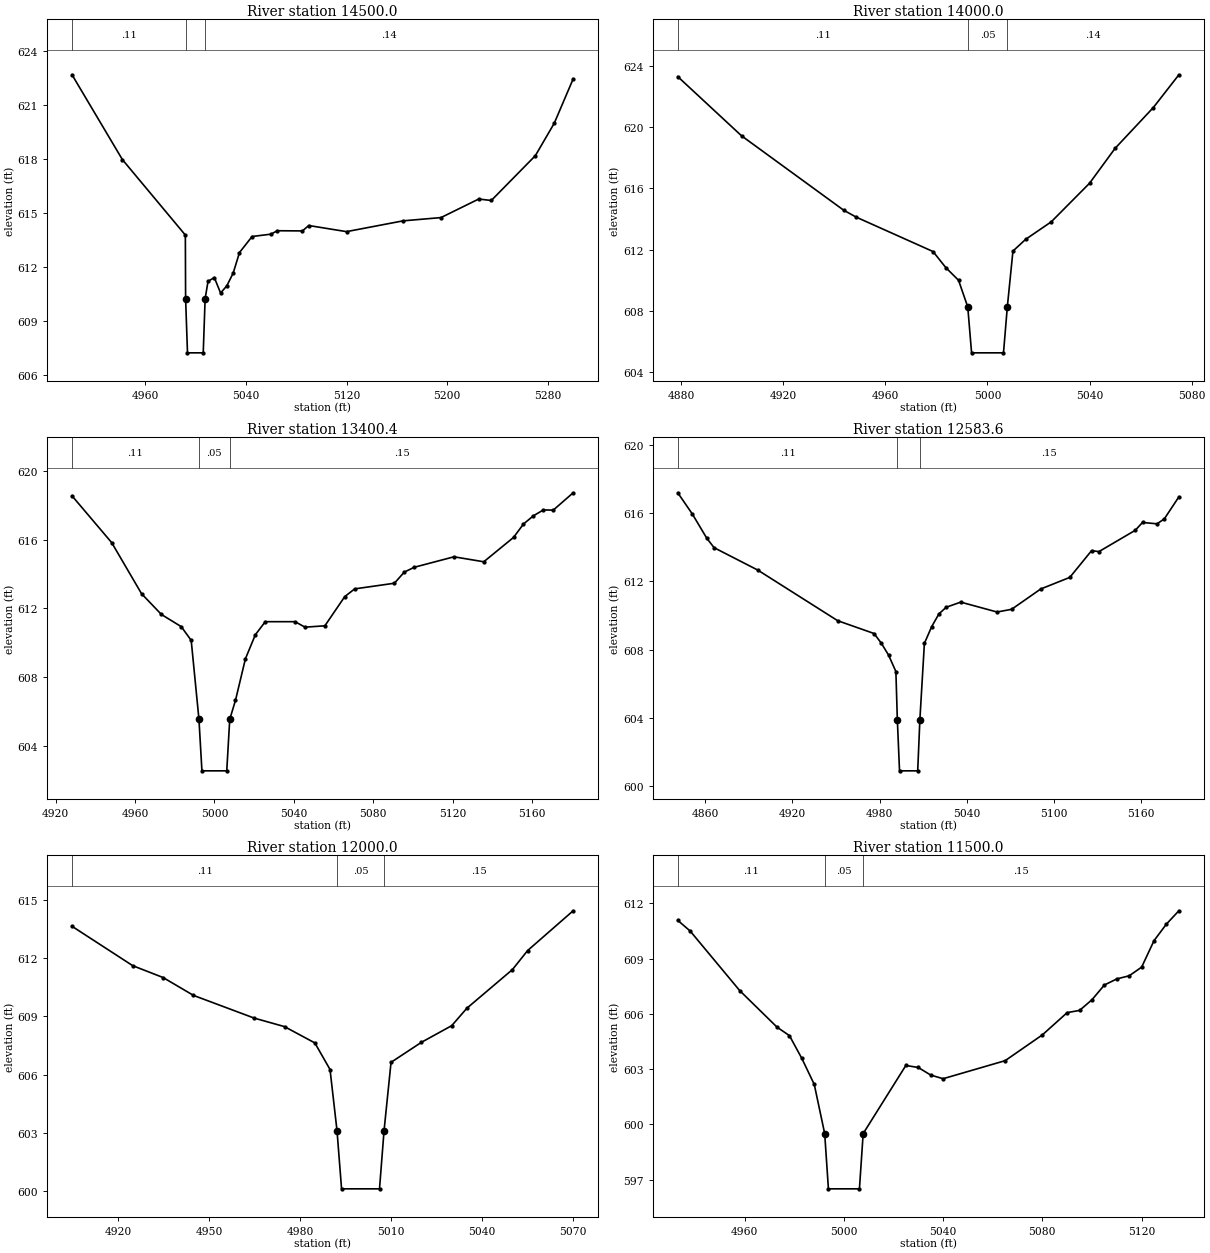
Type RM Length L Ch R = 1 ,14500.0,500,500,500
XS GIS Cut Line= 3
      1855230.17       757447.70      1855132.29       757442.73
      1854837.58       757386.67
BEGIN DESCRIPTION:
Greenbriar Creek 29.0
END DESCRIPTION:
#Sta/Elev= 26
    4902  622.66    4942  617.95    4992  613.76  4992.2  610.22  4993.7  607.22
  5006.2  607.22  5007.7  610.22    5010  611.19    5015   611.4    5020  610.54
    5025  610.95    5030  611.65    5035  612.79    5045  613.68    5060  613.81
    5065     614    5085  613.99    5090  614.29    5120  613.95    5165  614.55
    5195  614.73    5225  615.76    5235  615.68    5270  618.17    5285  619.97
    5300  622.43
#Mann= 3 , 1 , 0
 4902.00    0.11       0  4992.2    0.05       0  5007.7    0.14       0
Bank Sta=4992.20,5007.70
Exp/Cntr=0.3,0.1

Type RM Length L Ch R = 1 ,14000.0,599.6,599.6,599.6
XS GIS Cut Line= 3
      1855357.67       757182.44      1855286.42       757084.27
      1855241.02       757024.57
BEGIN DESCRIPTION:
Greenbriar Creek 28.0
END DESCRIPTION:
#Sta/Elev= 18
  4878.7  623.31  4903.7  619.44  4943.7  614.58  4948.7  614.12  4978.7  611.88
  4983.7  610.83  4988.7     610  4992.3  608.26  4993.8  605.26  5006.3  605.26
  5007.8  608.26    5010  611.91    5015  612.68    5025  613.82    5040  616.34
    5050  618.62    5065  621.29    5075  623.43
#Mann= 3 , 1 , 0
 4878.70    0.11       0  4992.3    0.05       0  5007.8    0.14       0
Bank Sta=4992.30,5007.80
Exp/Cntr=0.3,0.1

Type RM Length L Ch R = 1 ,13400.4,816.8,816.8,816.8
XS GIS Cut Line= 3
      1855790.20       756782.21      1855746.29       756718.54
      1855643.95       756576.63
BEGIN DESCRIPTION:
Greenbriar Creek 27.0
END DESCRIPTION:
#Sta/Elev= 30
  4928.3  618.56  4948.3  615.83  4963.3  612.86  4973.3  611.65  4983.3  610.94
  4988.3  610.14  4992.2  605.54  4993.7  602.54  5006.2  602.54  5007.7  605.54
  5010.6  606.65  5015.6  609.07  5020.6  610.47  5025.6  611.23  5040.6  611.23
  5045.6  610.91  5055.6  610.99  5065.6  612.69  5070.6  613.14  5090.6  613.47
  5095.6  614.12  5100.6   614.4  5120.6  615.01  5135.6  614.72  5150.6  616.14
  5155.6  616.92  5160.6   617.4  5165.6  617.74  5170.6  617.73  5180.6  618.74
#Mann= 3 , 1 , 0
 4928.30    0.11       0  4992.2    0.05       0  5007.7    0.15       0
Bank Sta=4992.20,5007.70
Exp/Cntr=0.3,0.1

Type RM Length L Ch R = 1 ,12583.6,583.6,583.6,583.6
XS GIS Cut Line= 3
      1856142.57       756877.02      1856151.24       756722.63
      1856189.55       756536.57
BEGIN DESCRIPTION:
Greenbriar Creek 25.0
END DESCRIPTION:
#Sta/Elev= 30
  4841.2   617.2  4851.2  615.96  4861.2  614.53  4866.2  613.98  4896.2  612.67
  4951.2   609.7  4976.2  608.95  4981.2  608.38  4986.2  607.68  4991.2  606.72
  4992.2   603.9  4993.7   600.9  5006.2   600.9  5007.7   603.9  5010.8  608.37
  5015.8  609.35  5020.8   610.1  5025.8  610.49  5035.8  610.79  5060.8  610.21
  5070.8  610.37  5090.8  611.56  5110.8  612.24  5125.8  613.81  5130.8  613.75
  5155.8     615  5160.8  615.46  5170.8  615.38  5175.8  615.67  5185.8  616.96
#Mann= 3 , 1 , 0
 4841.20    0.11       0  4992.2    0.05       0  5007.7    0.15       0
Bank Sta=4992.20,5007.70
Exp/Cntr=0.3,0.1

Type RM Length L Ch R = 1 ,12000.0,500,500,500
XS GIS Cut Line= 3
      1856468.90       756539.63      1856387.73       756490.08
      1856351.34       756430.28
BEGIN DESCRIPTION:
Greenbriar Creek 24.0
END DESCRIPTION:
#Sta/Elev= 19
  4904.9  613.64  4924.9  611.61  4934.9     611  4944.9  610.08  4964.9  608.91
  4974.9  608.47  4984.9  607.63  4989.9  606.26  4992.2  603.11  4993.7  600.11
  5006.2  600.11  5007.7  603.11    5010  606.63    5020  607.66    5030  608.52
    5035  609.42    5050  611.41    5055  612.39    5070  614.44
#Mann= 3 , 1 , 0
 4904.90    0.11       0  4992.2    0.05       0  5007.7    0.15       0
Bank Sta=4992.20,5007.70
Exp/Cntr=0.3,0.1

Type RM Length L Ch R = 1 ,11500.0,500,500,500
XS GIS Cut Line= 3
      1856768.80       756258.81      1856743.69       756196.79
      1856613.29       756161.85
BEGIN DESCRIPTION:
Greenbriar Creek 23.0
END DESCRIPTION:
#Sta/Elev= 27
  4933.1  611.08  4938.1   610.5  4958.1  607.26  4973.1  605.28  4978.1  604.82
  4983.1  603.58  4988.1  602.17  4992.3   599.5  4993.8   596.5  5006.3   596.5
  5007.8   599.5    5025   603.2    5030  603.09    5035  602.68    5040  602.48
    5065  603.46    5080  604.86    5090  606.07    5095  606.19    5100  606.77
    5105  607.57    5110   607.9    5115  608.07    5120  608.54    5125  609.98
    5130  610.88    5135   611.6
#Mann= 3 , 1 , 0
 4933.10    0.11       0  4992.3    0.05       0  5007.8    0.15       0
Bank Sta=4992.30,5007.80
Exp/Cntr=0.3,0.1

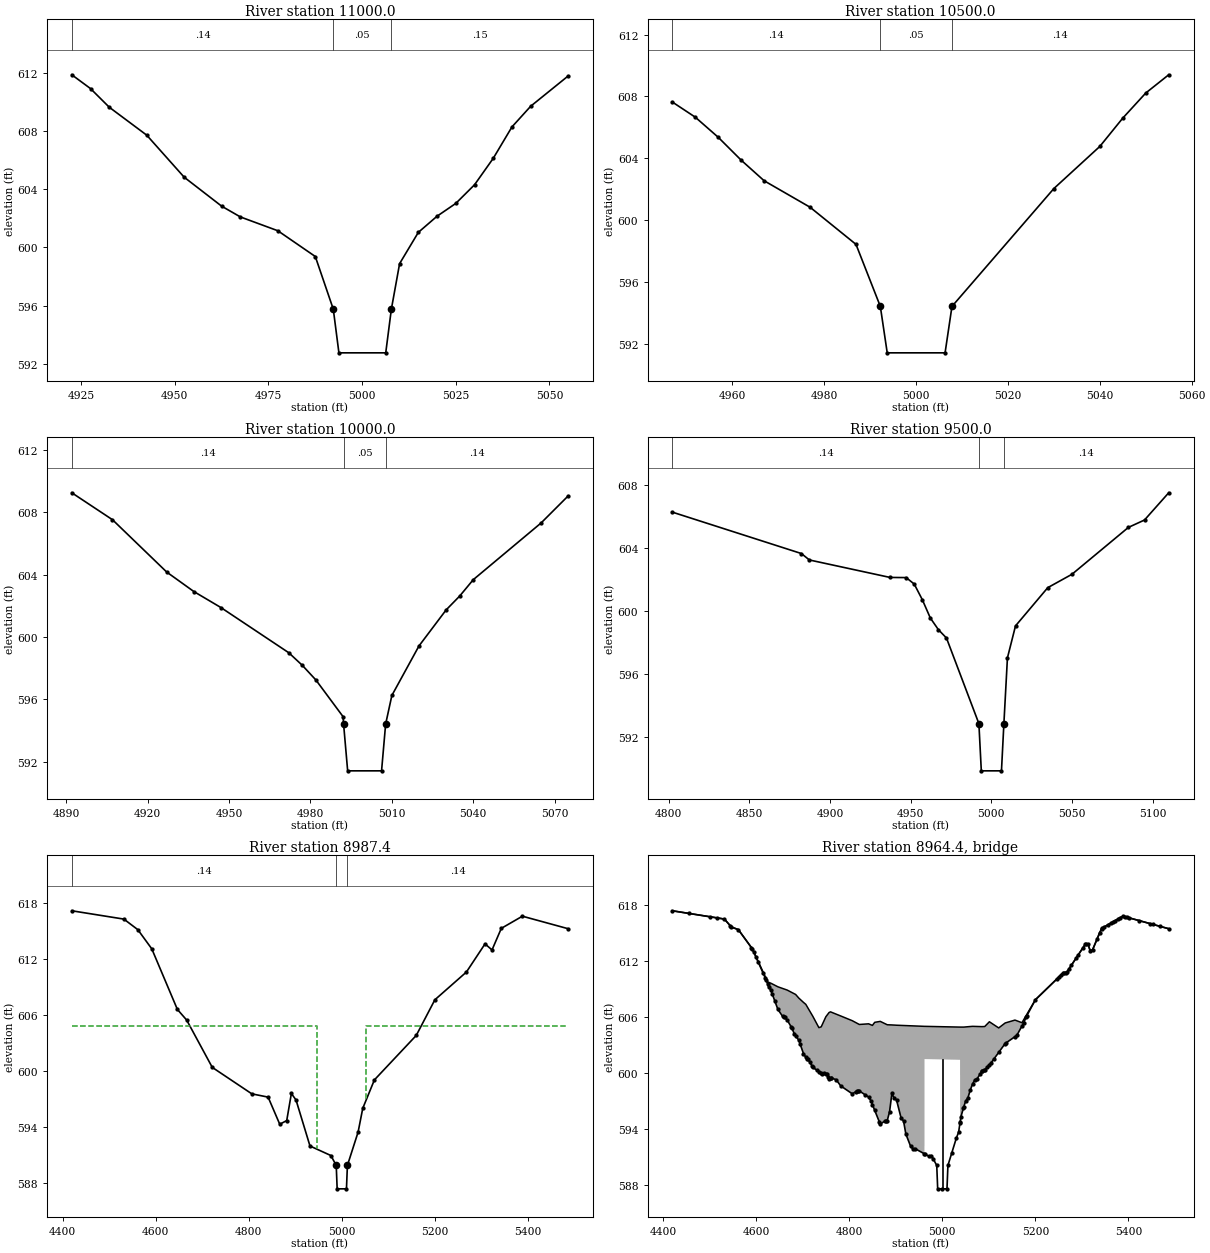
Type RM Length L Ch R = 1 ,11000.0,500,500,500
XS GIS Cut Line= 3
      1856567.50       755813.97      1856491.00       755826.39
      1856437.09       755837.29
BEGIN DESCRIPTION:
Greenbriar Creek 22.0
END DESCRIPTION:
#Sta/Elev= 22
  4922.5  611.87  4927.5  610.92  4932.5  609.64  4942.5  607.72  4952.5  604.83
  4962.5  602.84  4967.5   602.1  4977.5  601.15  4987.5  599.38  4992.3  595.76
  4993.8  592.76  5006.3  592.76  5007.8  595.76    5010  598.89    5015  601.04
    5020  602.15    5025  603.03    5030  604.31    5035  606.13    5040  608.29
    5045  609.71    5055  611.79
#Mann= 3 , 1 , 0
 4922.50    0.14       0  4992.3    0.05       0  5007.8    0.15       0
Bank Sta=4992.30,5007.80
Exp/Cntr=0.3,0.1

Type RM Length L Ch R = 1 ,10500.0,500,500,500
XS GIS Cut Line= 3
      1856288.16       755388.16      1856238.82       755407.80
      1856187.94       755428.67
BEGIN DESCRIPTION:
Greenbriar Creek 21.0
END DESCRIPTION:
#Sta/Elev= 16
  4946.9  607.64  4951.9  606.66  4956.9  605.36  4961.9  603.88  4966.9  602.55
  4976.9  600.84  4986.9  598.44  4992.2  594.43  4993.7  591.43  5006.3  591.43
  5007.8  594.43    5030  602.05    5040  604.77    5045   606.6    5050  608.22
    5055   609.4
#Mann= 3 , 1 , 0
 4946.90    0.14       0  4992.2    0.05       0  5007.8    0.14       0
Bank Sta=4992.20,5007.80
Exp/Cntr=0.3,0.1

Type RM Length L Ch R = 1 ,10000.0,500,500,500
XS GIS Cut Line= 3
      1856040.03       755025.15      1855932.03       755025.60
      1855862.47       755053.64
BEGIN DESCRIPTION:
Greenbriar Creek 20.0
END DESCRIPTION:
#Sta/Elev= 20
    4892  609.26    4907  607.53    4927  604.17    4937  602.92    4947  601.89
    4972  598.99    4977  598.18    4982  597.24    4992  594.89  4992.2  594.41
  4993.7  591.41  5006.2  591.41  5007.7  594.41    5010  596.25    5020  599.43
    5030  601.74    5035  602.63    5040  603.68    5065  607.32    5075  609.06
#Mann= 3 , 1 , 0
 4892.00    0.14       0  4992.2    0.05       0  5007.7    0.14       0
Bank Sta=4992.20,5007.70
Exp/Cntr=0.3,0.1

Type RM Length L Ch R = 1 ,9500.0,512.6,512.6,512.6
XS GIS Cut Line= 3
      1856142.71       754640.26      1855963.71       754556.08
      1855855.18       754538.21
BEGIN DESCRIPTION:
Greenbriar Creek 19.0
END DESCRIPTION:
#Sta/Elev= 21
  4802.2  606.28  4882.2  603.65  4887.2  603.24  4937.2  602.13  4947.2  602.12
  4952.2  601.71  4957.2  600.72  4962.2  599.55  4967.2  598.81  4972.2  598.28
  4992.3  592.84  4993.8  589.84  5006.3  589.84  5007.8  592.84    5010  597.02
    5015  599.05    5035  601.48    5050  602.33    5085  605.31    5095  605.78
    5110  607.51
#Mann= 3 , 1 , 0
 4802.20    0.14       0  4992.3    0.05       0  5007.8    0.14       0
Bank Sta=4992.30,5007.80
Exp/Cntr=0.5,0.3

Type RM Length L Ch R = 1 ,8987.4,46,46,46
XS GIS Cut Line= 4
      1856749.41       754123.67      1856168.57       754148.21
      1855898.78       754174.53      1855694.09       754238.20
BEGIN DESCRIPTION:
Upstream Section of Bridge/Culvert/Weir
END DESCRIPTION:
#Sta/Elev= 30
  4419.7  617.13  4531.6  616.24  4561.6  615.11  4591.6  613.06  4646.6  606.58
  4666.6  605.44  4721.6  600.38  4806.6  597.55  4841.6   597.2  4866.6   594.3
  4881.6  594.69  4891.6  597.59  4901.6  596.89  4931.6  591.97  4976.6  590.95
    4988  589.89    4990  587.39    5010  587.39    5012  589.89    5035  593.46
    5045     596    5070  599.04    5160   603.8    5200  607.61  5267.8  610.58
  5307.8  613.59  5322.8  612.94  5342.8  615.25  5388.1  616.55  5486.5  615.21
#Mann= 3 , 1 , 0
 4419.70    0.14       0    4988    0.05       0    5012    0.14       0
#XS Ineff= 2 , 0
       0    4947  604.84    5053       0  604.84
Bank Sta=4988.00,5012.00
Exp/Cntr=0.5,0.3

Type RM Length L Ch R = 3 ,8964.4,,,
BEGIN DESCRIPTION:
Silk Hope Liberty
Structure ID: NCF-0280
Approximate Survey Structure
END DESCRIPTION:
Bridge Culvert--1,0,-1,-1, 0
Deck Dist Width WeirC Skew NumUp NumDn MinLoCord MaxHiCord MaxSubmerge Is_Ogee
10,26,2.6,, 60, 60,,,0.95,0,1,1,,
  4419.7  4531.6  4546.6  4561.6  4591.6  4624.7  4631.6  4646.6  4666.6  4684.7
  4691.6  4701.6  4706.6  4721.6  4734.7  4739.7  4749.7  4756.6  4759.7  4771.6
  4781.6  4806.6  4821.6  4841.6  4849.7  4854.7  4866.6  4881.6  4886.6  4891.6
  4901.6  4911.6  4916.6  4921.6  4931.6 4961.61  4961.7 5038.09  5038.2    5040
  5046.1    5055    5065    5085  5091.1  5101.1  5121.1    5135  5156.1  5171.1
    5200    5260  5267.8  5307.8  5312.8  5317.8  5322.8  5342.8  5388.1  5486.5
  617.34  616.46  615.61  615.33  613.28  609.73  609.59  609.21  608.86  608.39
     608  607.54  607.33  606.06  604.84  604.93  606.01  606.46  606.53  606.29
  606.09  605.58  605.18  605.25  605.08  605.41  605.51  605.15  605.14  605.13
   605.1  605.08  605.07  605.06  605.04  604.98  604.98   604.9   604.9   604.9
   604.9  604.94  604.98  604.95  604.96  605.47  604.81  605.34  605.65  605.37
  607.83  610.72   610.8  613.81  613.81  613.06  613.16  615.47  616.77  615.42
  617.34  616.45   615.6  615.32  613.27  609.49  608.83  606.79  605.65  603.98
  603.48  602.06  601.66  600.59  600.14  599.97  599.91  599.36  599.42  599.28
  598.61  597.76  598.07  597.41  596.61  595.99  594.51   594.9  595.85   597.8
   597.1  595.13  594.87  593.46  592.18  591.34  601.48   601.4  594.72  595.31
  596.38  597.34  598.82  600.18  600.32  600.87  602.19  603.14  603.87  605.01
  607.82  610.71  610.79   613.8   613.8  613.05  613.15  615.46  616.76  615.42
  4419.7  4531.6  4546.6  4561.6  4591.6  4624.7  4631.6  4646.6  4666.6  4684.7
  4691.6  4701.6  4706.6  4721.6  4734.7  4739.7  4749.7  4756.6  4759.7  4771.6
  4781.6  4806.6  4821.6  4841.6  4849.7  4854.7  4866.6  4881.6  4886.6  4891.6
  4901.6  4911.6  4916.6  4921.6  4931.6 4961.61  4961.7 5038.09  5038.2    5040
  5046.1    5055    5065    5085  5091.1  5101.1  5121.1    5135  5156.1  5171.1
    5200    5260  5267.8  5307.8  5312.8  5317.8  5322.8  5342.8  5388.1  5486.5
  617.34  616.46  615.61  615.33  613.28  609.73  609.59  609.21  608.86  608.39
     608  607.54  607.33  606.06  604.84  604.93  606.01  606.46  606.53  606.29
  606.09  605.58  605.18  605.25  605.08  605.41  605.51  605.15  605.14  605.13
   605.1  605.08  605.07  605.06  605.04  604.98  604.98   604.9   604.9   604.9
   604.9  604.94  604.98  604.95  604.96  605.47  604.81  605.34  605.65  605.37
  607.83  610.72   610.8  613.81  613.81  613.06  613.16  615.47  616.77  615.42
  617.09   616.2  615.35  615.07  613.02  609.24  608.58  606.54   605.4  603.73
  603.23  601.81  601.41  600.34  599.89  599.72  599.66  599.11  599.17  599.03
  598.36  597.51  597.82  597.16  596.36  595.74  594.26  594.65   595.6  597.55
  596.85  594.88  594.62  593.21  591.93  591.09  601.23  601.15  594.47  595.06
  596.13  597.09  598.57  599.93  600.07  600.62  601.94  602.89  603.62  604.76
  607.57  610.46  610.54  613.55  613.55   612.8   612.9  615.21  616.51  615.17
Pier Skew, UpSta & Num, DnSta & Num=,5000.0, 2 ,5000.0, 2 , 0 , 0 , 0 ,,
       2       2
   586.6   602.4
       2       2
  586.35  602.15
Abutment Skew #Up #Dn=, 2 , 2
 4961.50 4980.00
  601.48  590.84
 4961.50 4980.00
  601.23  590.59
Abutment Skew #Up #Dn=, 2 , 2
 5020.00 5038.29
  591.39  601.40
 5020.00 5038.29
  591.14  601.15
BR Coef= 1 , 1 , 0 ,1.25, 0 ,,,0.8,0,2,0,
Wspro=,,,, 1 ,,,, 0 ,,,, 0 ,,,,-1 ,-1 ,-1 , 0 , 0 , 0 , 0 , 0
BC Design=,, 0 ,, 0 ,,,,,,
BR U #Sta/Elev= 157
  4419.7  617.34  4454.7  617.06  4499.7   616.7  4514.7  616.58  4531.6  616.45
  4544.7  615.71  4546.6   615.6  4561.6  615.32  4589.7   613.4  4591.6  613.27
  4594.7  612.92  4599.7  612.37  4604.7  611.81  4614.7  610.69  4619.7  610.13
  4621.6  609.92  4624.7  609.49  4626.6  609.23  4631.6  608.83  4634.7  608.41
  4639.7  607.73  4646.6  606.79  4656.6  606.06  4659.7  605.98  4661.6  605.93
  4666.6  605.65  4674.7  604.96  4676.6   604.8  4681.6  604.21  4684.7  603.98
  4691.6  603.48  4694.7  603.04  4701.6  602.06  4706.6  601.66  4709.7  601.54
  4711.6  601.47  4714.7   601.2  4719.7  600.76  4721.6  600.59  4729.7  600.31
  4734.7  600.14  4739.7  599.97  4741.6  599.91  4746.6  599.96  4749.7  599.91
  4751.6  599.88  4754.7  599.56  4756.6  599.36  4759.7  599.42  4761.6  599.45
  4771.6  599.28  4781.6  598.61  4806.6  597.76  4814.7  598.01  4816.6  598.07
  4819.7  598.07  4821.6  598.07  4834.7  597.64  4841.6  597.41  4846.6     597
  4849.7  596.61  4854.7  595.99  4864.7  594.75  4866.6  594.51  4876.6  594.86
  4879.7  594.88  4881.6   594.9  4886.6  595.85  4891.6   597.8  4896.6  597.29
  4901.6   597.1  4911.6  595.13  4916.6  594.87  4921.6  593.46  4931.6  592.18
  4936.6  591.89  4941.6  591.89 4961.61  591.34  4961.7  591.34  4971.6  591.07
  4976.6  591.16    4980  590.84    4988   590.1    4990   587.6    5000   587.6
    5010   587.6    5012   590.1    5020  591.39    5030  593.01    5035  593.67
 5038.09  594.68  5038.2  594.72    5040  595.31    5045  596.21  5046.1  596.38
    5050  596.97    5055  597.34    5060  598.15    5065  598.82    5070  599.25
    5075  599.39  5081.1  599.87    5085  600.18  5086.1   600.2    5090  600.26
  5091.1  600.32  5096.1   600.6  5101.1  600.87    5105  601.09  5111.1  601.51
  5121.1  602.19    5135  603.14  5136.1  603.18  5156.1  603.87    5160  604.01
  5171.1  605.01    5175  605.36    5180  605.97  5181.1  606.07    5200  607.82
  5246.1  610.04  5251.1  610.28  5256.1  610.52    5260  610.71  5261.1   610.7
    5265  610.67  5267.8  610.79  5272.1  611.11  5277.1  611.49  5287.1  612.24
  5292.1  612.62  5302.1  613.37  5307.1  613.75  5307.8   613.8  5312.8   613.8
  5317.8  613.05  5322.8  613.15  5332.1  614.28  5337.8  614.98  5342.1  615.39
  5342.8  615.46  5347.1  615.58  5357.1  615.87  5362.1  616.01  5367.1  616.16
  5372.1   616.3  5377.1  616.44  5382.1  616.59  5388.1  616.76  5392.1  616.71
  5397.1  616.64  5402.1  616.57  5422.1   616.3  5447.1  615.96  5452.1  615.89
  5467.1  615.68  5486.5  615.42
BR U #Mann= 3
 4419.70    0.14    4988    0.05    5012    0.14
BR U Banks=4988.00,5012.00
BR D #Sta/Elev= 157
  4419.7  617.09  4454.7  616.81  4499.7  616.45  4514.7  616.33  4531.6   616.2
  4544.7  615.46  4546.6  615.35  4561.6  615.07  4589.7  613.15  4591.6  613.02
  4594.7  612.67  4599.7  612.12  4604.7  611.56  4614.7  610.44  4619.7  609.88
  4621.6  609.67  4624.7  609.24  4626.6  608.98  4631.6  608.58  4634.7  608.16
  4639.7  607.48  4646.6  606.54  4656.6  605.81  4659.7  605.73  4661.6  605.68
  4666.6   605.4  4674.7  604.71  4676.6  604.55  4681.6  603.96  4684.7  603.73
  4691.6  603.23  4694.7  602.79  4701.6  601.81  4706.6  601.41  4709.7  601.29
  4711.6  601.22  4714.7  600.95  4719.7  600.51  4721.6  600.34  4729.7  600.06
  4734.7  599.89  4739.7  599.72  4741.6  599.66  4746.6  599.71  4749.7  599.66
  4751.6  599.63  4754.7  599.31  4756.6  599.11  4759.7  599.17  4761.6   599.2
  4771.6  599.03  4781.6  598.36  4806.6  597.51  4814.7  597.76  4816.6  597.82
  4819.7  597.82  4821.6  597.82  4834.7  597.39  4841.6  597.16  4846.6  596.75
  4849.7  596.36  4854.7  595.74  4864.7   594.5  4866.6  594.26  4876.6  594.61
  4879.7  594.63  4881.6  594.65  4886.6   595.6  4891.6  597.55  4896.6  597.04
  4901.6  596.85  4911.6  594.88  4916.6  594.62  4921.6  593.21  4931.6  591.93
  4936.6  591.64  4941.6  591.64 4961.61  591.09  4961.7  591.09  4971.6  590.82
  4976.6  590.91    4980  590.59    4988  589.85    4990  587.35    5000  587.35
    5010  587.35    5012  589.85    5020  591.14    5030  592.76    5035  593.42
 5038.09  594.43  5038.2  594.47    5040  595.06    5045  595.96  5046.1  596.13
    5050  596.72    5055  597.09    5060   597.9    5065  598.57    5070     599
    5075  599.14  5081.1  599.62    5085  599.93  5086.1  599.95    5090  600.01
  5091.1  600.07  5096.1  600.35  5101.1  600.62    5105  600.84  5111.1  601.26
  5121.1  601.94    5135  602.89  5136.1  602.93  5156.1  603.62    5160  603.76
  5171.1  604.76    5175  605.11    5180  605.72  5181.1  605.82    5200  607.57
  5246.1  609.79  5251.1  610.03  5256.1  610.27    5260  610.46  5261.1  610.45
    5265  610.42  5267.8  610.54  5272.1  610.86  5277.1  611.24  5287.1  611.99
  5292.1  612.37  5302.1  613.12  5307.1   613.5  5307.8  613.55  5312.8  613.55
  5317.8   612.8  5322.8   612.9  5332.1  614.03  5337.8  614.73  5342.1  615.14
  5342.8  615.21  5347.1  615.33  5357.1  615.62  5362.1  615.76  5367.1  615.91
  5372.1  616.05  5377.1  616.19  5382.1  616.34  5388.1  616.51  5392.1  616.46
  5397.1  616.39  5402.1  616.32  5422.1  616.05  5447.1  615.71  5452.1  615.64
  5467.1  615.43  5486.5  615.17
BR D #Mann= 3
 4419.70    0.14    4988    0.05    5012    0.14
BR D Banks=4988.00,5012.00

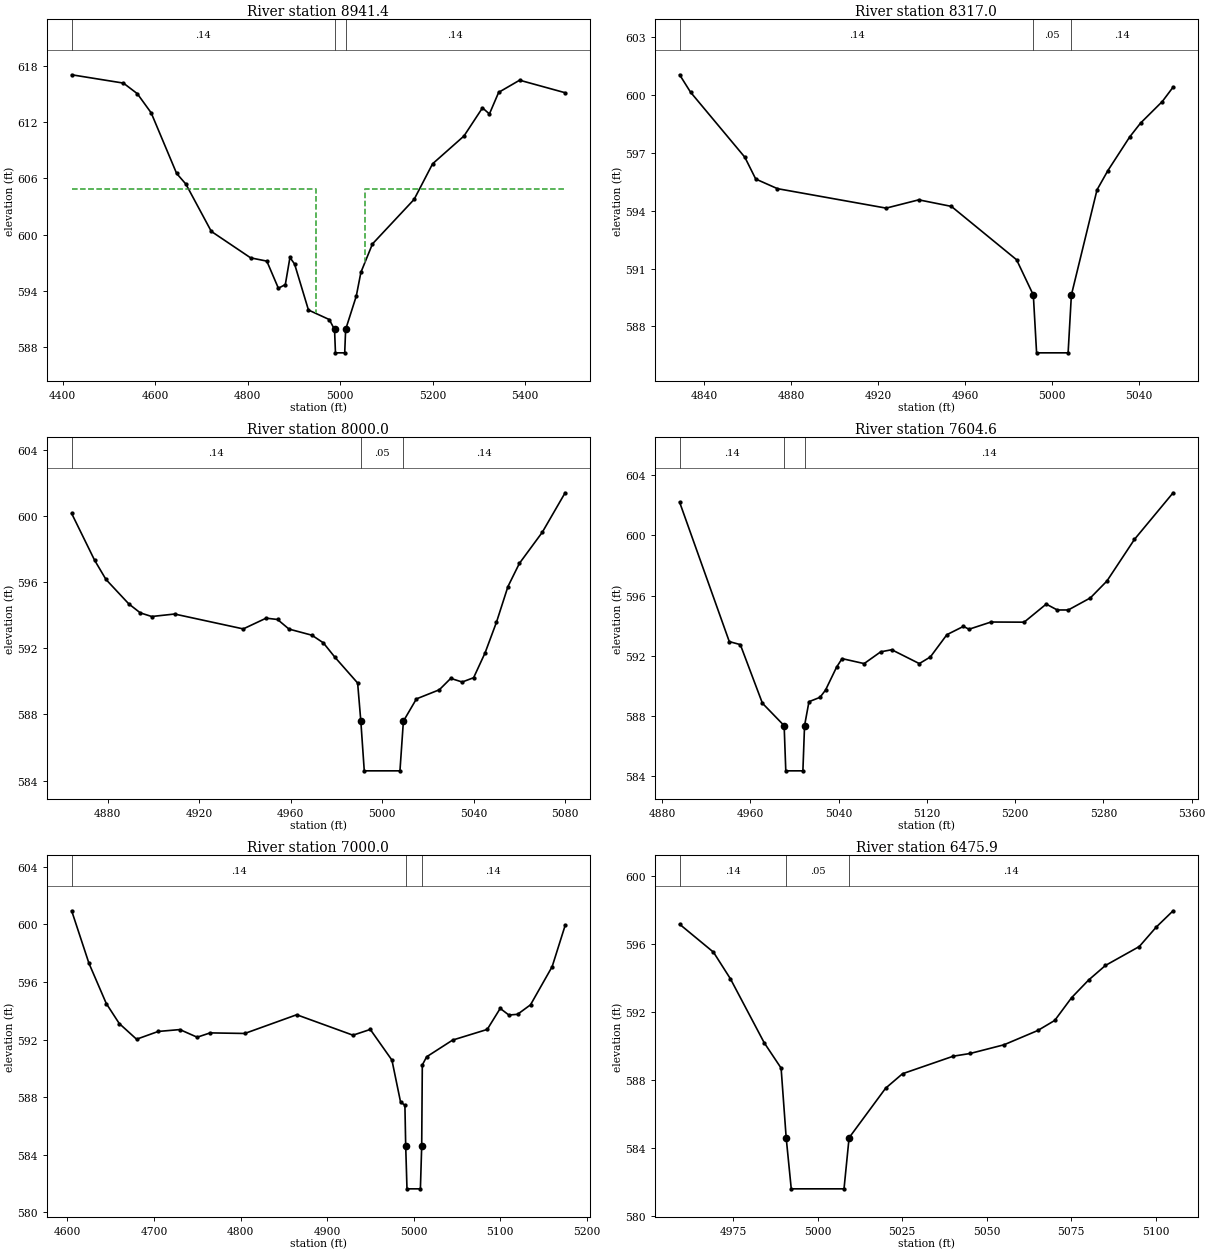
Type RM Length L Ch R = 1 ,8941.4,624.4,624.4,624.4
XS GIS Cut Line= 4
      1856747.47       754077.71      1856166.63       754102.25
      1855896.84       754128.57      1855692.15       754192.24
BEGIN DESCRIPTION:
Downstream Section of Bridge/Culvert/Weir
END DESCRIPTION:
#Sta/Elev= 30
  4419.7  617.09  4531.6   616.2  4561.6  615.07  4591.6  613.02  4646.6  606.54
  4666.6   605.4  4721.6  600.34  4806.6  597.51  4841.6  597.16  4866.6  594.26
  4881.6  594.65  4891.6  597.55  4901.6  596.85  4931.6  591.93  4976.6  590.91
    4988  589.85    4990  587.35    5010  587.35    5012  589.85    5035  593.42
    5045  595.96    5070     599    5160  603.76    5200  607.57  5267.8  610.54
  5307.8  613.55  5322.8   612.9  5342.8  615.21  5388.1  616.51  5486.5  615.17
#Mann= 3 , 1 , 0
 4419.70    0.14       0    4988    0.05       0    5012    0.14       0
#XS Ineff= 2 , 0
       0    4947  604.84    5053       0  604.84
Bank Sta=4988.00,5012.00
Exp/Cntr=0.5,0.3

Type RM Length L Ch R = 1 ,8317.0,317,317,317
XS GIS Cut Line= 3
      1856144.55       753714.05      1856025.90       753845.38
      1855976.09       753840.90
BEGIN DESCRIPTION:
Greenbriar Creek 17.0
END DESCRIPTION:
#Sta/Elev= 19
  4828.6  601.06  4833.6  600.16  4858.6  596.78  4863.6  595.65  4873.6  595.15
  4923.6  594.14  4938.6  594.57  4953.6  594.23  4983.6  591.46  4991.3  589.63
  4992.8  586.63  5007.3  586.63  5008.8  589.63  5020.6  595.09  5025.6  596.09
  5035.6  597.83  5040.6  598.55  5050.6  599.67  5055.6  600.42
#Mann= 3 , 1 , 0
 4828.60    0.14       0  4991.3    0.05       0  5008.8    0.14       0
Bank Sta=4991.30,5008.80
Exp/Cntr=0.3,0.1

Type RM Length L Ch R = 1 ,8000.0,395.4,395.4,395.4
XS GIS Cut Line= 3
      1856089.29       753560.65      1855954.67       753577.71
      1855876.13       753592.94
BEGIN DESCRIPTION:
Greenbriar Creek 16.0
END DESCRIPTION:
#Sta/Elev= 30
  4864.3  600.15  4874.3  597.33  4879.3  596.16  4889.3  594.68  4894.3  594.14
  4899.3  593.92  4909.3  594.07  4939.3  593.17  4949.3  593.82  4954.3  593.74
  4959.3  593.16  4969.3  592.79  4974.3  592.33  4979.3  591.47  4989.3   589.9
  4990.7  587.59  4992.2  584.59  5007.8  584.59  5009.3  587.59    5015  588.94
    5025  589.49    5030  590.18    5035  589.96    5040  590.22    5045  591.72
    5050  593.58    5055  595.73    5060  597.13    5070  599.01    5080   601.4
#Mann= 3 , 1 , 0
 4864.30    0.14       0  4990.7    0.05       0  5009.3    0.14       0
Bank Sta=4990.70,5009.30
Exp/Cntr=0.3,0.1

Type RM Length L Ch R = 1 ,7604.6,604.6,604.6,604.6
XS GIS Cut Line= 3
      1856096.10       753277.94      1856008.08       753236.72
      1855667.35       753316.77
BEGIN DESCRIPTION:
Greenbriar Creek 15.0
END DESCRIPTION:
#Sta/Elev= 30
    4896  602.19    4941  592.94    4951  592.74    4971  588.85  4990.7  587.36
  4992.2  584.36  5007.7  584.36  5009.2  587.36  5013.2  588.95  5023.2  589.24
  5028.2  589.72  5038.2  591.24  5043.2  591.81  5063.2  591.48  5078.2  592.26
  5088.2   592.4  5113.2  591.48  5123.2  591.92  5138.2   593.4  5153.2  593.95
  5158.2  593.76  5178.2  594.24  5208.2  594.23  5228.2  595.43  5238.2  595.04
  5248.2  595.04  5268.2  595.84  5283.2  596.96  5308.2  599.73  5343.2  602.82
#Mann= 3 , 1 , 0
 4896.00    0.14       0  4990.7    0.05       0  5009.2    0.14       0
Bank Sta=4990.70,5009.20
Exp/Cntr=0.3,0.1

Type RM Length L Ch R = 1 ,7000.0,524.1,524.1,524.1
XS GIS Cut Line= 3
      1856271.78       752974.33      1855920.87       752792.76
      1855746.13       752783.13
BEGIN DESCRIPTION:
Greenbriar Creek 14.0
END DESCRIPTION:
#Sta/Elev= 30
  4604.9  600.94  4624.9  597.29  4644.9   594.5  4659.9  593.11  4679.9  592.02
  4704.9  592.56  4729.9  592.69  4749.9  592.16  4764.9  592.46  4804.9  592.42
  4864.9  593.72  4929.9   592.3  4949.9   592.7  4974.9  590.57  4984.9  587.65
  4989.9  587.44  4990.8  584.63  4992.3  581.63  5007.8  581.63  5009.3  584.63
    5010  590.23    5015   590.8    5045  591.96    5085   592.7    5100  594.16
    5110   593.7    5120  593.75    5135  594.41    5160  597.06    5175  599.92
#Mann= 3 , 1 , 0
 4604.90    0.14       0  4990.8    0.05       0  5009.3    0.14       0
Bank Sta=4990.80,5009.30
Exp/Cntr=0.3,0.1

Type RM Length L Ch R = 1 ,6475.9,418.4,418.4,418.4
XS GIS Cut Line= 3
      1856276.61       752755.21      1856247.47       752719.74
      1856179.13       752646.74
BEGIN DESCRIPTION:
Greenbriar Creek 13.0
END DESCRIPTION:
#Sta/Elev= 22
  4959.2  597.15  4969.2  595.51  4974.2  593.95  4984.2  590.19  4989.2   588.7
  4990.7  584.61  4992.2  581.61  5007.8  581.61  5009.3  584.61  5020.1  587.52
  5025.1  588.37  5040.1   589.4  5045.1  589.56  5055.1  590.07  5065.1  590.91
  5070.1   591.5  5075.1  592.84  5080.1  593.87  5085.1  594.73  5095.1  595.84
  5100.1  596.98  5105.1  597.94
#Mann= 3 , 1 , 0
 4959.20    0.14       0  4990.7    0.05       0  5009.3    0.14       0
Bank Sta=4990.70,5009.30
Exp/Cntr=0.3,0.1

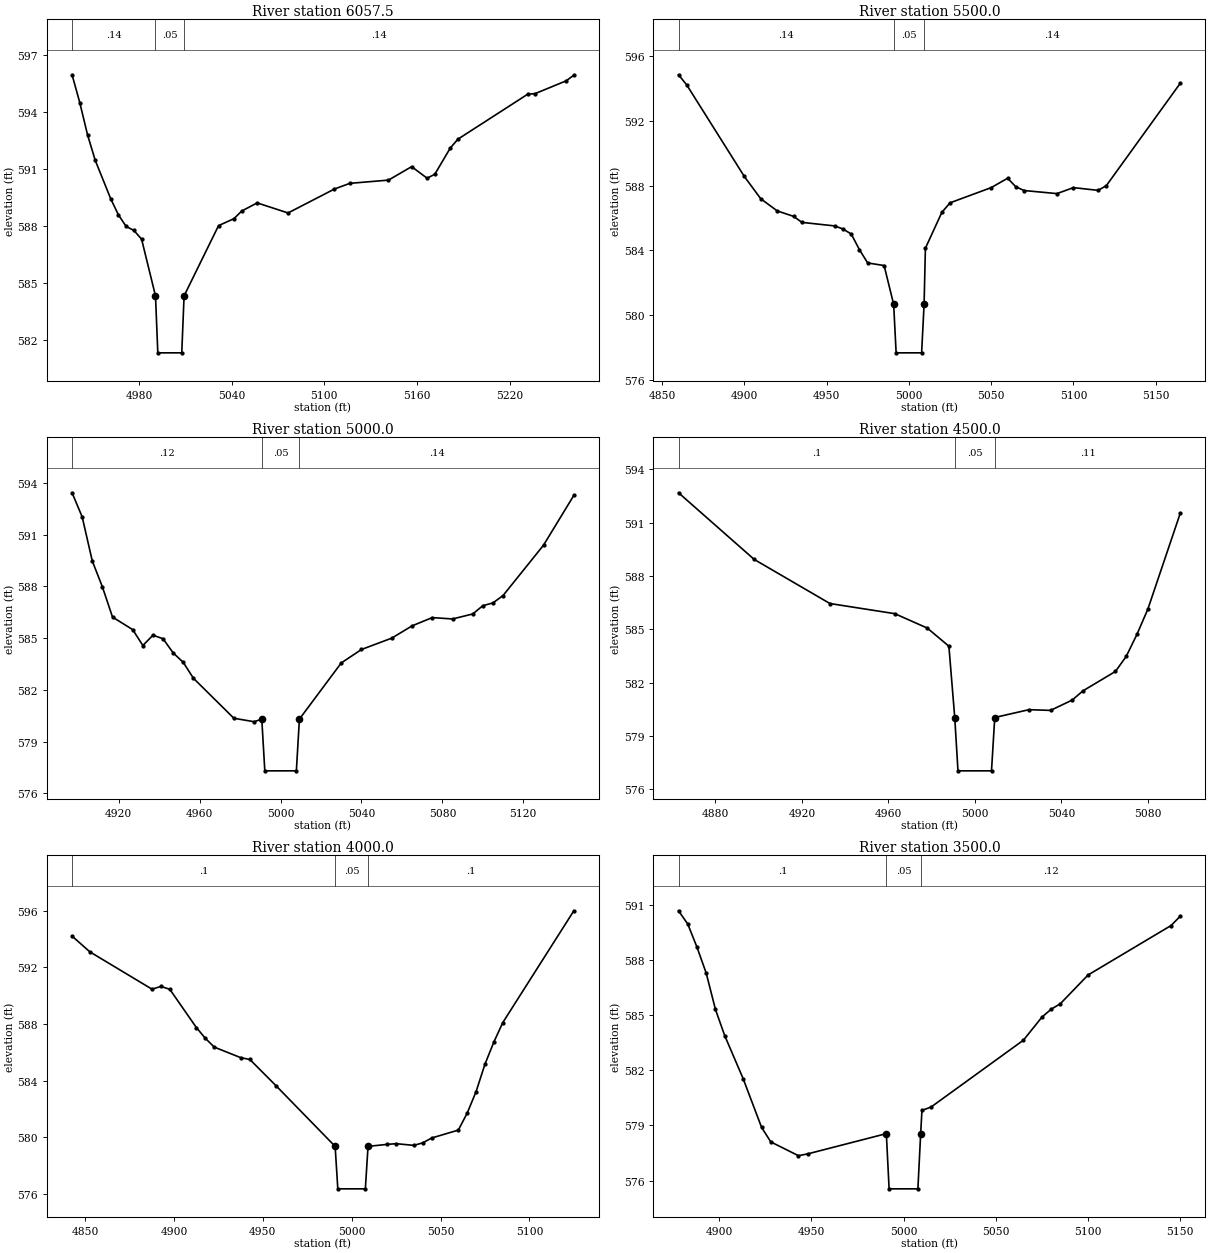
Type RM Length L Ch R = 1 ,6057.5,557.5,557.5,557.5
XS GIS Cut Line= 3
      1856541.93       752435.60      1856486.86       752401.40
      1856227.39       752417.62
BEGIN DESCRIPTION:
Greenbriar Creek 12.0
END DESCRIPTION:
#Sta/Elev= 30
  4936.7  595.98  4941.7  594.51  4946.7  592.82  4951.7  591.47  4961.7  589.45
  4966.7   588.6  4971.7  587.99  4976.7  587.78  4981.7  587.32  4990.7  584.33
  4992.2  581.33  5007.7  581.33  5009.2  584.33  5031.5  588.03  5041.5   588.4
  5046.5   588.8  5056.5  589.23  5076.5   588.7  5106.5  589.96  5116.5  590.26
  5141.5  590.43  5156.5  591.14  5166.5  590.53  5171.5  590.74  5181.5  592.12
  5186.5  592.59  5231.5  594.95  5236.5  594.99  5256.5  595.66  5261.5  595.96
#Mann= 3 , 1 , 0
 4936.70    0.14       0  4990.7    0.05       0  5009.2    0.14       0
Bank Sta=4990.70,5009.20
Exp/Cntr=0.3,0.1

Type RM Length L Ch R = 1 ,5500.0,500,500,500
XS GIS Cut Line= 3
      1856434.76       751989.81      1856306.60       752046.43
      1856158.27       752118.69
BEGIN DESCRIPTION:
Greenbriar Creek 11.0
END DESCRIPTION:
#Sta/Elev= 29
  4859.9  594.85  4864.9  594.22  4899.9  588.56  4909.9  587.18  4919.9  586.43
  4929.9  586.09  4934.9  585.72  4954.9   585.5  4959.9  585.31  4964.9     585
  4969.9  584.03  4974.9  583.21  4984.9  583.05  4990.7  580.65  4992.2  577.65
  5007.7  577.65  5009.2  580.65    5010  584.12    5020  586.34    5025  586.93
    5050  587.87    5060  588.45    5065  587.92    5070  587.69    5090   587.5
    5100  587.87    5115   587.7    5120  587.99    5165  594.33
#Mann= 3 , 1 , 0
 4859.90    0.14       0  4990.7    0.05       0  5009.2    0.14       0
Bank Sta=4990.70,5009.20
Exp/Cntr=0.3,0.1

Type RM Length L Ch R = 1 ,5000.0,500,500,500
XS GIS Cut Line= 3
      1856223.28       751584.79      1856121.05       751598.16
      1855976.36       751607.67
BEGIN DESCRIPTION:
Greenbriar Creek 10.0
END DESCRIPTION:
#Sta/Elev= 30
  4896.9  593.43  4901.9  592.03  4906.9  589.47  4911.9  587.97  4916.9  586.22
  4926.9  585.49  4931.9  584.57  4936.9  585.17  4941.9  584.96  4946.9  584.14
  4951.9  583.59  4956.9  582.67  4976.9  580.35  4986.9  580.15  4990.7   580.3
  4992.2   577.3  5007.8   577.3  5009.3   580.3    5030  583.56    5040  584.34
    5055     585    5065  585.71    5075  586.19    5085  586.11    5095   586.4
    5100  586.88    5105  587.04    5110  587.47    5130  590.39    5145  593.28
#Mann= 3 , 1 , 0
 4896.90    0.12       0  4990.7    0.05       0  5009.3    0.14       0
Bank Sta=4990.70,5009.30
Exp/Cntr=0.3,0.1

Type RM Length L Ch R = 1 ,4500.0,500,500,500
XS GIS Cut Line= 3
      1856340.06       751311.28      1856244.80       751212.82
      1856163.73       751163.29
BEGIN DESCRIPTION:
Greenbriar Creek 9.0
END DESCRIPTION:
#Sta/Elev= 19
    4863  592.68    4898  588.93    4933  586.45    4963  585.88    4978  585.07
    4988  584.05  4990.7  580.04  4992.2  577.04  5007.7  577.04  5009.2  580.04
    5025  580.48    5035  580.44    5045  581.02    5050  581.54    5065  582.63
    5070  583.48    5075  584.73    5080  586.14    5095  591.54
#Mann= 3 , 1 , 0
 4863.00     0.1       0  4990.7    0.05       0  5009.2    0.11       0
Bank Sta=4990.70,5009.20
Exp/Cntr=0.3,0.1

Type RM Length L Ch R = 1 ,4000.0,500,500,500
XS GIS Cut Line= 3
      1856706.77       751034.49      1856627.02       750898.90
      1856535.15       750814.14
BEGIN DESCRIPTION:
Greenbriar Creek 8.0
END DESCRIPTION:
#Sta/Elev= 27
  4842.7   594.2  4852.7  593.09  4887.7  590.45  4892.7  590.65  4897.7  590.44
  4912.7  587.73  4917.7  586.98  4922.7  586.36  4937.7  585.61  4942.7  585.49
  4957.7   583.6  4990.7  579.35  4992.2  576.35  5007.7  576.35  5009.2  579.35
    5020  579.49    5025  579.54    5035  579.42    5040   579.6    5045  579.94
    5060   580.5    5065   581.7    5070  583.22    5075  585.16    5080  586.72
    5085  588.09    5125  595.99
#Mann= 3 , 1 , 0
 4842.70     0.1       0  4990.7    0.05       0  5009.2     0.1       0
Bank Sta=4990.70,5009.20
Exp/Cntr=0.3,0.1

Type RM Length L Ch R = 1 ,3500.0,409.7,409.7,409.7
XS GIS Cut Line= 3
      1857119.46       750559.16      1856998.89       750577.14
      1856902.61       750462.12
BEGIN DESCRIPTION:
Greenbriar Creek 7.0
END DESCRIPTION:
#Sta/Elev= 24
  4878.1  590.66  4883.1  589.94  4888.1  588.68  4893.1  587.27  4898.1   585.3
  4903.1  583.88  4913.1  581.54  4923.1  578.89  4928.1   578.1  4943.1  577.35
  4948.1  577.45  4990.7  578.55  4992.2  575.55  5007.8  575.55  5009.3  578.55
    5010  579.81    5015     580    5065  583.63    5075  584.88    5080  585.31
    5085  585.61    5100  587.17    5145  589.86    5150  590.37
#Mann= 3 , 1 , 0
 4878.10     0.1       0  4990.7    0.05       0  5009.3    0.12       0
Bank Sta=4990.70,5009.30
Exp/Cntr=0.3,0.1