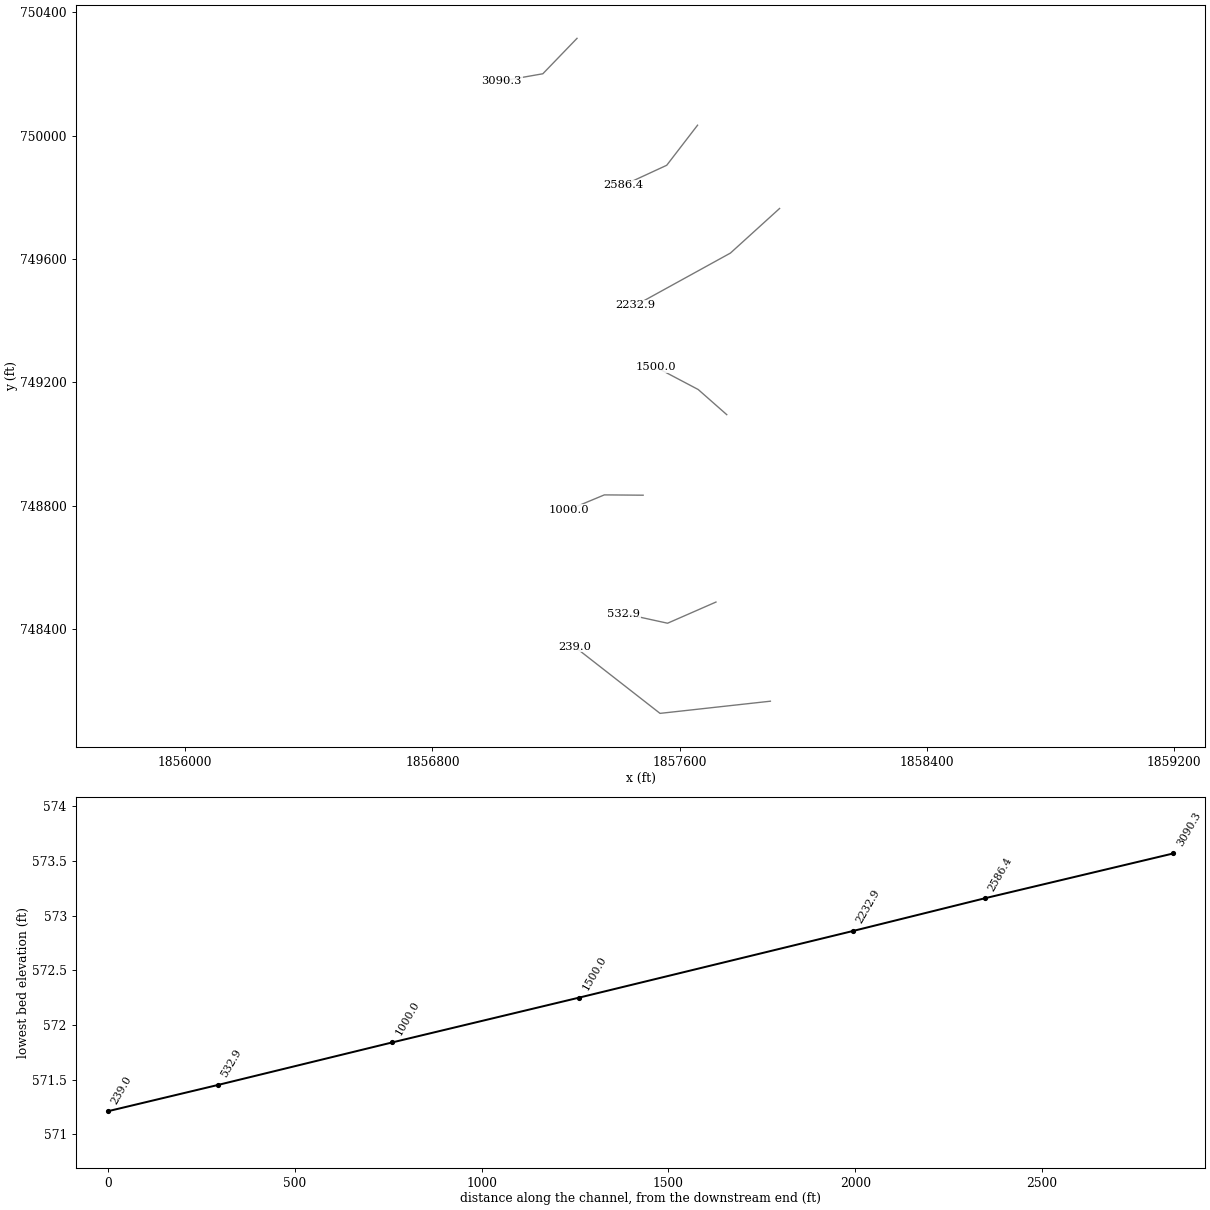
HEC-RAS study GREENBRIAR CREEK.PRJ: Greenbriar Creek

--- GREENBRIAR CREEK.g01 (geometry) --- (continued)

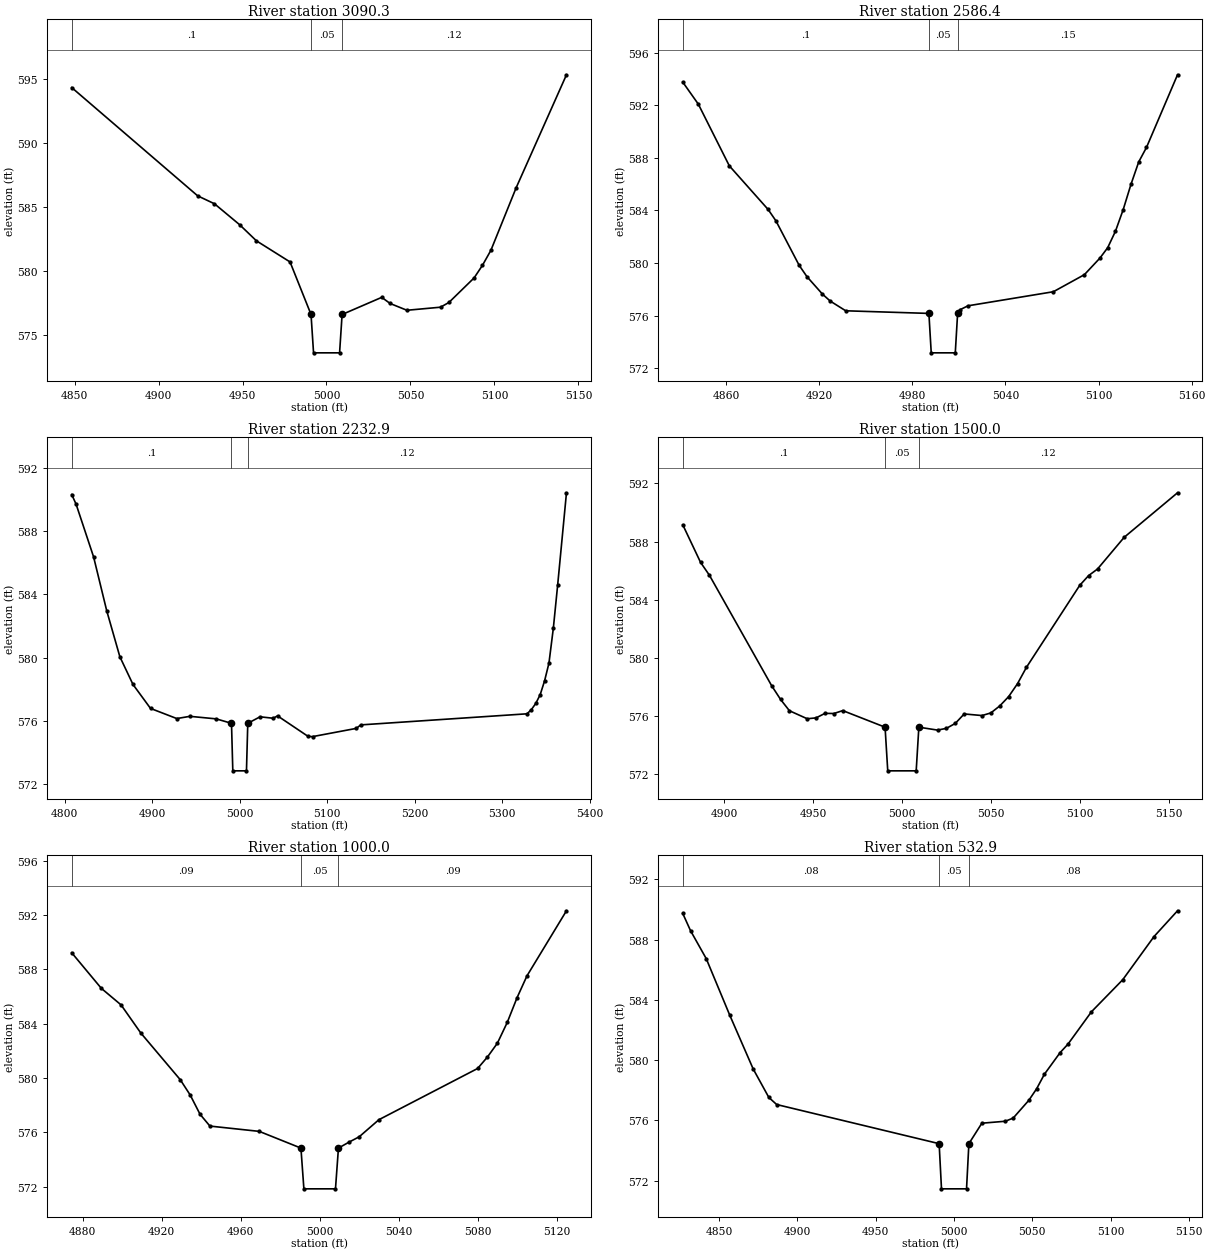
Type RM Length L Ch R = 1 ,3090.3,503.9,503.9,503.9
XS GIS Cut Line= 3
      1857268.00       750315.66      1857157.35       750200.75
      1857024.33       750177.28
BEGIN DESCRIPTION:
Greenbriar Creek 6.0
END DESCRIPTION:
#Sta/Elev= 20
  4848.3  594.32  4923.3  585.85  4933.3  585.23  4948.3  583.59  4958.3  582.33
  4978.3  580.68  4990.8  576.57  4992.3  573.57  5007.8  573.57  5009.3  576.57
  5032.9  577.91  5037.9  577.43  5047.9   576.9  5067.9  577.14  5072.9  577.51
  5087.9  579.43  5092.9  580.42  5097.9  581.59  5112.9  586.47  5142.9  595.32
#Mann= 3 , 1 , 0
 4848.30     0.1       0  4990.8    0.05       0  5009.3    0.12       0
Bank Sta=4990.80,5009.30
Exp/Cntr=0.3,0.1

Type RM Length L Ch R = 1 ,2586.4,353.5,353.5,353.5
XS GIS Cut Line= 3
      1857658.11       750033.89      1857558.34       749903.95
      1857417.70       749838.84
BEGIN DESCRIPTION:
Greenbriar Creek 5.0
END DESCRIPTION:
#Sta/Elev= 26
  4832.1  593.76  4842.1  592.09  4862.1  587.39  4887.1  584.07  4892.1  583.21
  4907.1  579.82  4912.1  578.96  4922.1  577.63  4927.1   577.1  4937.1  576.36
  4990.7  576.16  4992.2  573.16  5007.7  573.16  5009.2  576.16  5010.9  576.45
  5015.9  576.74  5070.9  577.81  5090.9  579.11  5100.9  580.37  5105.9  581.16
  5110.9  582.41  5115.9  584.06  5120.9  585.98  5125.9  587.69  5130.9  588.79
  5150.9  594.32
#Mann= 3 , 1 , 0
 4832.10     0.1       0  4990.7    0.05       0  5009.2    0.15       0
Bank Sta=4990.70,5009.20
Exp/Cntr=0.3,0.1

Type RM Length L Ch R = 1 ,2232.9,732.9,732.9,732.9
XS GIS Cut Line= 3
      1857923.64       749763.81      1857764.52       749619.15
      1857458.02       749450.05
BEGIN DESCRIPTION:
Greenbriar Creek 4.0
END DESCRIPTION:
#Sta/Elev= 30
  4808.2   590.3  4813.2  589.69  4833.2  586.36  4848.2  582.96  4863.2  580.06
  4878.2  578.31  4898.2   576.8  4928.2  576.16  4943.2   576.3  4973.2  576.14
  4990.7  575.86  4992.2  572.86  5007.8  572.86  5009.3  575.86  5023.3  576.27
  5038.3  576.18  5043.3  576.33  5078.3  575.03  5083.3  575.02  5133.3  575.54
  5138.3  575.76  5328.3  576.46  5333.3  576.73  5338.3  577.12  5343.3  577.67
  5348.3  578.54  5353.3  579.66  5358.3  581.86  5363.3  584.62  5373.3  590.41
#Mann= 3 , 1 , 0
 4808.20     0.1       0  4990.7    0.05       0  5009.3    0.12       0
Bank Sta=4990.70,5009.30
Exp/Cntr=0.3,0.1

Type RM Length L Ch R = 1 ,1500.0,500,500,500
XS GIS Cut Line= 3
      1857752.63       749095.08      1857660.16       749176.63
      1857523.11       749249.03
BEGIN DESCRIPTION:
Greenbriar Creek 3.0
END DESCRIPTION:
#Sta/Elev= 30
  4876.7  589.16  4886.7  586.58  4891.7  585.69  4926.7   578.1  4931.7  577.16
  4936.7  576.38  4946.7  575.83  4951.7  575.89  4956.7   576.2  4961.7  576.19
  4966.7  576.39  4990.5  575.25    4992  572.25    5008  572.25  5009.5  575.25
    5020  575.05    5025  575.17    5030  575.51    5035  576.16    5045  576.05
    5050  576.23    5055  576.71    5060  577.35    5065  578.24    5070  579.36
    5100     585    5105  585.67    5110  586.12    5125   588.3    5155  591.36
#Mann= 3 , 1 , 0
 4876.70     0.1       0  4990.5    0.05       0  5009.5    0.12       0
Bank Sta=4990.50,5009.50
Exp/Cntr=0.3,0.1

Type RM Length L Ch R = 1 ,1000.0,467.1,467.1,467.1
XS GIS Cut Line= 3
      1857481.99       748833.82      1857356.39       748834.83
      1857241.04       748786.68
BEGIN DESCRIPTION:
Greenbriar Creek 2.0
END DESCRIPTION:
#Sta/Elev= 23
  4874.4  589.22  4889.4   586.6  4899.4  585.38  4909.4  583.31  4929.4  579.87
  4934.4  578.75  4939.4  577.33  4944.4  576.46  4969.4  576.07  4990.5  574.84
    4992  571.84    5008  571.84  5009.5  574.84    5015  575.29    5020  575.67
    5030  576.93    5080   580.7    5085  581.55    5090  582.56    5095  584.09
    5100  585.92    5105  587.52    5125  592.31
#Mann= 3 , 1 , 0
 4874.40    0.09       0  4990.5    0.05       0  5009.5    0.09       0
Bank Sta=4990.50,5009.50
Exp/Cntr=0.3,0.1

Type RM Length L Ch R = 1 ,532.9,293.9,293.9,293.9
XS GIS Cut Line= 3
      1857717.73       748487.27      1857561.02       748418.57
      1857419.40       748449.66
BEGIN DESCRIPTION:
Greenbriar Creek 1.0
END DESCRIPTION:
#Sta/Elev= 23
  4826.7  589.74  4831.7  588.59  4841.7  586.74  4856.7  582.99  4871.7  579.41
  4881.7  577.52  4886.7  577.05  4990.5  574.45    4992  571.45    5008  571.45
  5009.5  574.45  5017.8  575.81  5032.8  575.94  5037.8  576.15  5047.8  577.33
  5052.8   578.1  5057.8  579.07  5067.8   580.5  5072.8  581.06  5087.8  583.21
  5107.8  585.34  5127.8  588.21  5142.8  589.92
#Mann= 3 , 1 , 0
 4826.70    0.08       0  4990.5    0.05       0  5009.5    0.08       0
Bank Sta=4990.50,5009.50
Exp/Cntr=0.3,0.1

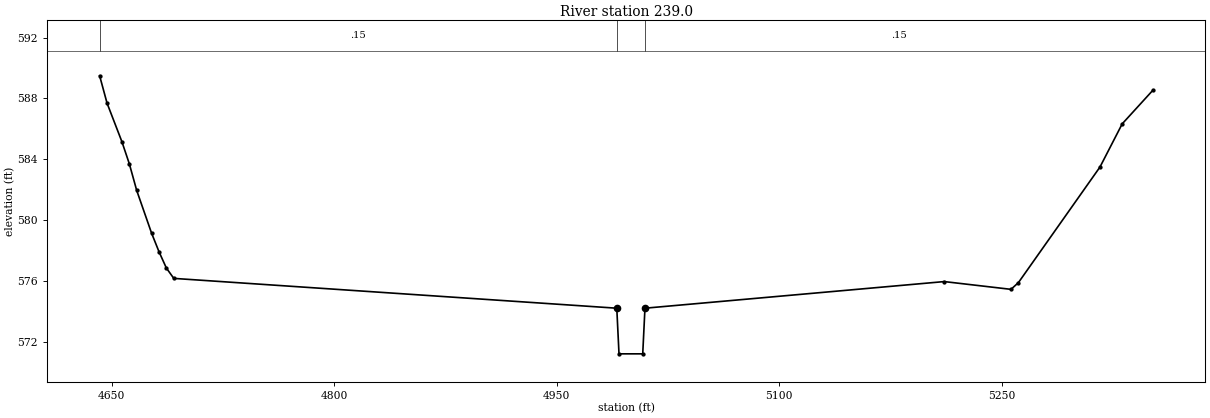
Type RM Length L Ch R = 1 ,239.0,0,0,0
XS GIS Cut Line= 3
      1857893.91       748165.65      1857536.66       748126.16
      1857260.36       748342.12
BEGIN DESCRIPTION:
Greenbriar Creek 0.5
END DESCRIPTION:
#Sta/Elev= 19
  4641.8  589.49  4646.8  587.69  4656.8  585.16  4661.8  583.71  4666.8  581.95
  4676.8  579.15  4681.8  577.93  4686.8  576.85  4691.8  576.17  4990.5  574.21
    4992  571.21    5008  571.21  5009.5  574.21  5211.3  575.96  5256.3  575.45
  5261.3  575.89  5316.3  583.49  5331.3  586.33  5351.9  588.53
#Mann= 3 , 1 , 0
 4641.80    0.15       0  4990.5    0.05       0  5009.5    0.15       0
Bank Sta=4990.50,5009.50
Exp/Cntr=0.3,0.1

Chan Stop Cuts=-1