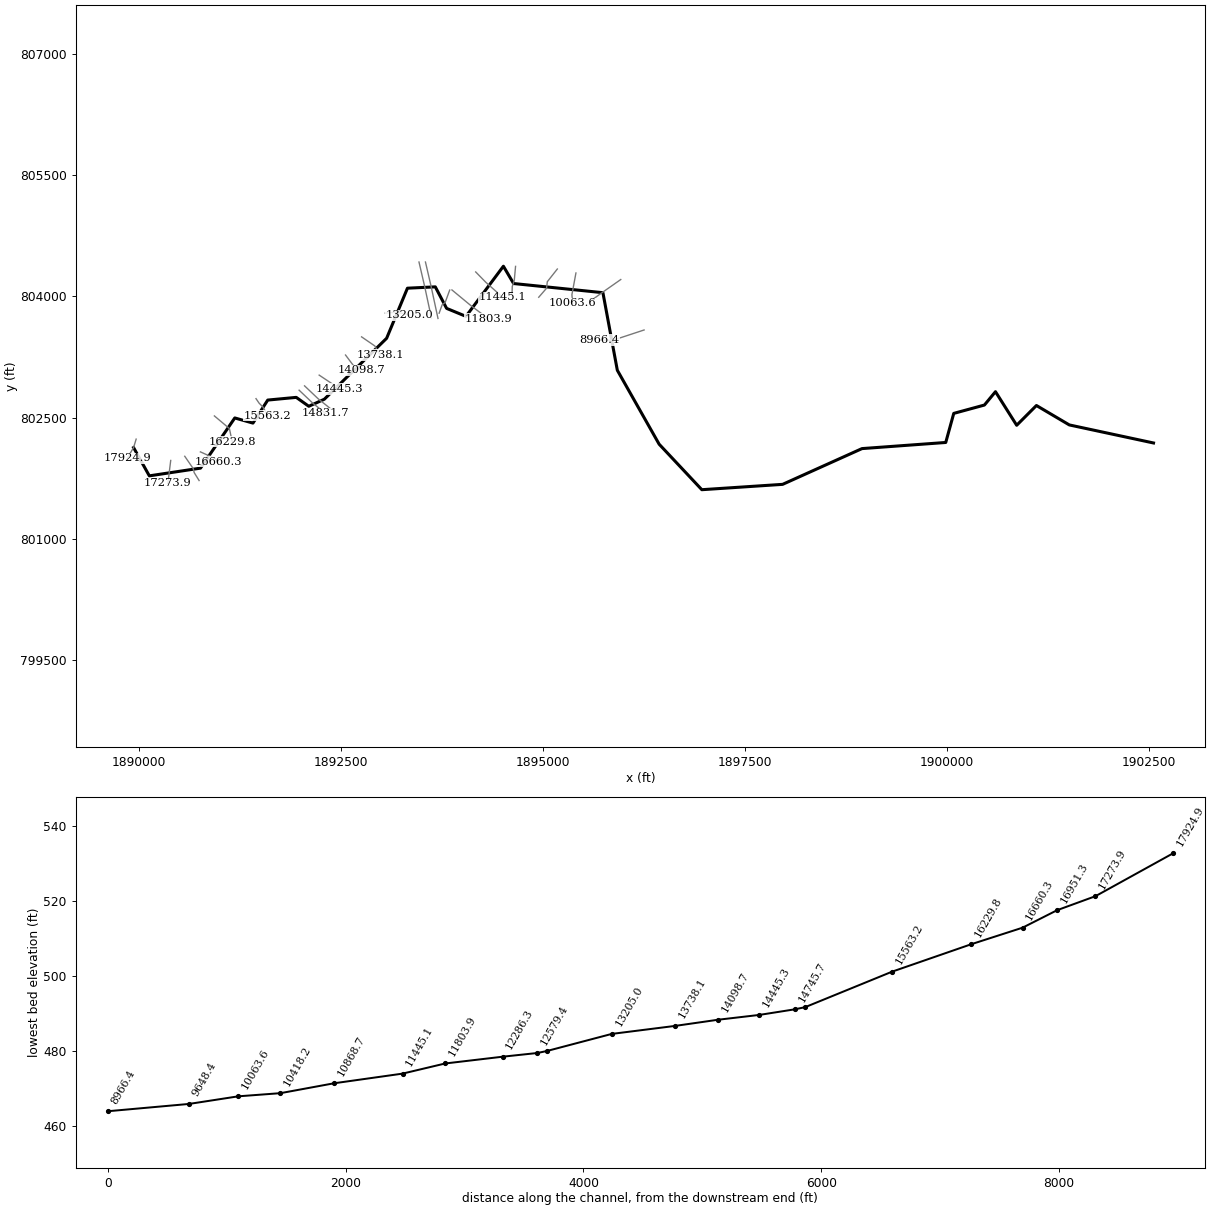
--- HAW RIVER TRIBUTARY 6.PRJ (project) ---

Proj Title=Haw River Tributary 6
Current Plan=p01
Default Exp/Contr=0.3,0.1
English Units
Geom File=g01
Flow File=f01
Plan File=p01
Y Axis Title=Elevation
X Axis Title(PF)=Main Channel Distance
X Axis Title(XS)=Station
BEGIN DESCRIPTION:
####(Watershed Name)####
HAW RIVER TRIBUTARY 6
HCFCD Unit X###-##-##
(Flood Hazard, Floodway) Model
10, 2, 1, 0.2% Event
Filename:  N:\NC_flood\60273\Approximates\Eng\Haw-Big_Alamance\Eng\Haw River Tributary 6\Haw River Tributary 6.prj
Prepared by:  ________     Date: ________
Reviewed by:  ________     Date: ________
STATUS (Draft RAS, SVSQ, FINAL)
END DESCRIPTION:
DSS Export Rating Curves= 0
DSS Export Rating Curve Sorted= 0
DSS Export Volume Flow Curves= 0
DXF OffsetX= 0
DXF OffsetY= 0
DXF ScaleX= 1
DXF ScaleY= 10

--- HAW RIVER TRIBUTARY 6.p01 (plan) ---

Plan Title=100-Year-Single
Program Version=3.10
Short Identifier=Plan01
Geom File=g01
Flow File=f01
Subcritical Flow
K Sum by GR= 0
Std Step Tol= 0.01
Critical Tol= 0.01
Num of Std Step Trials= 20
Max Error Tol= 0.3
Flow Tol Ratio= 0.001
Split Flow NTrial= 30
Split Flow Tol= 0.02
Split Flow Ratio= 0.02
Log Output Level= 0
Friction Slope Method= 1
Unsteady Friction Slope Method= 2
Parabolic Critical Depth
Global Vel Dist= 0 , 0 , 0
Global Log Level= 0
CheckData=True
Encroach Param=-1 ,10,10, 2
Encroach River=HawRiverTributar
Encroach Reach=Reach - 1
Encroach Node=17924.9
       4      .7
Encroach Node=17273.9
       4      .7
Encroach Node=16951.3
       4      .7
Encroach Node=16660.3
       1    4981  5015.5
Encroach Node=16229.8
       4      .7
Encroach Node=15563.2
       1    4976    5027
Encroach Node=14831.7
       4      .7
Encroach Node=14788.7
       4      .7
Encroach Node=14745.7
       4      .7
Encroach Node=14445.3
       4      .7
Encroach Node=14098.7
       4      .7
Encroach Node=13738.1
       4      .7
Encroach Node=13205.0
       4      .7
Encroach Node=12659.4
       4      .7
Encroach Node=12619.4
       4      .7
Encroach Node=12579.4
       4      .7
Encroach Node=12286.3
       4      .7
Encroach Node=11803.9
       1    4963    5035
Encroach Node=11445.1
       4      .7
Encroach Node=10868.7
       4      .7
Encroach Node=10418.2
       4      .7
Encroach Node=10063.6
       4      .7
Encroach Node=9648.4
       4      .7
Encroach Node=8966.4
       1    4927    5022
Encroach Node=8413.4
       1    4890    5037
Encroach Node=7968.0
       4      .7
Encroach Node=7500.0
       1    4965    5150
Encroach Node=6900.5
       4      .7
Encroach Node=6334.2
       4      .7
Encroach Node=5941.8
       4      .7
Encroach Node=5430.5
       1    4930    5043
Encroach Node=4930.3
       4      .7
Encroach Node=4479.3
       1    4975    5092
Encroach Node=3929.4
       4      .7
Encroach Node=3480.3
       4      .7
Encroach Node=3059.0
       1    4974    5055
Encroach Node=3039.0
       1    4974    5055
Encroach Node=3019.0
       1    4974    5055
Encroach Node=2510.2
       4      .7
Encroach Node=1786.0
       4      .7
Encroach Node=1314.0
       4      .7
Encroach Node=856.6
       4      .7
Encroach Node=606.4
       4      .7
Computation Interval=1HOUR
Output Interval=1HOUR
Run HTab= 0
Run UNet= 0
Run PostProcess= 0
UNET Theta= 1
UNET Theta Warmup= 1
UNET ZTol= 0.02
UNET ZSATol= 0.05
UNET MxIter= 20
UNET MaxInSteps= 1
UNET DtIC= 0
UNET DtMin= 0
UNET MaxCRTS= 20
UNET WFStab= 2
UNET SFStab= 1
UNET WFX= 1
UNET SFX= 1
UNET DSS MLevel= 4
UNET Convert EG Bridges=-1
UNET Use Existing IB Tables=-1
UNET Froude Reduction=False
UNET Froude Limit= 1
UNET Froude Power= 10
Instantaneous Interval=1HOUR
Write IC File= 0
Echo Input=False
Echo Output=False
Write Detailed= 0

--- HAW RIVER TRIBUTARY 6.f01 (steady flow) ---

Flow Title= 100-Year-Single
Program Version=3.10
Number of Profiles= 2
Profile Names=100-Year,AFW
River Rch & RM=HawRiverTributar,Reach - 1       ,17924.9
    1320    1320
River Rch & RM=HawRiverTributar,Reach - 1       ,9648.4
    1670    1670
River Rch & RM=HawRiverTributar,Reach - 1       ,5941.8
    2010    2010
River Rch & RM=HawRiverTributar,Reach - 1       ,3929.4
    2120    2120
Boundary for River Rch & Prof#=HawRiverTributar,Reach - 1       , 1
Up Type= 0
Dn Type= 3
Dn Slope=0.0004
Boundary for River Rch & Prof#=HawRiverTributar,Reach - 1       , 2
Up Type= 0
Dn Type= 1
Dn Known WS=452.51
DSS Import GetInterval= 0
DSS Import GetPeak= 0
DSS Import FillOption= 0

--- HAW RIVER TRIBUTARY 6.g01 (geometry) ---

Geom Title=Geom 01 by CodeH2 for Windows

River Reach=HawRiverTributar,Reach - 1
Reach XY= 30
      1889935.46       802131.96      1890130.25        801782.5
      1890763.75       801877.94      1891187.62       802498.38
      1891412.25       802434.69      1891595.25       802719.38
       1891947.7       802752.75      1892103.07       802642.65
      1892295.25       802729.75      1893066.01       803483.31
      1893323.62       804102.57      1893668.25       804119.06
      1893808.13          803853       1894047.5       803754.31
      1894510.75       804374.13      1894636.87       804160.19
      1895741.87          804047      1895920.13       803088.06
      1896437.37          802174       1896965.5       801611.31
      1897964.87       801677.37      1898947.25        802119.5
      1899983.13       802195.19      1900082.25       802554.69
      1900461.62       802657.94      1900598.37       802823.19
      1900860.87       802407.81         1901105       802652.25
      1901511.88       802412.06      1902553.75       802188.81

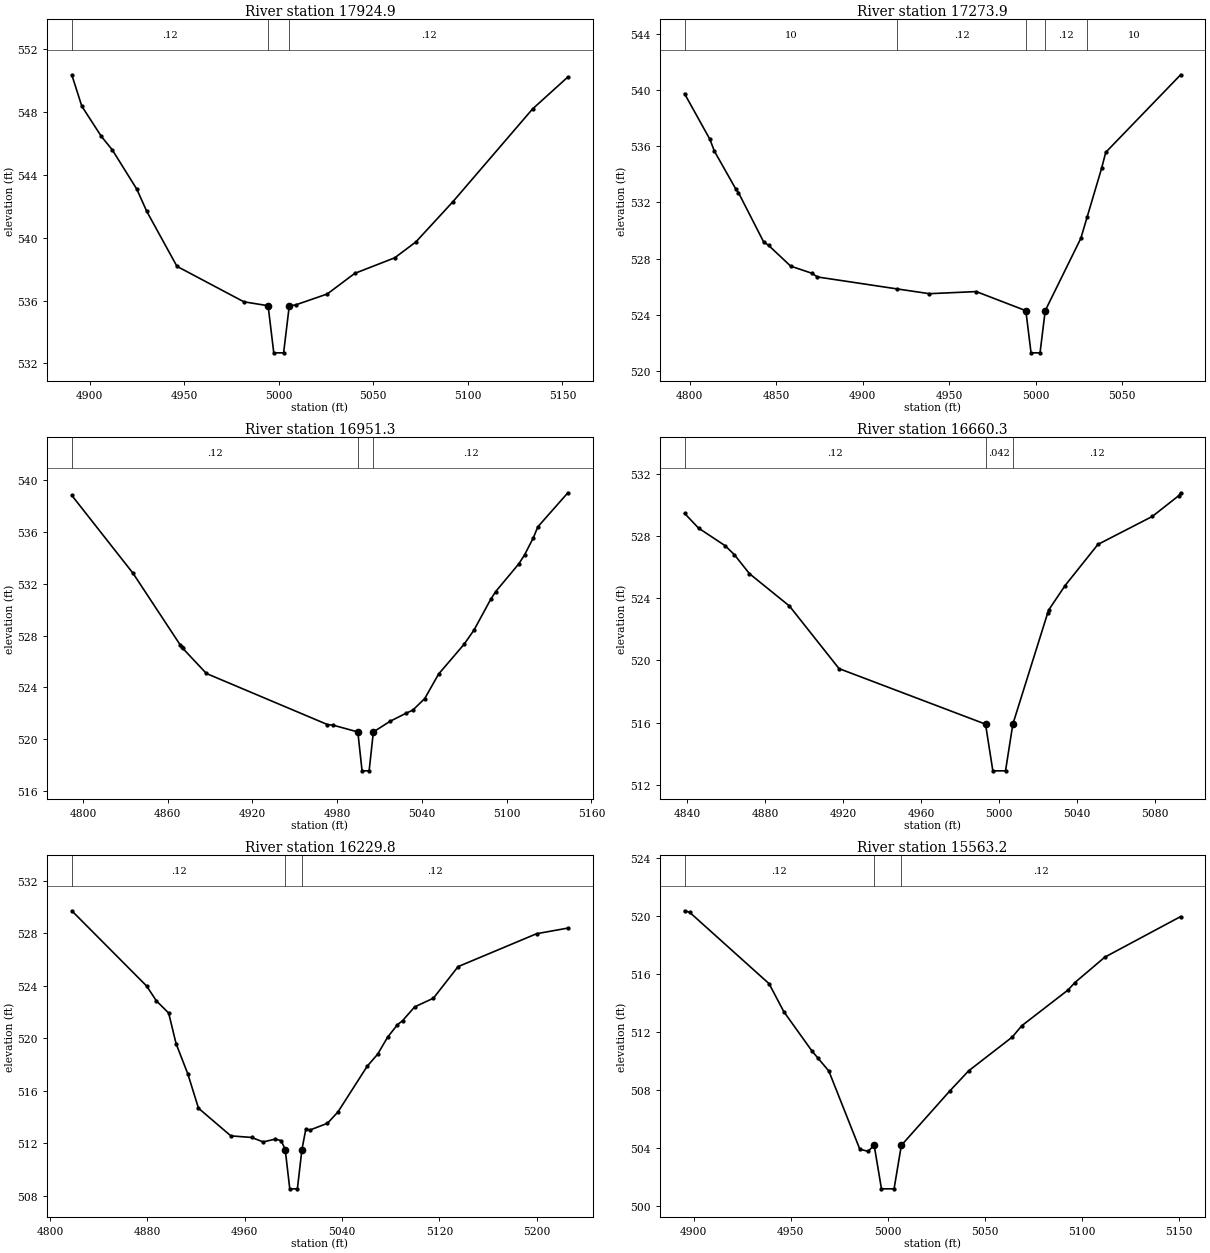
Type RM Length L Ch R = 1 ,17924.9,651,651,651
XS GIS Cut Line= 3
      1889967.24       802236.65      1889935.40       802131.78
      1889856.91       802000.79
BEGIN DESCRIPTION:
Haw River Tributary 6 36.0
END DESCRIPTION:
#Sta/Elev= 20
  4890.6  550.38  4895.9  548.38  4906.2  546.46    4912   545.6    4925  543.09
  4930.2  541.69  4946.2  538.18  4981.6  535.92  4994.4  535.67  4997.4  532.67
  5002.6  532.67  5005.6  535.67  5008.9  535.72  5025.7  536.42  5040.2  537.73
  5061.3  538.72  5072.5  539.73    5092  542.28  5134.2   548.2  5152.9  550.24
#Mann= 3 , 1 , 0
 4890.60    0.12       0  4994.4   0.042       0  5005.6    0.12       0
Bank Sta=4994.40,5005.60
Exp/Cntr=0.3,0.1

Type RM Length L Ch R = 1 ,17273.9,322.6,322.6,322.6
XS GIS Cut Line= 3
      1890394.89       801972.72      1890369.88       801770.39
      1890358.21       801688.18
BEGIN DESCRIPTION:
Haw River Tributary 6 35.0
END DESCRIPTION:
#Sta/Elev= 22
    4797  539.74  4811.7  536.48  4814.3  535.64  4826.7  532.94  4828.2  532.69
  4842.7   529.2  4845.6  528.94  4858.4  527.46  4870.5  526.96  4873.9  526.69
  4919.9  525.84  4938.6   525.5  4965.7  525.65  4994.4  524.29  4997.4  521.29
  5002.6  521.29  5005.6  524.29  5026.2  529.44  5029.9  530.98  5038.2  534.42
  5040.6  535.56  5083.9  541.08
#Mann= 5 , 1 , 0
 4797.00      10       0  4919.9    0.12       0  4994.4   0.042       0
  5005.6    0.12       0  5029.9      10       0
Bank Sta=4994.40,5005.60
Exp/Cntr=0.3,0.1

Type RM Length L Ch R = 1 ,16951.3,291,291,291
XS GIS Cut Line= 4
      1890568.62       802024.44      1890673.52       801871.97
      1890685.56       801822.08      1890746.04       801724.49
BEGIN DESCRIPTION:
Haw River Tributary 6 34.0
END DESCRIPTION:
#Sta/Elev= 26
  4792.1  538.81  4835.4  532.81    4869  527.25    4870  527.12  4870.6  527.02
  4887.4  525.07  4973.1  521.13  4977.2  521.08  4994.6  520.56  4997.6  517.56
  5002.6  517.56  5005.6  520.56  5017.4  521.38  5028.5  521.99  5033.5  522.24
    5042  523.14  5051.8  525.03  5069.8  527.32  5076.9  528.43  5088.6  530.78
  5092.2  531.39  5108.5  533.52  5112.6  534.21  5118.9  535.55    5122  536.38
  5143.3  539.01
#Mann= 3 , 1 , 0
 4792.10    0.12       0  4994.6   0.042       0  5005.6    0.12       0
Bank Sta=4994.60,5005.60
Exp/Cntr=0.3,0.1

Type RM Length L Ch R = 1 ,16660.3,430.5,430.5,430.5
XS GIS Cut Line= 3
      1890762.01       802078.80      1890940.15       801999.27
      1890981.10       801956.50
BEGIN DESCRIPTION:
Haw River Tributary 6 33.0
END DESCRIPTION:
#Sta/Elev= 18
  4838.7  529.45  4845.9   528.5  4859.5  527.37  4864.2   526.8    4872  525.57
  4892.5  523.49  4917.9  519.47    4993   515.9 4996.75   512.9 5003.25   512.9
    5007   515.9  5024.8  523.02  5025.5  523.26  5033.8  524.81  5050.6  527.45
  5078.5  529.25    5092  530.58    5093  530.77
#Mann= 3 , 1 , 0
 4838.70    0.12       0    4993   0.042       0    5007    0.12       0
Bank Sta=4993.00,5007.00
Exp/Cntr=0.3,0.1

Type RM Length L Ch R = 1 ,16229.8,666.6,666.6,666.6
XS GIS Cut Line= 3
      1890935.03       802523.47      1891120.78       802367.39
      1891155.21       802206.04
BEGIN DESCRIPTION:
Haw River Tributary 6 32.0
END DESCRIPTION:
#Sta/Elev= 30
  4817.9  529.72  4879.4  523.98  4887.4  522.85  4897.5  521.92  4903.6  519.58
  4913.3  517.26    4922  514.66  4948.6  512.55  4965.6  512.43  4975.1  512.09
    4985   512.3  4989.9  512.19 4993.25  511.51    4997  508.51 5003.25  508.51
    5007  511.51  5010.2  513.07  5013.7     513    5028  513.51  5036.7  514.39
  5060.6  517.86  5069.2  518.78  5077.4  520.08  5085.4  521.02  5089.8  521.35
  5099.6  522.39    5115  523.05  5135.3  525.46  5199.8  527.97  5225.5   528.4
#Mann= 3 , 1 , 0
 4817.90    0.12       0 4993.25   0.042       0    5007    0.12       0
Bank Sta=4993.25,5007.00
Exp/Cntr=0.3,0.1

Type RM Length L Ch R = 1 ,15563.2,731.5,731.5,731.5
XS GIS Cut Line= 4
      1891450.02       802737.03      1891488.90       802680.47
      1891537.07       802632.31      1891594.35       802527.95
BEGIN DESCRIPTION:
Haw River Tributary 6 31.0
END DESCRIPTION:
#Sta/Elev= 21
  4895.2  520.38  4897.8  520.28  4938.8  515.35  4946.4  513.42  4960.9  510.71
  4963.8  510.25  4969.6  509.33  4985.6  503.93  4989.8  503.79    4993   504.2
 4996.75   501.2 5003.25   501.2    5007   504.2  5031.9  507.94  5041.7  509.34
  5064.2  511.67  5069.1  512.45  5092.9  514.91  5096.5  515.43  5111.9  517.18
    5151  519.98
#Mann= 3 , 1 , 0
 4895.20    0.12       0    4993   0.042       0    5007    0.12       0
Bank Sta=4993.00,5007.00
Exp/Cntr=0.5,0.3

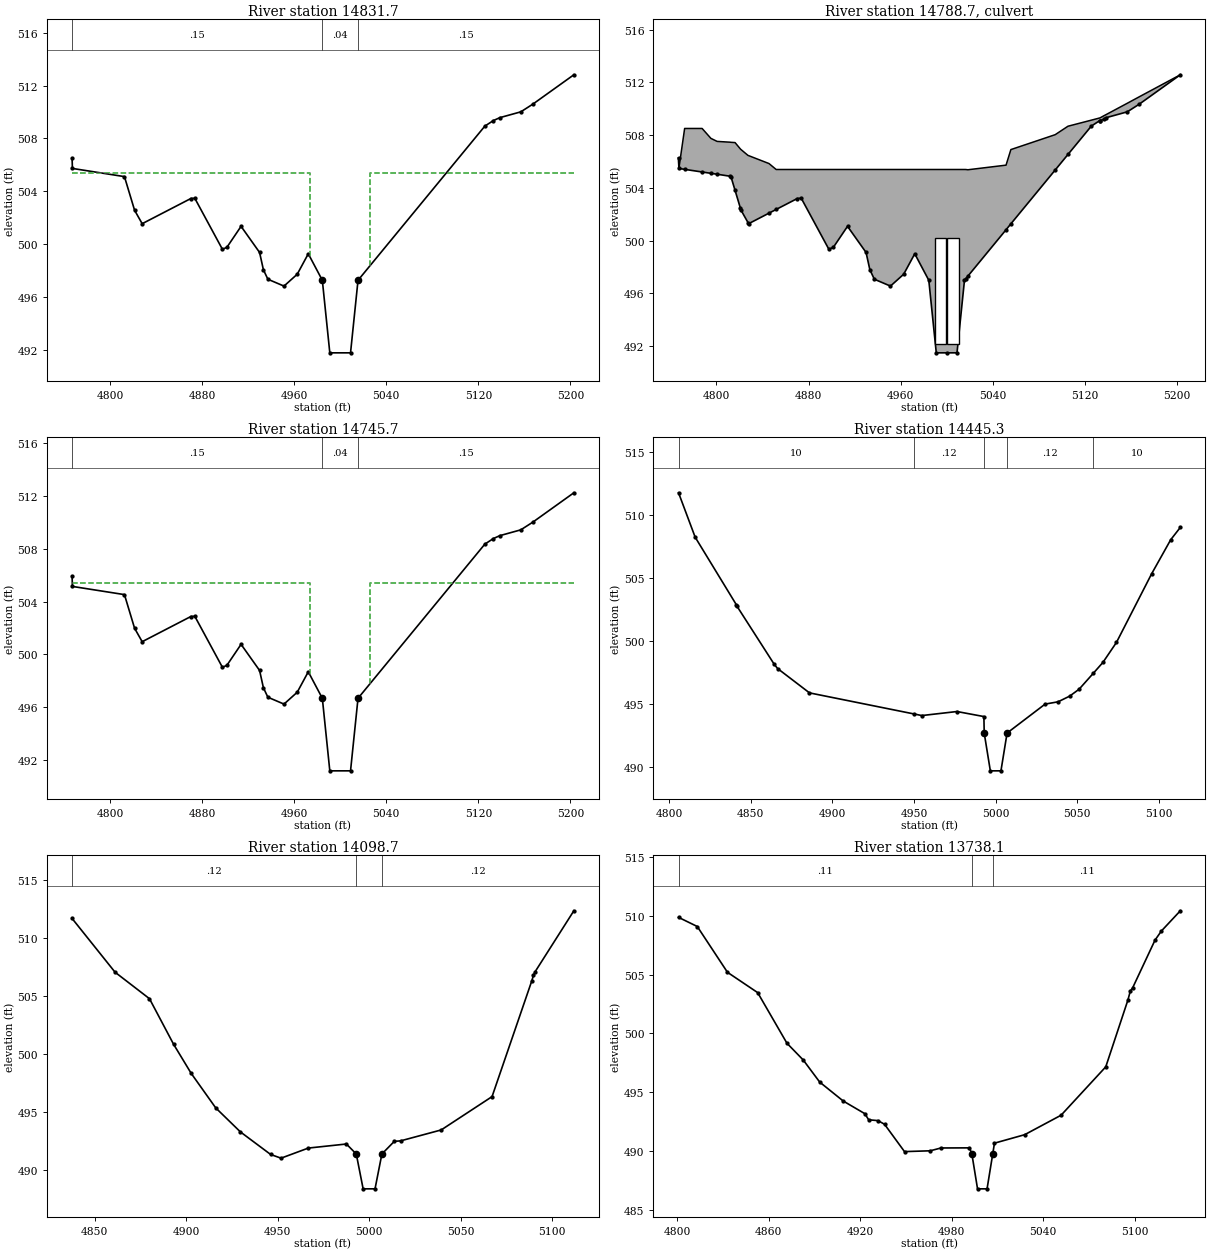
Type RM Length L Ch R = 1 ,14831.7,86,86,86
XS GIS Cut Line= 3
      1891983.31       802841.61      1892152.14       802681.44
      1892310.80       802554.51
BEGIN DESCRIPTION:
Upstream Section of Bridge/Culvert/Weir
END DESCRIPTION:
#Sta/Elev= 26
  4767.1  506.53  4767.4  505.73  4812.6  505.11  4821.4  502.56    4828  501.54
  4870.3  503.45  4873.7  503.47  4897.7   499.6  4901.6  499.75  4913.9  501.34
    4930  499.36  4933.3  498.05  4937.2  497.33  4951.2  496.81  4962.7  497.71
  4972.3  499.26  4984.5  497.25    4991  491.75    5009  491.75  5015.5  497.25
  5125.7  508.94  5133.1  509.36  5138.7  509.58  5156.9  510.02  5167.3   510.6
    5203  512.83
#Mann= 3 , 1 , 0
 4767.10    0.15       0  4984.5    0.04       0  5015.5    0.15       0
#XS Ineff= 2 , 0
       0    4974   505.4    5026       0   505.4
Bank Sta=4984.50,5015.50
Exp/Cntr=0.5,0.3

Type RM Length L Ch R = 2 ,14788.7,,,
BEGIN DESCRIPTION:
Haw River Tributary 6 - NC 87
Structure ID: NCF-0205
Approximate Survey Structure
END DESCRIPTION:
Bridge Culvert--1,0,-1,-1, 0
Deck Dist Width WeirC Skew NumUp NumDn MinLoCord MaxHiCord MaxSubmerge Is_Ogee
10,66,3,,45,45,,,0.95,0,1,1,,
  4767.1  4767.4  4772.4  4787.6  4795.2  4800.6  4811.8  4812.6  4816.2  4820.9
  4821.4  4827.4    4828  4845.7  4851.9  4870.3  4873.7  4897.7  4901.6  4913.9
    4930  4933.3  4937.2  4951.2  4962.7  4972.3  4984.5    4991    5000    5009
  5015.5  5016.4  5018.5  5051.6  5055.8  5094.3  5105.4  5125.7  5133.1  5133.2
  5136.3  5138.7  5156.9  5167.3    5203
  506.28  505.48  508.51  508.51  507.76  507.53  507.47  507.46  507.44  506.95
  506.91  506.47  506.45  505.85   505.4   505.4   505.4   505.4   505.4   505.4
   505.4   505.4   505.4   505.4   505.4   505.4   505.4   505.4   505.4   505.4
   505.4   505.4  505.38  505.73  506.91  508.04  508.68  509.14  509.31  509.31
  509.46  509.57  510.42  510.91  512.58
  506.28  505.48  505.41  505.21  505.11  505.04  504.89  504.86  503.82  502.45
  502.31  501.38  501.29  502.09  502.37   503.2  503.22  499.35   499.5  501.09
  499.11   497.8  497.08  496.56  497.46  499.01     497   491.5   491.5   491.5
     497   497.1  497.32  500.83  501.28  505.36  506.54  508.69  509.11  509.11
  509.19  509.33  509.77  510.35  512.58
  4767.1  4767.4  4772.4  4787.6  4795.2  4800.6  4811.8  4812.6  4816.2  4820.9
  4821.4  4827.4    4828  4845.7  4851.9  4870.3  4873.7  4897.7  4901.6  4913.9
    4930  4933.3  4937.2  4951.2  4962.7  4972.3  4984.5    4991    5000    5009
  5015.5  5016.4  5018.5  5051.6  5055.8  5094.3  5105.4  5125.7  5133.1  5133.2
  5136.3  5138.7  5156.9  5167.3    5203
  506.28  505.48  508.51  508.51  507.76  507.53  507.47  507.46  507.44  506.95
  506.91  506.47  506.45  505.85   505.4   505.4   505.4   505.4   505.4   505.4
   505.4   505.4   505.4   505.4   505.4   505.4   505.4   505.4   505.4   505.4
   505.4   505.4  505.38  505.73  506.91  508.04  508.68  509.14  509.31  509.31
  509.46  509.57  510.42  510.91  512.58
  505.95  505.15  505.08  504.88  504.78  504.71  504.56  504.53  503.49  502.12
  501.98  501.05  500.96  501.76  502.04  502.87  502.89  499.02  499.17  500.76
  498.78  497.47  496.75  496.23  497.13  498.68  496.67  491.17  491.17  491.17
  496.67  496.77  496.99   500.5  500.95  505.03  506.21  508.36  508.78  508.78
  508.86     509  509.44  510.02  512.25
BR Coef= 1 , 0 , 0 ,1.25, 0 ,,,0.8,-1,2,0,
Wspro=,,,, 1 ,,,, 0 ,,,, 0 ,,,,-1 ,-1 ,-1 , 0 , 0 , 0 , 0 , 0
Culvert=2,8.0,10.0,66.0,0.015,0.4,1.0,8,1,492.20,4994.53,491.87,4994.53,Culvert #1  ,0,10
Culvert=2,8.0,10.0,66.0,0.015,0.4,1.0,8,1,492.20,5005.53,491.87,5005.53,Culvert #2  ,0,10
BC Design=,, 0 ,, 0 ,,,,,,
BR U #Sta/Elev= 45
  4767.1  506.28  4767.4  505.48  4772.4  505.41  4787.6  505.21  4795.2  505.11
  4800.6  505.04  4811.8  504.89  4812.6  504.86  4816.2  503.82  4820.9  502.45
  4821.4  502.31  4827.4  501.38    4828  501.29  4845.7  502.09  4851.9  502.37
  4870.3   503.2  4873.7  503.22  4897.7  499.35  4901.6   499.5  4913.9  501.09
    4930  499.11  4933.3   497.8  4937.2  497.08  4951.2  496.56  4962.7  497.46
  4972.3  499.01  4984.5     497    4991   491.5    5000   491.5    5009   491.5
  5015.5     497  5016.4   497.1  5018.5  497.32  5051.6  500.83  5055.8  501.28
  5094.3  505.36  5105.4  506.54  5125.7  508.69  5133.1  509.11  5133.2  509.11
  5136.3  509.19  5138.7  509.33  5156.9  509.77  5167.3  510.35    5203  512.58
BR U #Mann= 3
 4767.10    0.15  4984.5    0.04  5015.5    0.15
BR U Banks=4984.50,5015.50
BR D #Sta/Elev= 45
  4767.1  505.95  4767.4  505.15  4772.4  505.08  4787.6  504.88  4795.2  504.78
  4800.6  504.71  4811.8  504.56  4812.6  504.53  4816.2  503.49  4820.9  502.12
  4821.4  501.98  4827.4  501.05    4828  500.96  4845.7  501.76  4851.9  502.04
  4870.3  502.87  4873.7  502.89  4897.7  499.02  4901.6  499.17  4913.9  500.76
    4930  498.78  4933.3  497.47  4937.2  496.75  4951.2  496.23  4962.7  497.13
  4972.3  498.68  4984.5  496.67    4991  491.17    5000  491.17    5009  491.17
  5015.5  496.67  5016.4  496.77  5018.5  496.99  5051.6   500.5  5055.8  500.95
  5094.3  505.03  5105.4  506.21  5125.7  508.36  5133.1  508.78  5133.2  508.78
  5136.3  508.86  5138.7     509  5156.9  509.44  5167.3  510.02    5203  512.25
BR D #Mann= 3
 4767.10    0.15  4984.5    0.04  5015.5    0.15
BR D Banks=4984.50,5015.50

Type RM Length L Ch R = 1 ,14745.7,300.4,300.4,300.4
XS GIS Cut Line= 3
      1892050.48       802895.31      1892219.30       802735.14
      1892377.96       802608.21
BEGIN DESCRIPTION:
Downstream Section of Bridge/Culvert/Weir
END DESCRIPTION:
#Sta/Elev= 26
  4767.1  505.96  4767.4  505.16  4812.6  504.54  4821.4  501.99    4828  500.97
  4870.3  502.88  4873.7   502.9  4897.7  499.03  4901.6  499.18  4913.9  500.77
    4930  498.79  4933.3  497.48  4937.2  496.76  4951.2  496.24  4962.7  497.14
  4972.3  498.69  4984.5  496.68    4991  491.18    5009  491.18  5015.5  496.68
  5125.7  508.37  5133.1  508.79  5138.7  509.01  5156.9  509.45  5167.3  510.03
    5203  512.26
#Mann= 3 , 1 , 0
 4767.10    0.15       0  4984.5    0.04       0  5015.5    0.15       0
#XS Ineff= 2 , 0
       0    4974   505.4    5026       0   505.4
Bank Sta=4984.50,5015.50
Exp/Cntr=0.5,0.3

Type RM Length L Ch R = 1 ,14445.3,346.6,346.6,346.6
XS GIS Cut Line= 3
      1892231.48       803027.83      1892394.07       802919.53
      1892486.65       802856.59
BEGIN DESCRIPTION:
Haw River Tributary 6 29.0
END DESCRIPTION:
#Sta/Elev= 25
  4805.8  511.76    4816  508.23  4841.2  502.87  4841.7  502.73  4864.4  498.14
  4866.5   497.8    4886  495.87  4949.9   494.2  4954.8  494.07  4976.3  494.39
  4992.8  493.99    4993  492.68 4996.75  489.68 5003.25  489.68    5007  492.68
  5030.3  494.98  5038.2  495.16  5045.3  495.61  5051.1  496.16  5059.9  497.44
  5065.7  498.29    5074  499.88  5095.5  505.32  5107.2  508.03  5113.1  509.01
#Mann= 5 , 1 , 0
 4805.80      10       0  4949.9    0.12       0    4993   0.042       0
    5007    0.12       0  5059.9      10       0
Bank Sta=4993.00,5007.00
Exp/Cntr=0.3,0.1

Type RM Length L Ch R = 1 ,14098.7,360.6,360.6,360.6
XS GIS Cut Line= 3
      1892557.50       803276.32      1892655.29       803146.30
      1892750.39       803088.07
BEGIN DESCRIPTION:
Haw River Tributary 6 28.0
END DESCRIPTION:
#Sta/Elev= 23
  4837.7  511.68  4861.2  507.05    4880  504.77  4893.2  500.84  4902.8  498.34
  4916.2  495.37  4929.7   493.3  4946.2  491.36  4951.9  491.04  4966.8  491.91
  4987.6  492.26    4993   491.4 4996.75   488.4 5003.25   488.4    5007   491.4
  5013.8  492.49  5017.2  492.53  5039.4  493.47  5067.2  496.34  5088.9   506.3
  5089.8  506.77  5090.6  507.06  5111.9  512.34
#Mann= 3 , 1 , 0
 4837.70    0.12       0    4993   0.042       0    5007    0.12       0
Bank Sta=4993.00,5007.00
Exp/Cntr=0.3,0.1

Type RM Length L Ch R = 1 ,13738.1,533.1,533.1,533.1
XS GIS Cut Line= 3
      1892756.34       803500.80      1892919.92       803388.52
      1892986.81       803276.24
BEGIN DESCRIPTION:
Haw River Tributary 6 27.0
END DESCRIPTION:
#Sta/Elev= 30
  4800.9  509.88  4813.2   509.1    4833   505.2  4852.8  503.47    4872  499.16
  4882.7  497.73  4893.5  495.85  4908.9  494.24  4923.1  493.16  4925.6  492.64
  4931.7  492.57    4936  492.26  4949.1  489.93    4966     490    4973  490.24
  4991.7  490.25 4993.25  489.76    4997  486.76 5003.25  486.76    5007  489.76
  5008.1  490.65  5027.9  491.37  5051.8  493.03  5081.1  497.15  5095.6  502.83
  5097.2   503.6  5098.7  503.87  5113.4  507.94  5117.6  508.72    5130  510.44
#Mann= 3 , 1 , 0
 4800.90    0.11       0 4993.25   0.041       0    5007    0.11       0
Bank Sta=4993.25,5007.00
Exp/Cntr=0.3,0.1

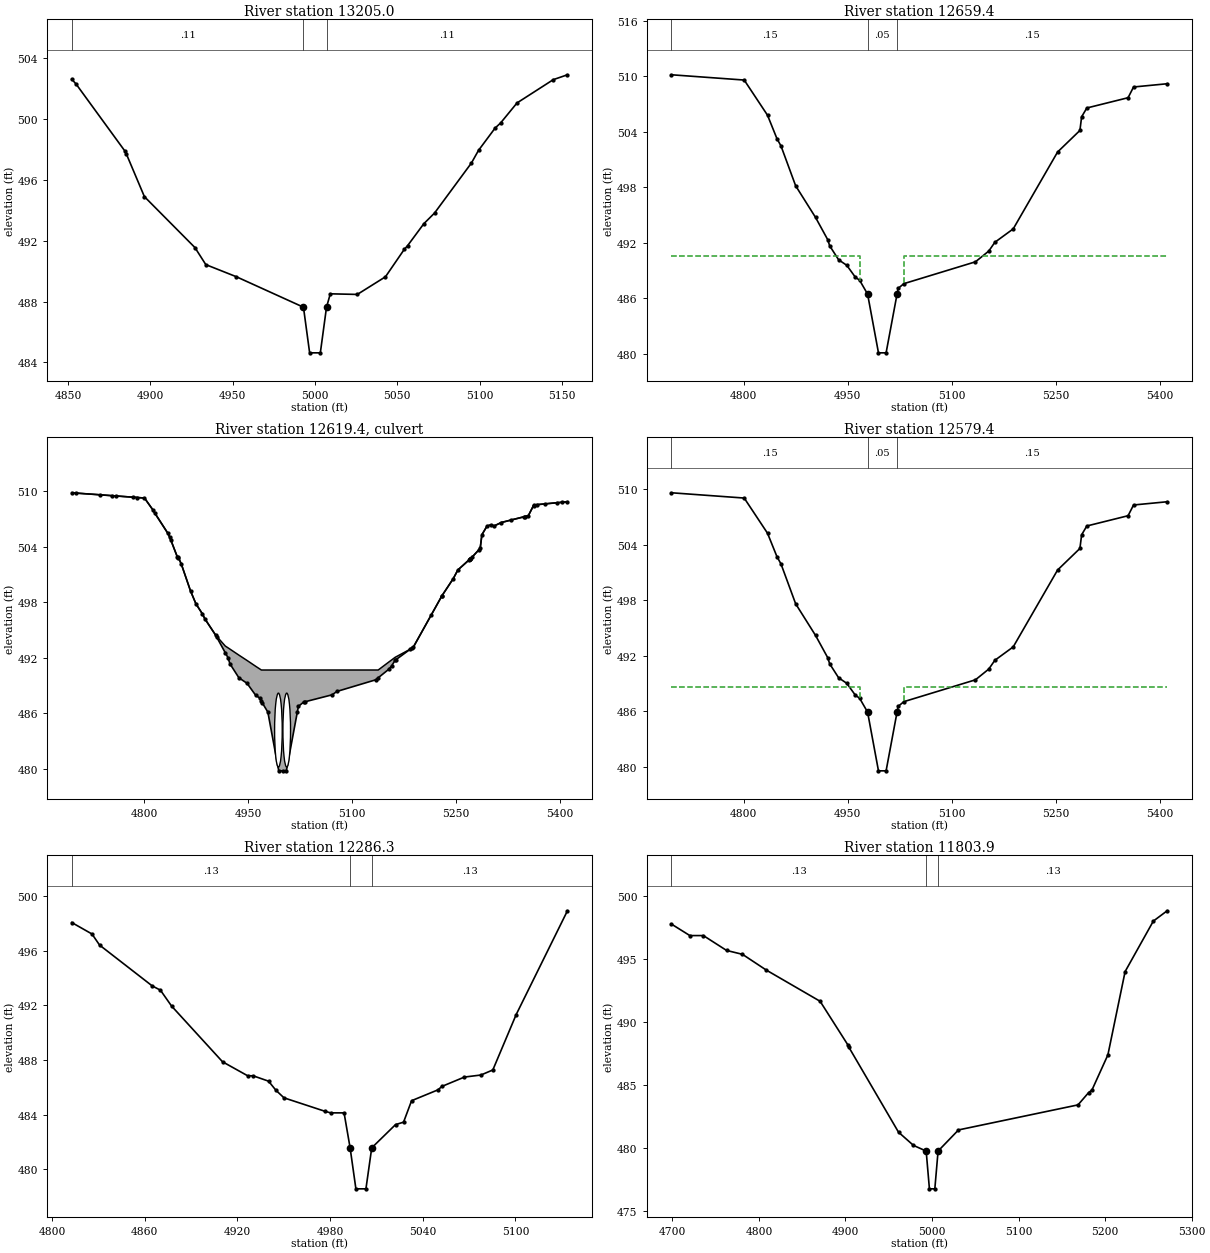
Type RM Length L Ch R = 1 ,13205.0,545.6,545.6,545.6
XS GIS Cut Line= 3
      1893049.13       803794.57      1893198.07       803806.76
      1893345.07       803769.84
BEGIN DESCRIPTION:
Haw River Tributary 6 26.0
END DESCRIPTION:
#Sta/Elev= 26
  4852.3  502.62    4855  502.29  4884.4  497.92  4885.4  497.72  4896.4   494.9
  4927.1  491.55  4933.7  490.43  4952.1  489.64    4993  487.63 4996.75  484.63
 5003.25  484.63    5007  487.63  5009.3  488.51  5025.7  488.47  5042.8  489.63
  5054.2  491.43  5056.2  491.67  5066.1  493.12  5072.6  493.82    5095  497.11
  5099.3  497.94  5109.4  499.41  5112.7  499.74  5122.7  501.06  5144.7  502.59
  5153.3  502.91
#Mann= 3 , 1 , 0
 4852.30    0.11       0    4993   0.041       0    5007    0.11       0
Bank Sta=4993.00,5007.00
Exp/Cntr=0.5,0.3

Type RM Length L Ch R = 1 ,12659.4,80,80,80
XS GIS Cut Line= 3
      1893466.38       804426.23      1893535.70       804127.54
      1893621.48       803728.17
BEGIN DESCRIPTION:
Upstream Section of Bridge/Culvert/Weir
END DESCRIPTION:
#Sta/Elev= 30
  4695.9  510.14  4800.8  509.57  4834.4  505.77    4848  503.24  4853.9  502.44
    4875  498.14  4903.7  494.72  4921.3  492.31  4924.1  491.65    4937  490.14
  4948.8  489.54  4961.3  488.24  4967.2  487.94  4978.8  486.43  4994.5  480.08
  5005.5  480.08  5021.3  486.43  5022.9  487.05  5031.2  487.56  5134.4  489.92
  5153.6  491.08  5162.4  492.03  5188.9  493.48  5252.9  501.79  5285.1  504.12
  5287.6   505.6  5295.1  506.55  5354.6  507.66  5362.5  508.82    5411  509.17
#Mann= 3 , 1 , 0
 4695.90    0.15       0  4978.8    0.05       0  5021.3    0.15       0
#XS Ineff= 2 , 0
       0    4968   490.6    5032       0   490.6
Bank Sta=4978.80,5021.30
Exp/Cntr=0.5,0.3

Type RM Length L Ch R = 2 ,12619.4,,,
BEGIN DESCRIPTION:
Haw River Tributary 6 - Cedar Cliff Rd
Structure ID: NCF-0206
Approximate Survey Structure
END DESCRIPTION:
Bridge Culvert--1,0,-1,-1, 0
Deck Dist Width WeirC Skew NumUp NumDn MinLoCord MaxHiCord MaxSubmerge Is_Ogee
10,60,3,, 48, 48,,,0.95,0,1,1,,
  4695.9  4800.8  4813.1  4834.4  4837.2    4848  4849.8  4853.9  4867.2    4875
  4884.4    4888  4903.7  4917.4  4921.3  4924.1    4937  4948.8  4961.3  4967.2
  4969.4  4978.8  4994.5  5005.5  5022.9  5031.2  5071.6  5078.3  5134.4    5138
  5153.6  5157.6  5162.4  5183.7  5188.9  5230.1  5246.4  5252.9  5271.1  5285.1
  5287.6  5295.1  5300.1  5305.6  5315.5  5354.6  5362.5    5411
  509.86   509.3     508   505.5  505.07  502.97  502.85  502.17  499.26  497.87
  496.77  496.23  494.45  493.29   493.1  492.96  492.31  491.73   491.1  490.81
   490.7   490.7   490.7   490.7   490.7   490.7   490.7   490.7   490.7   490.7
  491.58   491.8  492.07  492.93  493.21  498.75   500.6  501.52  502.72  503.85
  505.33  506.28  506.38  506.29  506.65  507.39  508.55  508.89
  509.86  509.29  507.99  505.49  505.06  502.96  502.84  502.16  499.25  497.86
  496.76  496.22  494.44  492.56  492.03  491.37  489.86  489.26  487.96  487.66
  487.35  486.15   479.8   479.8  486.77  487.28  488.02  488.38  489.64  489.86
   490.8  491.17  491.75  492.92   493.2  498.74  500.59  501.51  502.71  503.84
  505.32  506.27  506.37  506.28  506.64  507.38  508.54  508.89
  4695.9  4800.8  4813.1  4834.4  4837.2    4848  4849.8  4853.9  4867.2    4875
  4884.4    4888  4903.7  4917.4  4921.3  4924.1    4937  4948.8  4961.3  4967.2
  4969.4  4978.8  4994.5  5005.5  5022.9  5031.2  5071.6  5078.3  5134.4    5138
  5153.6  5157.6  5162.4  5183.7  5188.9  5230.1  5246.4  5252.9  5271.1  5285.1
  5287.6  5295.1  5300.1  5305.6  5315.5  5354.6  5362.5    5411
  509.86   509.3     508   505.5  505.07  502.97  502.85  502.17  499.26  497.87
  496.77  496.23  494.45  493.29   493.1  492.96  492.31  491.73   491.1  490.81
   490.7   490.7   490.7   490.7   490.7   490.7   490.7   490.7   490.7   490.7
  491.58   491.8  492.07  492.93  493.21  498.75   500.6  501.52  502.72  503.85
  505.33  506.28  506.38  506.29  506.65  507.39  508.55  508.89
  509.56  508.99  507.69  505.19  504.76  502.66  502.54  501.86  498.95  497.56
  496.46  495.92  494.14  492.26  491.73  491.07  489.56  488.96  487.66  487.36
  487.05  485.85   479.5   479.5  486.47  486.98  487.72  488.08  489.34  489.56
   490.5  490.87  491.45  492.62   492.9  498.44  500.29  501.21  502.41  503.54
  505.02  505.97  506.07  505.98  506.34  507.08  508.24  508.59
BR Coef= 1 , 0 , 0 ,1.25, 0 ,,,0.8,-1,2,0,
Wspro=,,,, 1 ,,,, 0 ,,,, 0 ,,,,-1 ,-1 ,-1 , 0 , 0 , 0 , 0 , 0
Culvert=4,8.0,11.0,60.0,0.015,0.4,1.0,29,1,480.20,4994.03,479.90,4994.03,Culvert #1  ,0,10
Culvert=4,8.0,11.0,60.0,0.015,0.4,1.0,29,1,480.20,5006.03,479.90,5006.03,Culvert #2  ,0,10
BC Design=,, 0 ,, 0 ,,,,,,
BR U #Sta/Elev= 80
  4695.9  509.86  4701.3  509.83    4737  509.64  4754.4  509.54  4760.3  509.51
  4783.9  509.38  4790.7  509.34  4800.8  509.29  4813.1  507.99  4815.9  507.62
  4834.4  505.49  4837.2  505.06  4838.6  504.79    4848  502.96  4848.7  502.91
  4849.8  502.84  4853.9  502.16  4867.2  499.25    4875  497.86  4884.4  496.76
    4888  496.22  4903.7  494.44    4905  494.26  4917.4  492.56  4921.3  492.03
  4924.1  491.37    4937  489.86  4948.8  489.26  4961.3  487.96  4967.2  487.66
  4969.4  487.35    4971  487.12  4978.8  486.15  4994.5   479.8    5000   479.8
  5005.5   479.8  5021.3  486.15  5022.9  486.77  5031.2  487.28  5032.6  487.27
  5071.6  488.02  5078.3  488.38  5134.4  489.64    5138  489.86  5153.6   490.8
  5157.6  491.17  5162.4  491.75  5163.3   491.8  5183.7  492.92  5187.3  493.11
  5188.9   493.2  5214.4  496.63  5230.1  498.74  5230.2  498.75  5246.4  500.59
  5252.9  501.51  5268.8   502.6  5270.1  502.69  5270.5  502.67  5270.7   502.7
  5271.1  502.71  5273.7  502.92  5282.7  503.65  5285.1  503.84  5287.6  505.32
  5295.1  506.27  5300.1  506.37  5305.6  506.28  5315.5  506.64  5329.1   506.9
  5348.4  507.26  5349.1  507.28  5354.6  507.38  5362.1  508.48  5362.5  508.54
  5367.1  508.57  5378.9  508.66  5395.6  508.78  5403.1  508.83    5411  508.89
BR U #Mann= 3
 4695.90    0.15  4978.8    0.05  5021.3    0.15
BR U Banks=4978.80,5021.30
BR D #Sta/Elev= 80
  4695.9  509.56  4701.3  509.53    4737  509.34  4754.4  509.24  4760.3  509.21
  4783.9  509.08  4790.7  509.04  4800.8  508.99  4813.1  507.69  4815.9  507.32
  4834.4  505.19  4837.2  504.76  4838.6  504.49    4848  502.66  4848.7  502.61
  4849.8  502.54  4853.9  501.86  4867.2  498.95    4875  497.56  4884.4  496.46
    4888  495.92  4903.7  494.14    4905  493.96  4917.4  492.26  4921.3  491.73
  4924.1  491.07    4937  489.56  4948.8  488.96  4961.3  487.66  4967.2  487.36
  4969.4  487.05    4971  486.82  4978.8  485.85  4994.5   479.5    5000   479.5
  5005.5   479.5  5021.3  485.85  5022.9  486.47  5031.2  486.98  5032.6  486.97
  5071.6  487.72  5078.3  488.08  5134.4  489.34    5138  489.56  5153.6   490.5
  5157.6  490.87  5162.4  491.45  5163.3   491.5  5183.7  492.62  5187.3  492.81
  5188.9   492.9  5214.4  496.33  5230.1  498.44  5230.2  498.45  5246.4  500.29
  5252.9  501.21  5268.8   502.3  5270.1  502.39  5270.5  502.37  5270.7   502.4
  5271.1  502.41  5273.7  502.62  5282.7  503.35  5285.1  503.54  5287.6  505.02
  5295.1  505.97  5300.1  506.07  5305.6  505.98  5315.5  506.34  5329.1   506.6
  5348.4  506.96  5349.1  506.98  5354.6  507.08  5362.1  508.18  5362.5  508.24
  5367.1  508.27  5378.9  508.36  5395.6  508.48  5403.1  508.53    5411  508.59
BR D #Mann= 3
 4695.90    0.15  4978.8    0.05  5021.3    0.15
BR D Banks=4978.80,5021.30

Type RM Length L Ch R = 1 ,12579.4,293.1,293.1,293.1
XS GIS Cut Line= 3
      1893546.38       804426.23      1893615.70       804127.54
      1893701.48       803728.17
BEGIN DESCRIPTION:
Downstream Section of Bridge/Culvert/Weir
END DESCRIPTION:
#Sta/Elev= 30
  4695.9  509.61  4800.8  509.04  4834.4  505.24    4848  502.71  4853.9  501.91
    4875  497.61  4903.7  494.19  4921.3  491.78  4924.1  491.12    4937  489.61
  4948.8  489.01  4961.3  487.71  4967.2  487.41  4978.8   485.9  4994.5  479.55
  5005.5  479.55  5021.3   485.9  5022.9  486.52  5031.2  487.03  5134.4  489.39
  5153.6  490.55  5162.4   491.5  5188.9  492.95  5252.9  501.26  5285.1  503.59
  5287.6  505.07  5295.1  506.02  5354.6  507.13  5362.5  508.29    5411  508.64
#Mann= 3 , 1 , 0
 4695.90    0.15       0  4978.8    0.05       0  5021.3    0.15       0
#XS Ineff= 2 , 0
       0    4968   488.6    5032       0   488.6
Bank Sta=4978.80,5021.30
Exp/Cntr=0.5,0.3

Type RM Length L Ch R = 1 ,12286.3,482.4,482.4,482.4
XS GIS Cut Line= 4
      1893846.38       804079.40      1893789.98       803925.63
      1893753.29       803898.10      1893715.63       803793.42
BEGIN DESCRIPTION:
Haw River Tributary 6 25.0
END DESCRIPTION:
#Sta/Elev= 29
  4812.8  498.05  4825.9  497.21  4830.8   496.4  4864.9  493.41  4870.2   493.1
  4877.4  491.94  4910.4  487.86  4926.6  486.84  4930.3  486.83  4940.2  486.44
    4945  485.77  4950.2  485.22  4976.6  484.24  4980.4  484.12  4989.1  484.12
    4993  481.56 4996.75  478.56 5003.25  478.56    5007  481.56  5022.4  483.26
  5027.6  483.44  5032.8  485.01    5050  485.81  5052.3  486.05    5067  486.74
  5077.7  486.89  5085.4  487.26  5100.5  491.31  5133.7  498.91
#Mann= 3 , 1 , 0
 4812.80    0.13       0    4993   0.042       0    5007    0.13       0
Bank Sta=4993.00,5007.00
Exp/Cntr=0.3,0.1

Type RM Length L Ch R = 1 ,11803.9,358.8,358.8,358.8
XS GIS Cut Line= 3
      1893874.19       804080.85      1894107.63       803887.97
      1894323.47       803725.95
BEGIN DESCRIPTION:
Haw River Tributary 6 24.0
END DESCRIPTION:
#Sta/Elev= 23
    4699  497.79  4720.2  496.88  4735.8  496.88  4762.6   495.7    4781  495.39
  4808.5  494.14  4870.7  491.66    4903  488.17  4904.1  487.99  4961.3  481.26
  4978.6  480.21 4993.25  479.76    4997  476.76 5003.25  476.76    5007  479.76
  5030.6  481.44  5168.7  483.43    5181  484.41  5184.8  484.61  5203.2   487.4
  5223.1  494.02  5255.7  498.03  5271.7  498.85
#Mann= 3 , 1 , 0
 4699.00    0.13       0 4993.25   0.042       0    5007    0.13       0
Bank Sta=4993.25,5007.00
Exp/Cntr=0.3,0.1

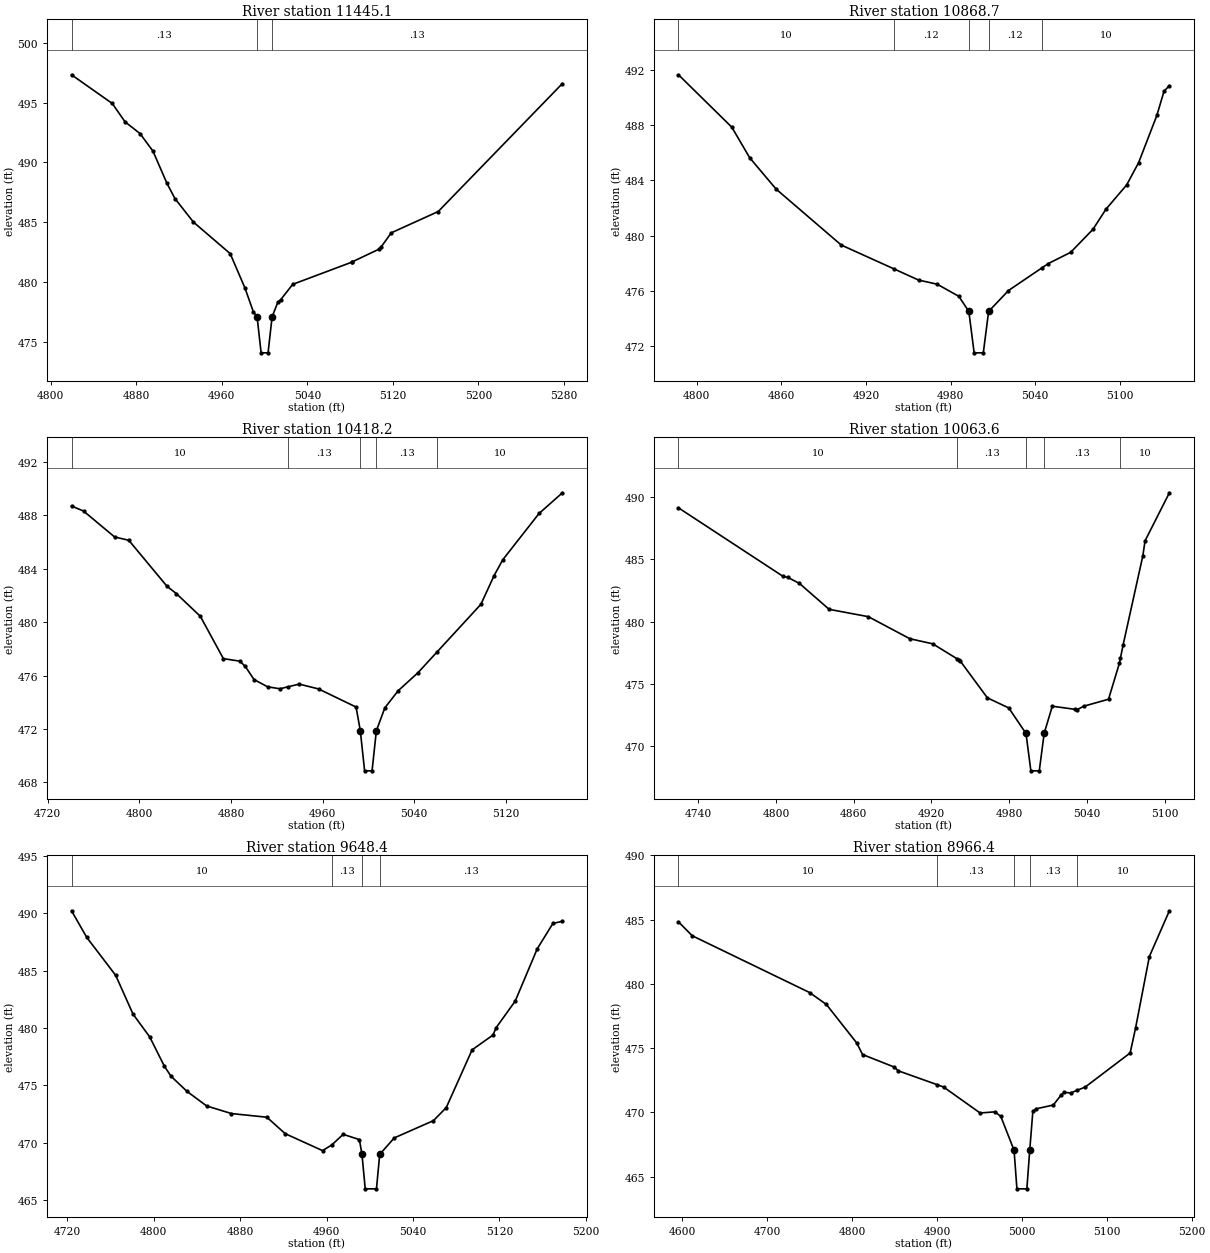
Type RM Length L Ch R = 1 ,11445.1,576.4,576.4,576.4
XS GIS Cut Line= 3
      1894168.08       804303.40      1894294.42       804174.24
      1894502.60       803989.20
BEGIN DESCRIPTION:
Haw River Tributary 6 23.0
END DESCRIPTION:
#Sta/Elev= 25
  4819.4  497.32  4857.5  494.92  4869.5  493.38  4883.5   492.4  4895.6  490.93
  4908.6  488.25  4916.1  486.97  4933.4     485  4967.8  482.36  4981.6  479.49
  4989.5  477.49    4993  477.06 4996.75  474.06 5003.25  474.06    5007  477.06
  5012.3  478.28  5015.1  478.51  5026.3  479.79    5082  481.66  5082.2  481.68
  5106.7  482.72  5108.8  482.89  5118.5   484.1  5162.4  485.88  5278.6  496.59
#Mann= 3 , 1 , 0
 4819.40    0.13       0    4993   0.042       0    5007    0.13       0
Bank Sta=4993.00,5007.00
Exp/Cntr=0.3,0.1

Type RM Length L Ch R = 1 ,10868.7,450.5,450.5,450.5
XS GIS Cut Line= 4
      1894661.08       804372.21      1894645.66       804202.66
      1894620.28       804122.88      1894617.70       804028.79
BEGIN DESCRIPTION:
Haw River Tributary 6 22.0
END DESCRIPTION:
#Sta/Elev= 24
  4787.1  491.66  4824.9  487.86  4837.6  485.64  4856.3  483.37  4902.5  479.31
  4939.9  477.58  4957.3  476.77  4970.5  476.47  4985.9  475.59    4993  474.49
 4996.75  471.49 5003.25  471.49    5007  474.49  5021.1  476.01  5044.9  477.66
  5049.4  477.97  5065.2  478.78    5081  480.45  5090.3  481.92  5104.9  483.67
  5113.4  485.29  5126.3  488.71  5131.4  490.47  5135.2  490.87
#Mann= 5 , 1 , 0
 4787.10      10       0  4939.9    0.12       0    4993   0.041       0
    5007    0.12       0  5044.9      10       0
Bank Sta=4993.00,5007.00
Exp/Cntr=0.3,0.1

Type RM Length L Ch R = 1 ,10418.2,354.6,354.6,354.6
XS GIS Cut Line= 4
      1895177.74       804339.63      1895053.77       804182.51
      1895044.60       804102.24      1894947.78       803990.61
BEGIN DESCRIPTION:
Haw River Tributary 6 21.0
END DESCRIPTION:
#Sta/Elev= 30
  4740.8  488.71  4751.3  488.33  4778.4  486.39  4790.8  486.14  4824.2  482.69
  4832.4  482.14  4853.3  480.44  4873.4  477.27  4887.8  477.08  4892.5  476.69
  4900.2   475.7    4912  475.16  4922.8  475.01  4929.9  475.16  4939.6  475.36
  4956.5     475  4989.3  473.64    4993  471.86 4996.75  468.86 5003.25  468.86
    5007  471.86  5014.4  473.58    5026  474.86  5043.3  476.21  5059.9  477.76
  5098.3  481.34  5109.8  483.49  5117.4  484.68  5149.1  488.15  5169.5   489.7
#Mann= 5 , 1 , 0
 4740.80      10       0  4929.9    0.13       0    4993   0.042       0
    5007    0.13       0  5059.9      10       0
Bank Sta=4993.00,5007.00
Exp/Cntr=0.3,0.1

Type RM Length L Ch R = 1 ,10063.6,415.2,415.2,415.2
XS GIS Cut Line= 3
      1895408.04       804290.66      1895358.28       804021.97
      1895367.49       803916.63
BEGIN DESCRIPTION:
Haw River Tributary 6 20.0
END DESCRIPTION:
#Sta/Elev= 28
  4724.7  489.14  4805.4  483.64    4809  483.56  4818.1  483.07    4841  480.99
  4871.3   480.4  4903.3  478.63    4921  478.22  4939.9  477.01  4941.5  476.91
  4942.3  476.83  4963.2  473.88  4979.7  473.07    4993  471.02 4996.75  468.02
 5003.25  468.02    5007  471.02  5013.3  473.21  5030.8  472.96    5032  472.91
  5037.6  473.21  5056.7  473.77  5065.1  476.66  5065.9  477.07  5067.9   478.1
  5083.2  485.29  5084.9  486.49  5103.7  490.35
#Mann= 5 , 1 , 0
 4724.70      10       0  4939.9    0.13       0    4993   0.042       0
    5007    0.13       0  5065.9      10       0
Bank Sta=4993.00,5007.00
Exp/Cntr=0.3,0.1

Type RM Length L Ch R = 1 ,9648.4,682,682,682
XS GIS Cut Line= 3
      1895962.76       804209.81      1895737.27       804051.78
      1895592.17       803947.05
BEGIN DESCRIPTION:
Haw River Tributary 6 19.0
END DESCRIPTION:
#Sta/Elev= 30
    4724  490.22  4738.1   487.9  4764.9  484.59  4780.9  481.22  4796.4  479.22
    4810  476.66  4816.2  475.79  4830.9  474.48  4849.1  473.21    4872  472.55
  4904.8  472.23  4921.7   470.8  4956.3  469.32  4964.9  469.82  4975.4  470.74
  4990.4  470.28  4992.8  468.99  4995.8  465.99  5006.2  465.99  5009.2  468.99
  5022.7  470.43  5058.9  471.93  5070.8  473.07  5094.7   478.1    5114  479.39
    5117  480.04  5134.6  482.35    5155  486.91  5169.5  489.12  5178.3   489.3
#Mann= 4 , 1 , 0
 4724.00      10       0  4964.9    0.13       0  4992.8   0.042       0
  5009.2    0.13       0
Bank Sta=4992.80,5009.20
Exp/Cntr=0.3,0.1

Type RM Length L Ch R = 1 ,8966.4,553,553,553
XS GIS Cut Line= 3
      1896251.20       803585.93      1895867.88       803459.58
      1895693.40       803462.06
BEGIN DESCRIPTION:
Haw River Tributary 6 18.0
END DESCRIPTION:
#Sta/Elev= 29
  4595.6  484.82  4611.7  483.74    4750  479.32  4769.8  478.39  4805.6  475.39
  4812.3   474.5  4849.4  473.53  4854.5  473.23  4899.9  472.16  4907.8  471.97
  4950.8  469.95  4968.3  470.04  4975.2  469.68 4990.78  467.05 4994.15  464.05
 5005.85  464.05 5009.23  467.05  5012.9  470.07  5017.1  470.28    5037  470.57
  5046.6  471.38  5050.1  471.55  5057.5  471.51  5064.9  471.71  5074.6  471.97
  5127.5  474.62    5134   476.6  5150.1  482.12  5173.7  485.68
#Mann= 5 , 1 , 0
 4595.60      10       0  4899.9    0.13       0 4990.78   0.042       0
 5009.23    0.13       0  5064.9      10       0
Bank Sta=4990.78,5009.23
Exp/Cntr=0.3,0.1