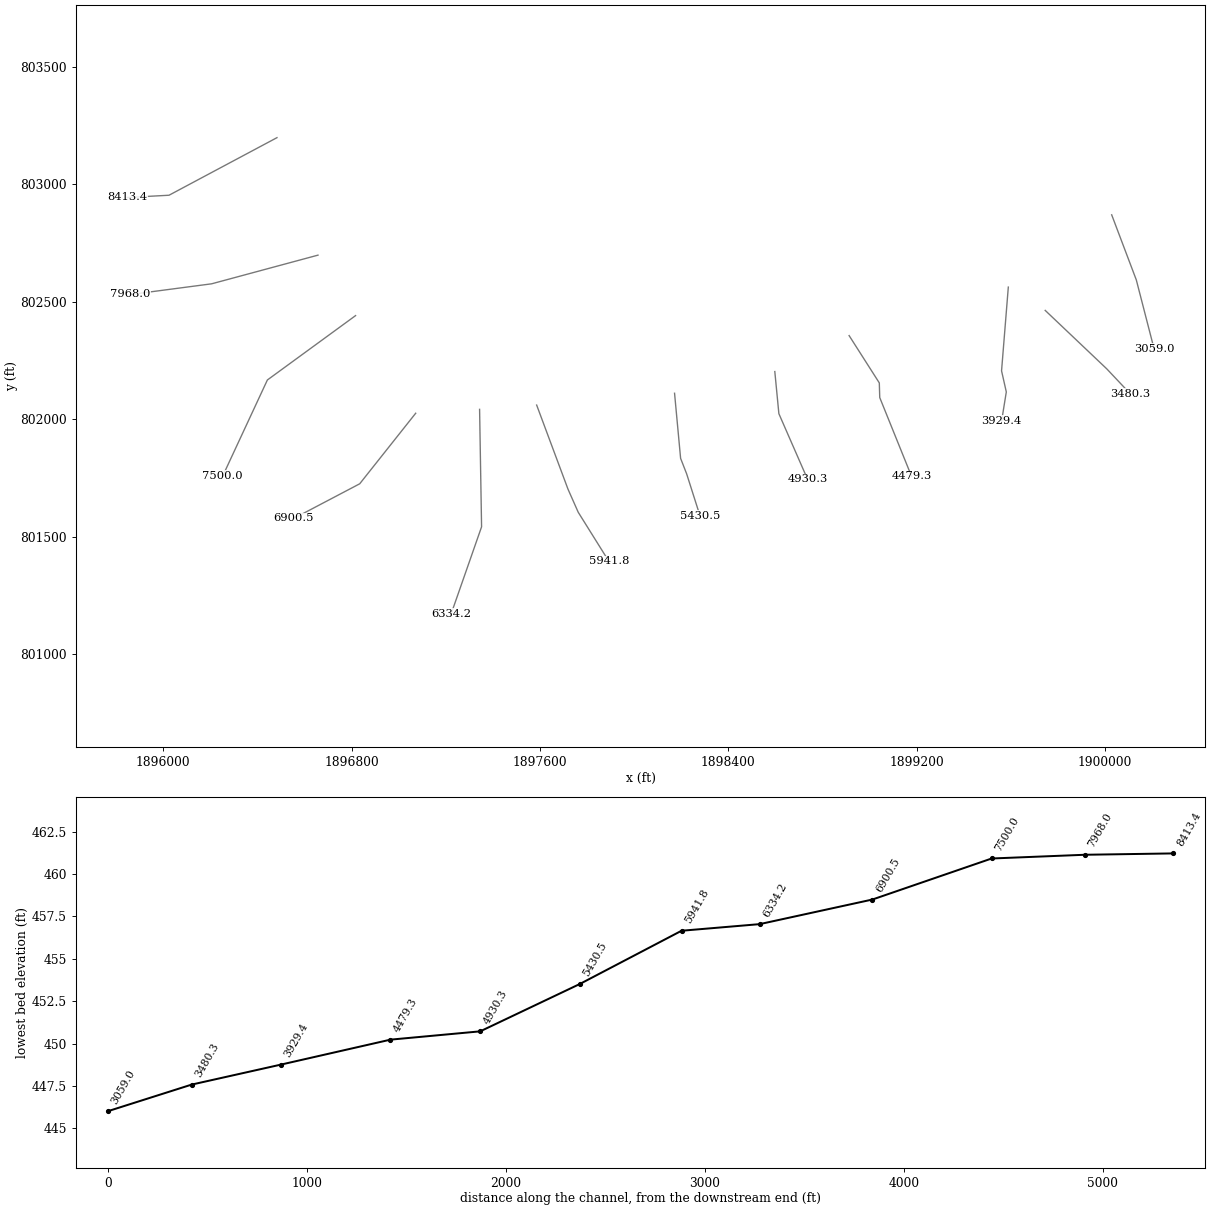
HEC-RAS study HAW RIVER TRIBUTARY 6.PRJ: Haw River Tributary 6

--- HAW RIVER TRIBUTARY 6.g01 (geometry) --- (continued)

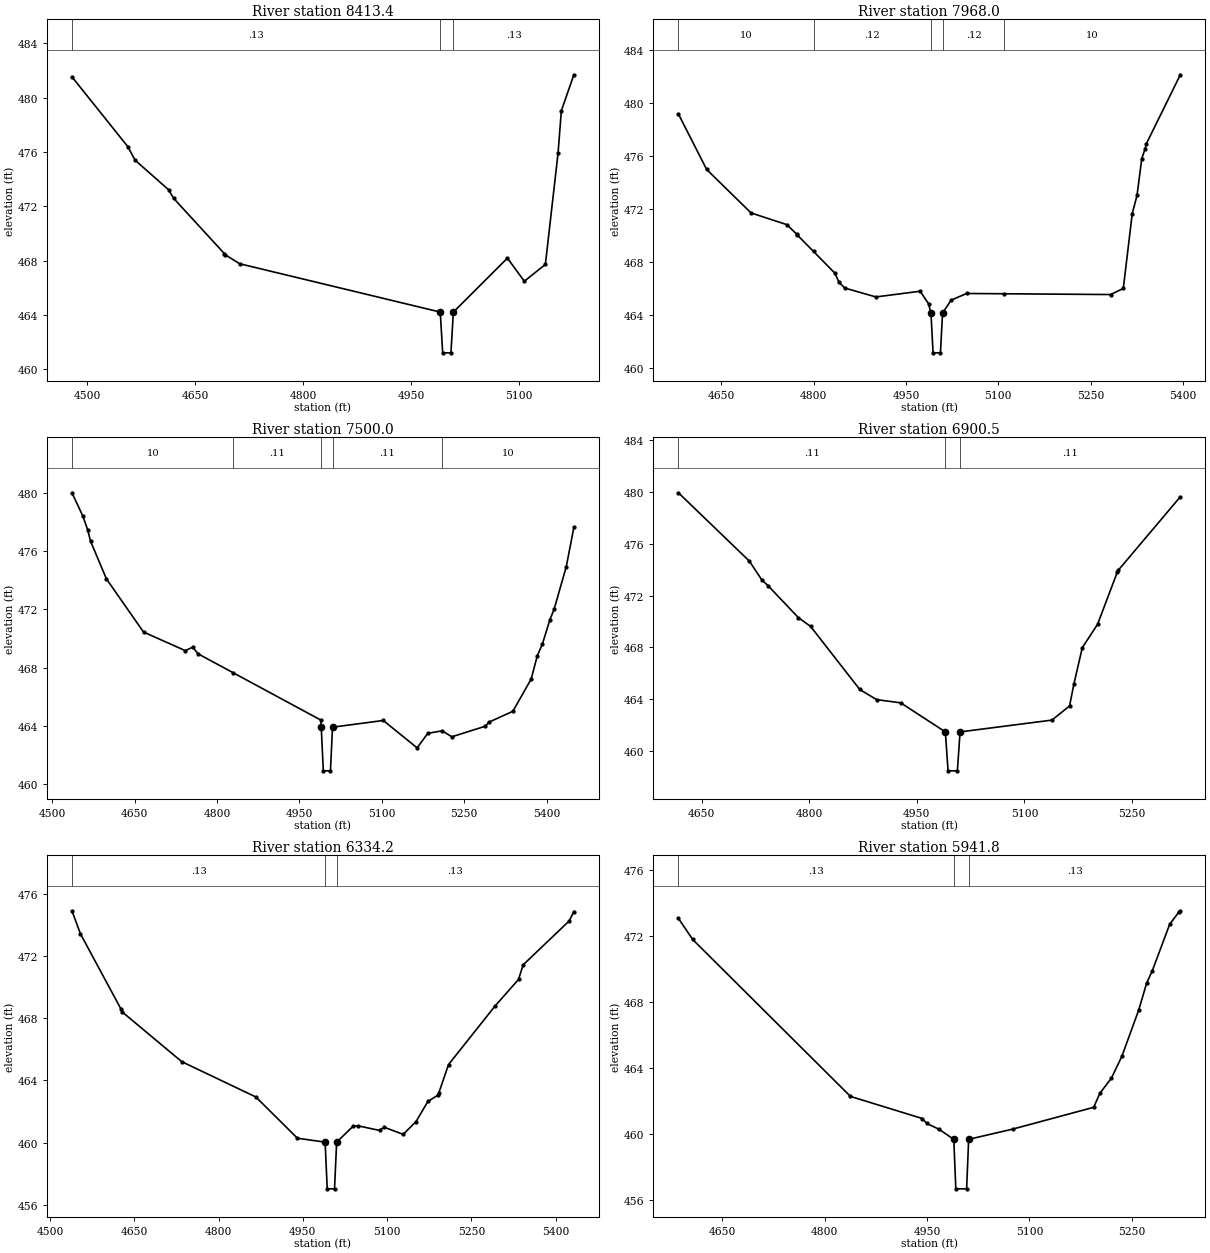
Type RM Length L Ch R = 1 ,8413.4,445.4,445.4,445.4
XS GIS Cut Line= 3
      1896482.86       803199.15      1896024.22       802954.04
      1895846.40       802944.44
BEGIN DESCRIPTION:
Haw River Tributary 6 17.0
END DESCRIPTION:
#Sta/Elev= 18
  4478.5  481.53  4556.2  476.39  4566.2   475.4  4612.8  473.22    4620  472.58
  4690.6  468.51  4691.4  468.44  4711.7  467.77 4990.78  464.21 4994.15  461.21
 5005.63  461.21    5009  464.21  5084.2  468.18  5107.7  466.48    5137  467.72
  5154.6   475.9  5159.2  479.03  5176.6  481.68
#Mann= 3 , 1 , 0
 4478.50    0.13       0 4990.78   0.042       0    5009    0.13       0
Bank Sta=4990.78,5009.00
Exp/Cntr=0.3,0.1

Type RM Length L Ch R = 1 ,7968.0,468,468,468
XS GIS Cut Line= 3
      1896657.10       802699.07      1896205.17       802576.97
      1895861.09       802531.53
BEGIN DESCRIPTION:
Haw River Tributary 6 16.0
END DESCRIPTION:
#Sta/Elev= 28
  4580.4  479.16  4626.3  474.97  4698.4  471.69  4756.3  470.81  4772.3   470.1
  4772.9  470.05  4799.9  468.78  4834.8  467.13    4841  466.47  4850.6  466.02
  4901.1  465.35    4973  465.78  4986.6  464.84 4990.57  464.13 4994.02  461.13
 5005.98  461.13 5009.43  464.13  5023.4  465.11  5048.5  465.61  5109.9  465.59
  5282.4  465.53    5303  465.99  5317.5  471.64  5325.3  473.02    5333   475.8
  5338.3  476.51  5340.6  476.93  5395.6  482.12
#Mann= 5 , 1 , 0
 4580.40      10       0  4799.9    0.12       0 4990.57   0.041       0
 5009.43    0.12       0  5109.9      10       0
Bank Sta=4990.57,5009.43
Exp/Cntr=0.3,0.1

Type RM Length L Ch R = 1 ,7500.0,599.5,599.5,599.5
XS GIS Cut Line= 3
      1896816.77       802441.67      1896442.11       802167.61
      1896252.79       801759.70
BEGIN DESCRIPTION:
Haw River Tributary 6 15.0
END DESCRIPTION:
#Sta/Elev= 30
  4535.8  480.02    4556  478.39  4564.6  477.45  4569.6   476.7  4598.6   474.1
  4666.1  470.45  4742.2  469.17  4755.7  469.41  4765.5  468.95  4829.9  467.64
  4988.9   464.4 4989.75  463.91  4993.5  460.91  5006.5  460.91 5010.25  463.91
  5102.7  464.37  5164.3  462.49  5183.8  463.49  5209.9  463.66  5227.5  463.25
  5288.8  463.98  5294.7  464.25  5338.6     465  5372.1  467.23  5383.2  468.83
  5392.4  469.62  5406.2  471.31  5413.7  472.01  5435.9  474.94  5449.7  477.64
#Mann= 5 , 1 , 0
 4535.80      10       0  4829.9    0.11       0 4989.75   0.041       0
 5010.25    0.11       0  5209.9      10       0
Bank Sta=4989.75,5010.25
Exp/Cntr=0.3,0.1

Type RM Length L Ch R = 1 ,6900.5,566.3,566.3,566.3
XS GIS Cut Line= 3
      1897072.12       802026.08      1896834.30       801725.72
      1896554.18       801578.22
BEGIN DESCRIPTION:
Haw River Tributary 6 14.0
END DESCRIPTION:
#Sta/Elev= 21
  4617.6  479.92  4716.4  474.66  4733.9   473.2  4742.4  472.77  4784.8   470.3
  4801.9  469.62  4870.4  464.76  4893.8  463.98  4927.5  463.73 4989.75  461.49
  4993.5  458.49  5006.5  458.49 5010.25  461.49  5138.3   462.4  5162.9  463.49
  5168.8  465.15  5180.7  467.99  5201.9  469.78  5229.3  473.78  5230.8  473.95
  5317.3  479.61
#Mann= 3 , 1 , 0
 4617.60    0.11       0 4989.75   0.041       0 5010.25    0.11       0
Bank Sta=4989.75,5010.25
Exp/Cntr=0.3,0.1

Type RM Length L Ch R = 1 ,6334.2,392.4,392.4,392.4
XS GIS Cut Line= 3
      1897343.55       802042.61      1897351.99       801542.55
      1897222.46       801171.23
BEGIN DESCRIPTION:
Haw River Tributary 6 13.0
END DESCRIPTION:
#Sta/Elev= 26
  4539.1   474.9  4554.2  473.42  4626.5  468.58  4628.3  468.41  4734.5  465.21
  4866.4  462.94  4940.5  460.29 4989.75  460.04  4993.5  457.04  5006.5  457.04
 5010.25  460.04  5039.3  461.05    5048  461.09  5086.8  460.79  5094.5     461
  5128.7  460.54  5151.6  461.36  5172.6  462.65  5190.2  463.05  5192.2  463.21
  5209.4  465.02  5291.7  468.76    5334  470.49  5342.3  471.43  5424.3  474.25
  5432.5  474.85
#Mann= 3 , 1 , 0
 4539.10    0.13       0 4989.75   0.042       0 5010.25    0.13       0
Bank Sta=4989.75,5010.25
Exp/Cntr=0.3,0.1

Type RM Length L Ch R = 1 ,5941.8,511.3,511.3,511.3
XS GIS Cut Line= 4
      1897585.94       802060.91      1897718.97       801703.10
      1897762.55       801604.48      1897892.51       801396.09
BEGIN DESCRIPTION:
Haw River Tributary 6 12.0
END DESCRIPTION:
#Sta/Elev= 21
  4585.9  473.04  4606.8  471.76  4837.9  462.25  4943.2  460.91  4949.7  460.61
  4967.6  460.26  4989.2  459.65  4992.2  456.65    5008  456.65    5011  459.65
  5075.5  460.27  5194.1  461.59  5203.2  462.44  5220.1  463.36  5235.4  464.68
  5260.1  467.49  5271.7  469.12  5280.1  469.88  5305.4  472.68  5319.2  473.44
    5321   473.5
#Mann= 3 , 1 , 0
 4585.90    0.13       0  4989.2   0.042       0    5011    0.13       0
Bank Sta=4989.20,5011.00
Exp/Cntr=0.3,0.1

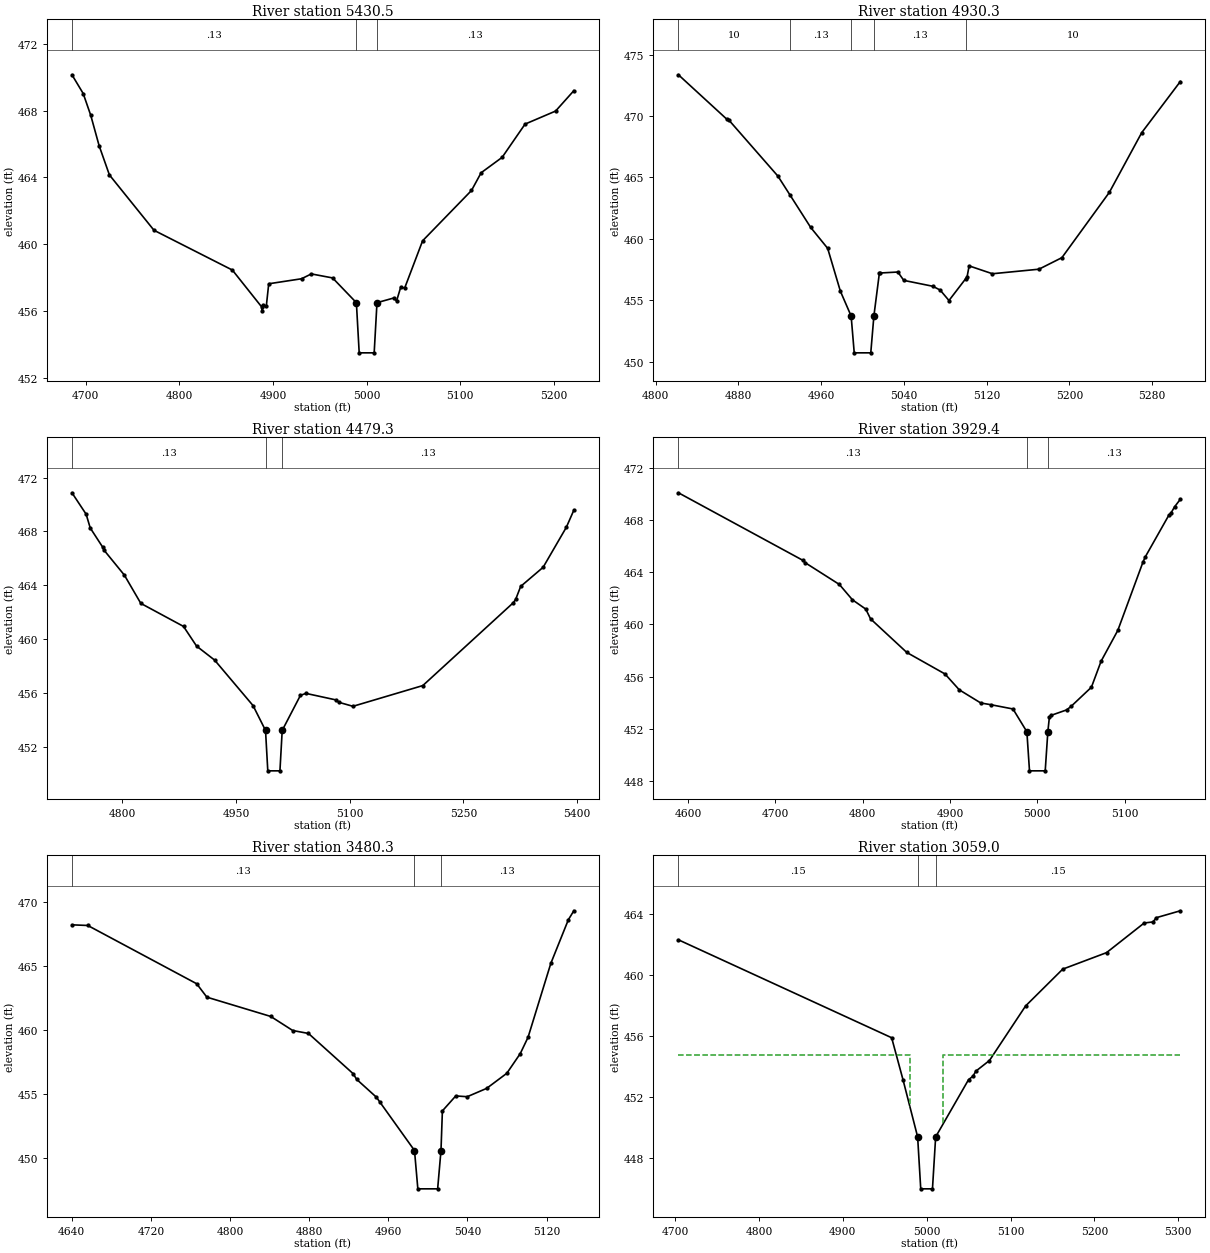
Type RM Length L Ch R = 1 ,5430.5,500.2,500.2,500.2
XS GIS Cut Line= 4
      1898171.73       802111.14      1898197.42       801834.07
      1898223.11       801768.01      1898279.65       801589.98
BEGIN DESCRIPTION:
Haw River Tributary 6 11.0
END DESCRIPTION:
#Sta/Elev= 30
  4685.3  470.14  4697.3  469.02  4705.4  467.71  4714.3   465.9  4725.3  464.15
  4772.9  460.84  4856.6  458.46  4888.1  456.24  4888.6  456.01  4888.8  456.37
  4892.8  456.29  4895.4  457.64  4930.4  457.94  4940.9  458.23  4963.6  457.99
    4989  456.51    4992  453.51    5008  453.51    5011  456.51  5028.9  456.79
  5031.9  456.61  5036.3  457.43  5040.6  457.39  5059.7  460.21  5111.9  463.22
  5122.2  464.28  5144.6   465.2  5169.1  467.19  5201.7  467.97  5221.2  469.19
#Mann= 3 , 1 , 0
 4685.30    0.13       0    4989   0.042       0    5011    0.13       0
Bank Sta=4989.00,5011.00
Exp/Cntr=0.3,0.1

Type RM Length L Ch R = 1 ,4930.3,451,451,451
XS GIS Cut Line= 3
      1898597.59       802203.51      1898614.85       802024.17
      1898736.90       801744.51
BEGIN DESCRIPTION:
Haw River Tributary 6 10.0
END DESCRIPTION:
#Sta/Elev= 28
    4822  473.36  4869.1  469.72  4870.8  469.67  4918.2  465.11  4929.9  463.57
  4949.9  460.93  4966.3  459.23  4978.6  455.74    4989  453.72    4992  450.72
    5008  450.72    5011  453.72  5016.3   457.2  5016.9  457.22  5034.2   457.3
  5039.9  456.62    5068  456.14  5075.1  455.83  5083.6  454.98  5099.9  456.77
  5101.1   456.9  5103.1   457.8  5125.6  457.16  5170.6  457.53  5192.8  458.47
  5238.7  463.79    5270  468.65  5307.3  472.81
#Mann= 5 , 1 , 0
 4822.00      10       0  4929.9    0.13       0    4989   0.042       0
    5011    0.13       0  5099.9      10       0
Bank Sta=4989.00,5011.00
Exp/Cntr=0.3,0.1

Type RM Length L Ch R = 1 ,4479.3,549.9,549.9,549.9
XS GIS Cut Line= 4
      1898913.20       802356.59      1899041.47       802155.18
      1899043.31       802092.79      1899178.04       801758.41
BEGIN DESCRIPTION:
Haw River Tributary 6 9.0
END DESCRIPTION:
#Sta/Elev= 27
  4733.8  470.87  4752.5  469.28  4757.9  468.26  4774.6  466.81  4776.1  466.61
  4802.9  464.76  4824.6  462.66  4880.9  460.95  4898.1  459.49  4921.9  458.45
  4972.6  455.07    4989  453.23    4992  450.23    5008  450.23    5011  453.23
    5035  455.83  5042.2  455.98  5081.4   455.5  5086.1  455.31  5104.3  455.02
  5196.4  456.56  5315.7  462.71  5318.8  462.96  5325.4  463.92    5355  465.34
  5385.6  468.31  5395.5  469.58
#Mann= 3 , 1 , 0
 4733.80    0.13       0    4989   0.042       0    5011    0.13       0
Bank Sta=4989.00,5011.00
Exp/Cntr=0.3,0.1

Type RM Length L Ch R = 1 ,3929.4,449.1,449.1,449.1
XS GIS Cut Line= 4
      1899589.48       802563.03      1899560.75       802206.55
      1899580.94       802116.64      1899561.01       801993.32
BEGIN DESCRIPTION:
Haw River Tributary 6 8.0
END DESCRIPTION:
#Sta/Elev= 30
    4589  470.11  4731.3  464.93  4734.4  464.73  4773.3  463.07  4788.3  461.89
  4803.5  461.18    4809  460.43  4850.5  457.85  4894.2   456.2  4910.6  454.98
  4935.2  453.97  4946.6  453.84  4972.1  453.51    4988  451.76    4991  448.76
    5009  448.76    5012  451.76  5013.8   452.9  5015.3  453.01  5033.6  453.44
  5038.8  453.72  5061.9  455.18    5073  457.18  5092.1  459.54    5121   464.8
  5123.6  465.19  5150.4  468.37  5152.7  468.52  5157.1  469.03  5163.7  469.61
#Mann= 3 , 1 , 0
 4589.00    0.13       0    4988   0.042       0    5012    0.13       0
Bank Sta=4988.00,5012.00
Exp/Cntr=0.3,0.1

Type RM Length L Ch R = 1 ,3480.3,421.3,421.3,421.3
XS GIS Cut Line= 3
      1899746.17       802463.76      1900007.63       802215.02
      1900107.98       802108.33
BEGIN DESCRIPTION:
Haw River Tributary 6 7.0
END DESCRIPTION:
#Sta/Elev= 25
  4640.2  468.24  4656.2  468.19  4766.3  463.63  4776.6  462.58  4841.2  461.07
  4863.4  459.97  4879.3  459.74  4924.5  456.59    4928  456.15    4948  454.75
  4951.4  454.38  4986.5  450.58 4989.88  447.58  5009.9  447.58 5013.28  450.58
  5014.7  453.68  5028.2  454.85  5039.8  454.79  5059.4  455.44  5079.8  456.62
  5093.4  458.16  5101.3  459.44  5124.3  465.22  5142.1  468.65  5147.6  469.34
#Mann= 3 , 1 , 0
 4640.20    0.13       0  4986.5   0.042       0 5013.28    0.13       0
Bank Sta=4986.50,5013.28
Exp/Cntr=0.3,0.1

Type RM Length L Ch R = 1 ,3059.0,40,40,40
XS GIS Cut Line= 3
      1900028.56       802870.68      1900133.22       802593.38
      1900208.60       802300.52
BEGIN DESCRIPTION:
Upstream Section of Bridge/Culvert/Weir
END DESCRIPTION:
#Sta/Elev= 18
  4703.8  462.31  4958.2   455.9  4971.9  453.12  4989.2  449.41  4992.9  446.01
  5006.9  446.01  5010.7  449.41    5050  453.16  5055.2  453.38  5058.6  453.71
  5074.9  454.41    5118  457.98  5162.3  460.39  5214.6  461.47  5259.5  463.41
  5269.9  463.48  5274.1  463.76  5302.6  464.21
#Mann= 3 , 1 , 0
 4703.80    0.15       0  4989.2   0.043       0  5010.7    0.15       0
#XS Ineff= 2 , 0
       0    4980   454.8    5020       0   454.8
Bank Sta=4989.20,5010.70
Exp/Cntr=0.5,0.3