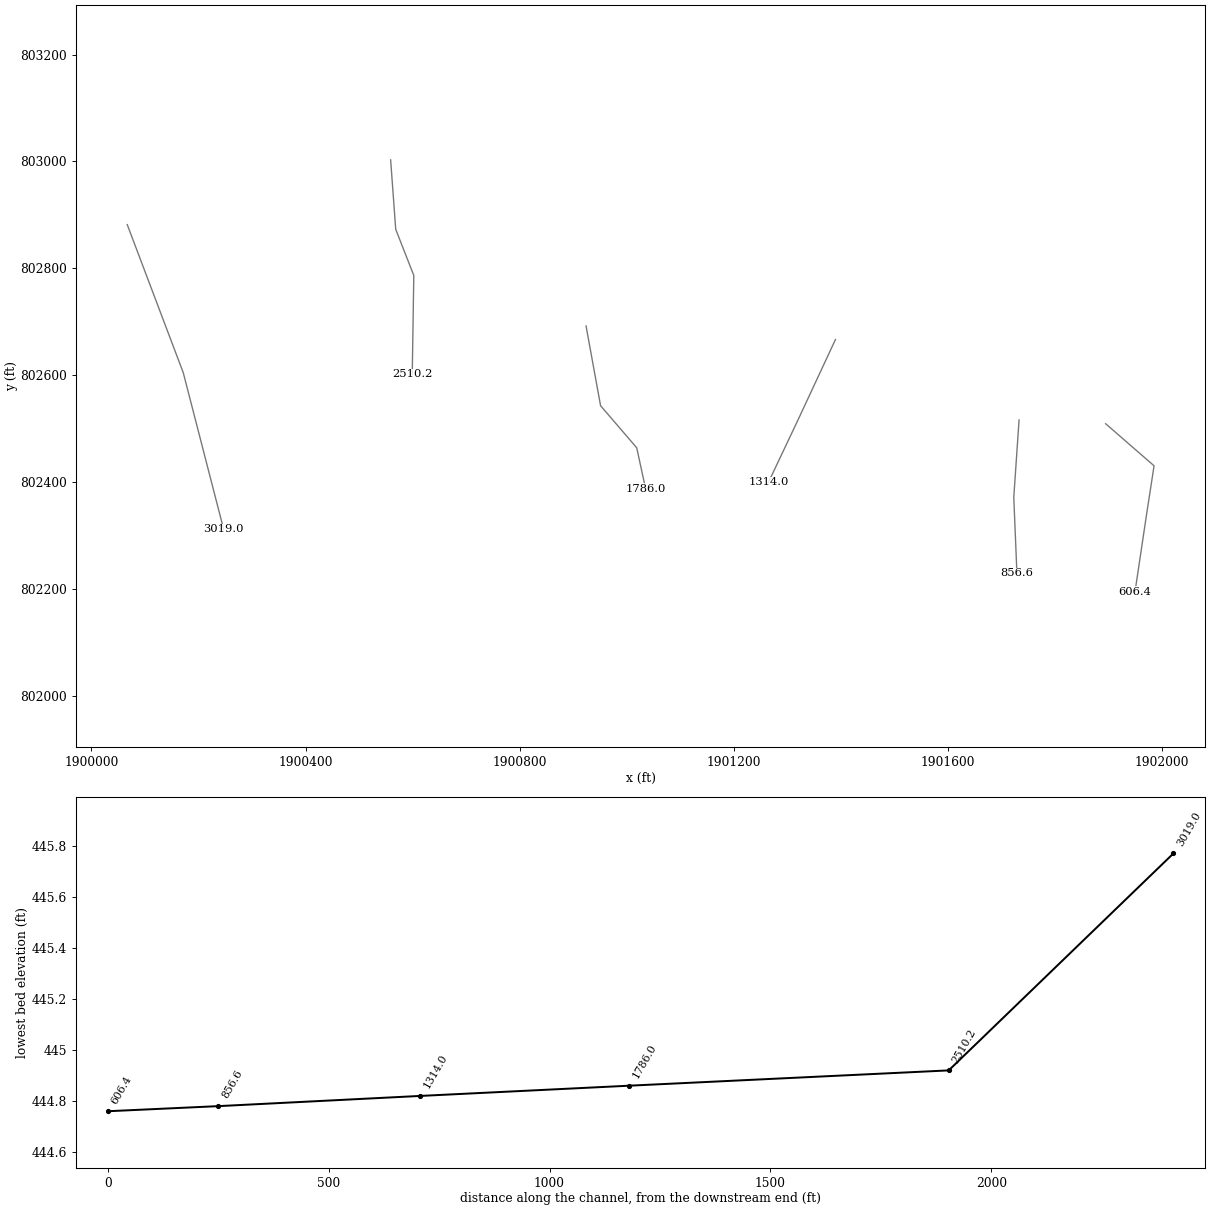
HEC-RAS study HAW RIVER TRIBUTARY 6.PRJ: Haw River Tributary 6

--- HAW RIVER TRIBUTARY 6.g01 (geometry) --- (continued)

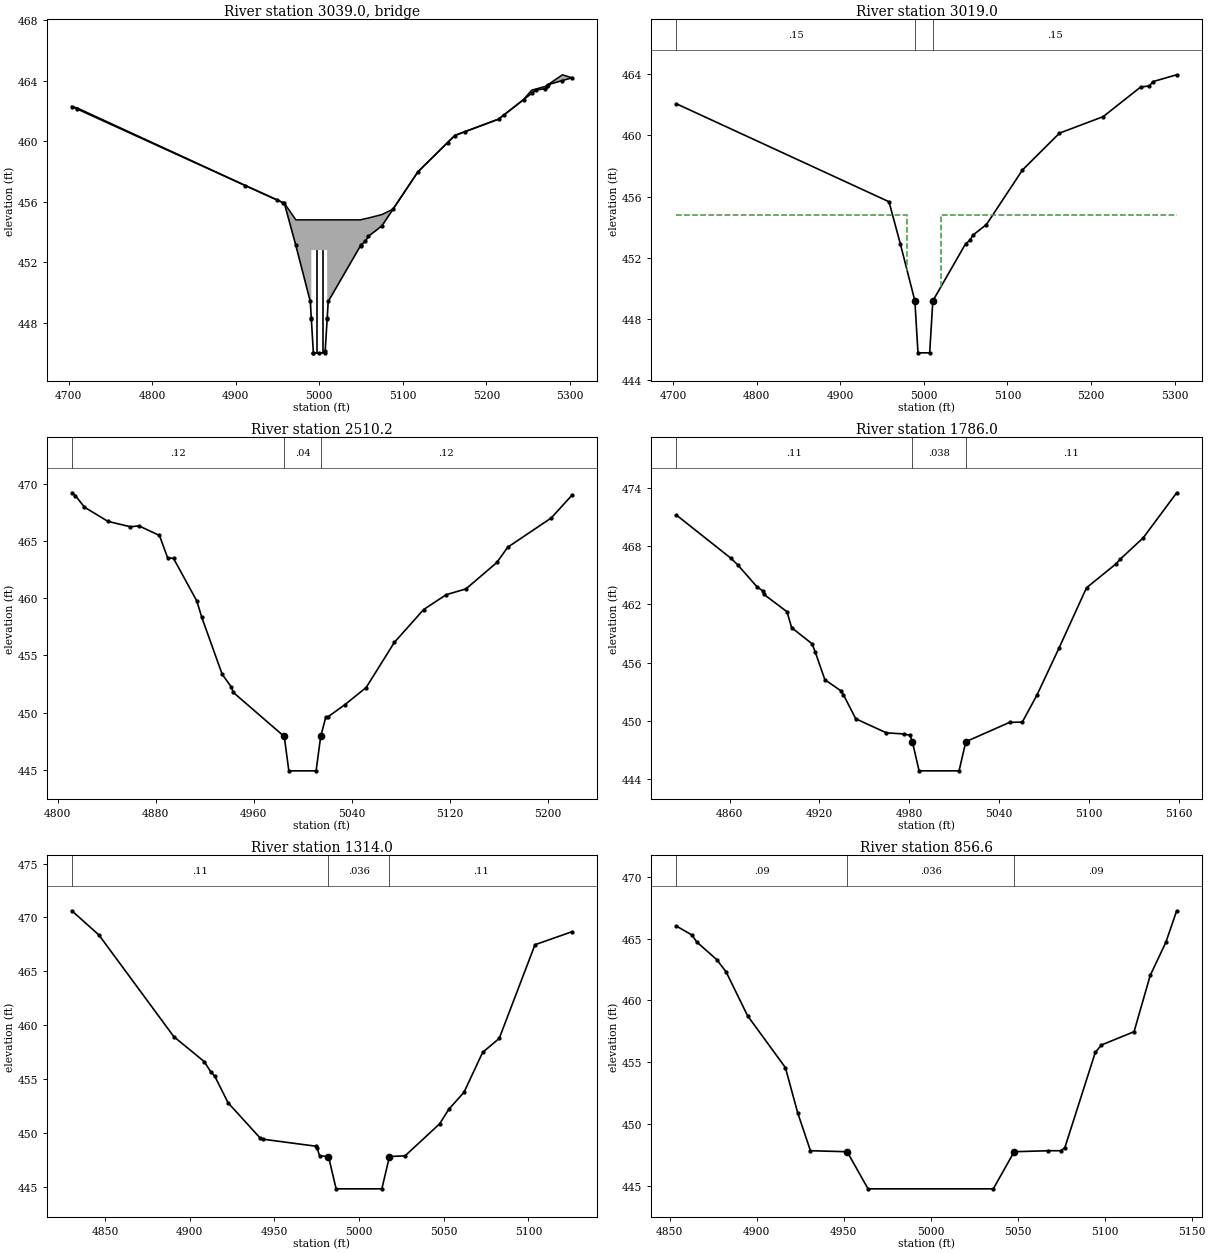
Type RM Length L Ch R = 3 ,3039.0,,,
BEGIN DESCRIPTION:
Haw River Tributary 6 - Rumley Rd
Structure ID: NCF-0207
Approximate Survey Structure
END DESCRIPTION:
Bridge Culvert--1,0,-1,-1, 0
Deck Dist Width WeirC Skew NumUp NumDn MinLoCord MaxHiCord MaxSubmerge Is_Ogee
10,20,2.6,,39,39,,,0.95,0,1,1,,
  4703.8  4710.4  4911.3  4948.8  4956.6  4958.2  4971.9  4989.2 4990.41  4990.5
  4992.9    4993    5000  5006.9    5007 5009.39  5009.5  5010.7  5049.5    5050
  5055.2  5058.6  5074.9  5088.1    5118  5153.6  5162.3  5174.8  5214.6  5220.6
  5244.5  5254.1  5259.5  5269.9  5272.5  5272.7  5274.1  5291.1  5302.6
   462.3   462.2  457.08  456.14  455.94   455.9   454.8   454.8   454.8   454.8
   454.8   454.8   454.8   454.8   454.8   454.8   454.8   454.8   454.8  454.81
  454.88  454.92  455.15   455.5  457.98  459.92  460.39  460.65  461.47  461.73
  462.76  463.38  463.46  463.62  463.66  463.66  463.76   464.4   464.2
   462.3  462.13  457.07  456.13  455.93  455.89  453.11   449.4  448.29   452.8
   452.8   452.8   452.8   452.8   452.8   452.8  448.33   449.4   453.1  453.15
  453.37   453.7   454.4  455.49  457.97  459.91  460.38  460.64  461.46  461.72
  462.75  463.17   463.4  463.47  463.64  463.66  463.75  464.02   464.2
  4703.8  4710.4  4911.3  4948.8  4956.6  4958.2  4971.9  4989.2 4990.41  4990.5
  4992.9    4993    5000  5006.9    5007 5009.39  5009.5  5010.7  5049.5    5050
  5055.2  5058.6  5074.9  5088.1    5118  5153.6  5162.3  5174.8  5214.6  5220.6
  5244.5  5254.1  5259.5  5269.9  5272.5  5272.7  5274.1  5291.1  5302.6
   462.3   462.2  457.08  456.14  455.94   455.9   454.8   454.8   454.8   454.8
   454.8   454.8   454.8   454.8   454.8   454.8   454.8   454.8   454.8  454.81
  454.88  454.92  455.15   455.5  457.98  459.92  460.39  460.65  461.47  461.73
  462.76  463.38  463.46  463.62  463.66  463.66  463.76   464.4   464.2
  462.05  461.88  456.82  455.88  455.68  455.64  452.86  449.15  448.04  452.55
  452.55  452.55  452.55  452.55  452.55  452.55  448.08  449.15  452.85   452.9
  453.12  453.45  454.15  455.24  457.72  459.66  460.13  460.39  461.21  461.47
   462.5  462.92  463.15  463.22  463.39  463.41   463.5  463.77  463.95
Pier Skew, UpSta & Num, DnSta & Num=,4996.5, 2 ,4996.5, 2 , 0 , 0 , 0 ,,
       1       1
     445   453.8
       1       1
  444.75  453.55
Pier Skew, UpSta & Num, DnSta & Num=,5003.5, 2 ,5003.5, 2 , 0 , 0 , 0 ,,
       1       1
     445   453.8
       1       1
  444.75  453.55
Abutment Skew #Up #Dn=, 2 , 2
 4990.30 4993.00
  452.80  446.00
 4990.30 4993.00
  452.55  445.75
Abutment Skew #Up #Dn=, 2 , 2
 5007.00 5009.59
  446.09  452.80
 5007.00 5009.59
  445.84  452.55
BR Coef= 1 , 1 , 0 ,1.25, 0 ,,,0.8,0,2,0,
Wspro=,,,, 1 ,,,, 0 ,,,, 0 ,,,,-1 ,-1 ,-1 , 0 , 0 , 0 , 0 , 0
BC Design=,, 0 ,, 0 ,,,,,,
BR U #Sta/Elev= 39
  4703.8   462.3  4710.4  462.13  4911.3  457.07  4948.8  456.13  4956.6  455.93
  4958.2  455.89  4971.9  453.11  4989.2   449.4 4990.41  448.29  4990.5  448.21
  4992.9     446    4993     446    5000     446  5006.9     446    5007  446.09
 5009.39  448.23  5009.5  448.33  5010.7   449.4  5049.5   453.1    5050  453.15
  5055.2  453.37  5058.6   453.7  5074.9   454.4  5088.1  455.49    5118  457.97
  5153.6  459.91  5162.3  460.38  5174.8  460.64  5214.6  461.46  5220.6  461.72
  5244.5  462.75  5254.1  463.17  5259.5   463.4  5269.9  463.47  5272.5  463.64
  5272.7  463.66  5274.1  463.75  5291.1  464.02  5302.6   464.2
BR U #Mann= 3
 4703.80    0.15  4989.2   0.043  5010.7    0.15
BR U Banks=4989.20,5010.70
BR D #Sta/Elev= 39
  4703.8  462.05  4710.4  461.88  4911.3  456.82  4948.8  455.88  4956.6  455.68
  4958.2  455.64  4971.9  452.86  4989.2  449.15 4990.41  448.04  4990.5  447.96
  4992.9  445.75    4993  445.75    5000  445.75  5006.9  445.75    5007  445.84
 5009.39  447.98  5009.5  448.08  5010.7  449.15  5049.5  452.85    5050   452.9
  5055.2  453.12  5058.6  453.45  5074.9  454.15  5088.1  455.24    5118  457.72
  5153.6  459.66  5162.3  460.13  5174.8  460.39  5214.6  461.21  5220.6  461.47
  5244.5   462.5  5254.1  462.92  5259.5  463.15  5269.9  463.22  5272.5  463.39
  5272.7  463.41  5274.1   463.5  5291.1  463.77  5302.6  463.95
BR D #Mann= 3
 4703.80    0.15  4989.2   0.043  5010.7    0.15
BR D Banks=4989.20,5010.70

Type RM Length L Ch R = 1 ,3019.0,508.8,508.8,508.8
XS GIS Cut Line= 3
      1900066.99       802881.75      1900171.66       802604.46
      1900247.03       802311.59
BEGIN DESCRIPTION:
Downstream Section of Bridge/Culvert/Weir
END DESCRIPTION:
#Sta/Elev= 18
  4703.8  462.07  4958.2  455.66  4971.9  452.88  4989.2  449.17  4992.9  445.77
  5006.9  445.77  5010.7  449.17    5050  452.92  5055.2  453.14  5058.6  453.47
  5074.9  454.17    5118  457.74  5162.3  460.15  5214.6  461.23  5259.5  463.17
  5269.9  463.24  5274.1  463.52  5302.6  463.97
#Mann= 3 , 1 , 0
 4703.80    0.15       0  4989.2   0.043       0  5010.7    0.15       0
#XS Ineff= 2 , 0
       0    4980   454.8    5020       0   454.8
Bank Sta=4989.20,5010.70
Exp/Cntr=0.5,0.3

Type RM Length L Ch R = 1 ,2510.2,724.2,724.2,724.2
XS GIS Cut Line= 4
      1900559.06       803002.92      1900568.54       802872.97
      1900602.31       802786.67      1900599.41       802601.26
BEGIN DESCRIPTION:
Haw River Tributary 6 5.0
END DESCRIPTION:
#Sta/Elev= 30
  4811.6  469.21  4814.4  468.97  4821.9  467.95  4841.1  466.71  4859.4  466.24
  4866.4  466.32  4883.1  465.48  4889.8  463.53  4894.6  463.48  4913.6  459.76
  4917.7  458.32  4934.3  453.36  4941.8  452.24  4943.3  451.78    4985  447.92
 4988.75  444.92    5011  444.92 5014.75  447.92  5018.9  449.61  5020.6  449.63
  5034.5   450.7  5051.9   452.2  5074.9  456.14  5098.8  459.01  5117.3  460.31
  5133.3  460.81  5158.6  463.12  5167.4  464.45    5203  467.01    5220  469.01
#Mann= 3 , 1 , 0
 4811.60    0.12       0    4985    0.04       0 5014.75    0.12       0
Bank Sta=4985.00,5014.75
Exp/Cntr=0.3,0.1

Type RM Length L Ch R = 1 ,1786.0,472,472,472
XS GIS Cut Line= 4
      1900924.13       802692.01      1900951.26       802542.78
      1901018.80       802463.98      1901035.38       802387.22
BEGIN DESCRIPTION:
Haw River Tributary 6 4.0
END DESCRIPTION:
#Sta/Elev= 30
  4824.5  471.19    4861  466.73  4865.4  466.07  4878.2  463.82    4882   463.4
  4882.9  463.03  4898.3  461.24  4901.4   459.6    4915  457.95  4917.1  457.12
  4923.6  454.24  4934.4  453.09    4936  452.69  4944.2  450.22  4964.7  448.77
  4976.2  448.66  4980.4  448.52    4982  447.86  4986.5  444.86  5013.2  444.86
  5017.7  447.86  5046.9  449.85  5055.4  449.88  5065.1  452.63  5079.9  457.49
  5098.3  463.71  5117.9  466.16  5120.8  466.65  5136.2  468.86  5158.5  473.49
#Mann= 3 , 1 , 0
 4824.50    0.11       0    4982   0.038       0  5017.7    0.11       0
Bank Sta=4982.00,5017.70
Exp/Cntr=0.3,0.1

Type RM Length L Ch R = 1 ,1314.0,457.4,457.4,457.4
XS GIS Cut Line= 3
      1901390.03       802666.62      1901319.95       802515.85
      1901264.81       802399.19
BEGIN DESCRIPTION:
Haw River Tributary 6 3.0
END DESCRIPTION:
#Sta/Elev= 24
  4830.5  470.62  4846.5  468.37  4890.7  458.94  4908.7  456.62  4912.5  455.67
  4914.8  455.29  4922.7  452.81  4941.6  449.54  4943.1  449.43  4974.8  448.77
  4975.3  448.62  4976.7  447.88    4982  447.82  4986.5  444.82  5013.5  444.82
    5018  447.82  5027.2  447.88  5047.6  450.85    5053   452.2    5062  453.78
    5073  457.48  5082.8  458.78  5103.9  467.47  5125.8  468.68
#Mann= 3 , 1 , 0
 4830.50    0.11       0    4982   0.036       0    5018    0.11       0
Bank Sta=4982.00,5018.00
Exp/Cntr=0.3,0.1

Type RM Length L Ch R = 1 ,856.6,250.2,250.2,250.2
XS GIS Cut Line= 3
      1901733.09       802516.11      1901723.21       802371.35
      1901729.06       802229.07
BEGIN DESCRIPTION:
Haw River Tributary 6 2.0
END DESCRIPTION:
#Sta/Elev= 22
  4853.9  466.01  4862.7   465.3  4865.7  464.71    4877  463.31  4882.4  462.32
  4894.8  458.76  4916.5  454.58  4923.6  450.91  4930.9  447.86    4952  447.78
    4964  444.78    5036  444.78    5048  447.78  5067.7  447.86  5074.8  447.86
  5077.1   448.1  5094.6   455.8  5098.1   456.4  5116.9  457.48  5126.2  462.03
  5135.2  464.71  5141.4  467.25
#Mann= 3 , 1 , 0
 4853.90    0.09       0    4952   0.036       0    5048    0.09       0
Bank Sta=4952.00,5048.00
Exp/Cntr=0.3,0.1

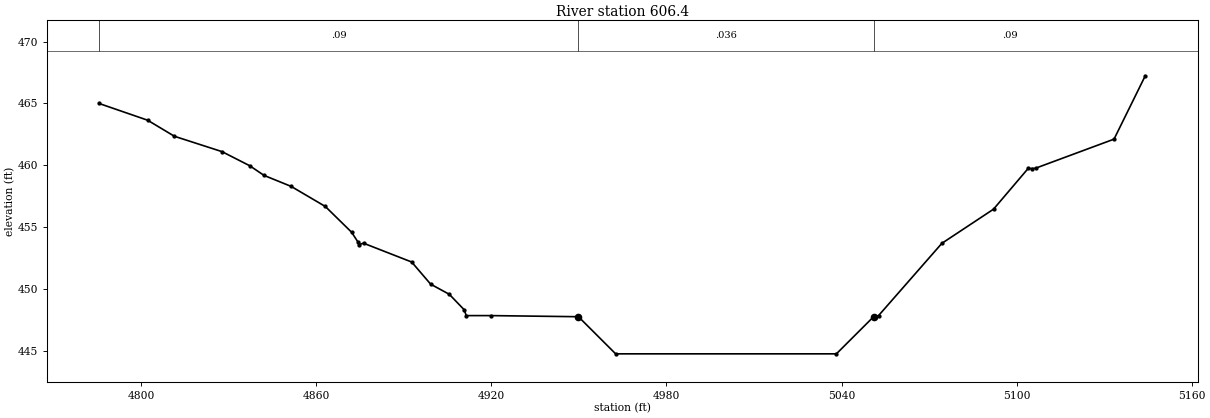
Type RM Length L Ch R = 1 ,606.4,0,0,0
XS GIS Cut Line= 4
      1901894.82       802509.06      1901985.31       802430.30
      1901970.91       802336.84      1901949.69       802194.44
BEGIN DESCRIPTION:
Haw River Tributary 6 1.0
END DESCRIPTION:
#Sta/Elev= 30
  4785.6  464.99  4802.2  463.64  4811.4  462.34  4827.7   461.1  4837.2  459.96
  4842.1  459.18  4851.4  458.29  4863.1  456.67  4872.1  454.59  4874.2  453.83
  4874.6  453.59  4876.2   453.7  4892.7  452.18  4899.2  450.39  4905.6  449.57
  4910.7  448.32  4911.4  447.85  4919.8  447.85 4949.85  447.76  4962.6  444.76
 5038.25  444.76    5051  447.76  5052.7  447.85  5074.4  453.69  5092.1  456.45
    5104  459.75  5105.3  459.73  5106.5  459.76  5133.4  462.11  5144.1  467.23
#Mann= 3 , 1 , 0
 4785.60    0.09       0 4949.85   0.036       0    5051    0.09       0
Bank Sta=4949.85,5051.00
Exp/Cntr=0.3,0.1

Chan Stop Cuts=-1