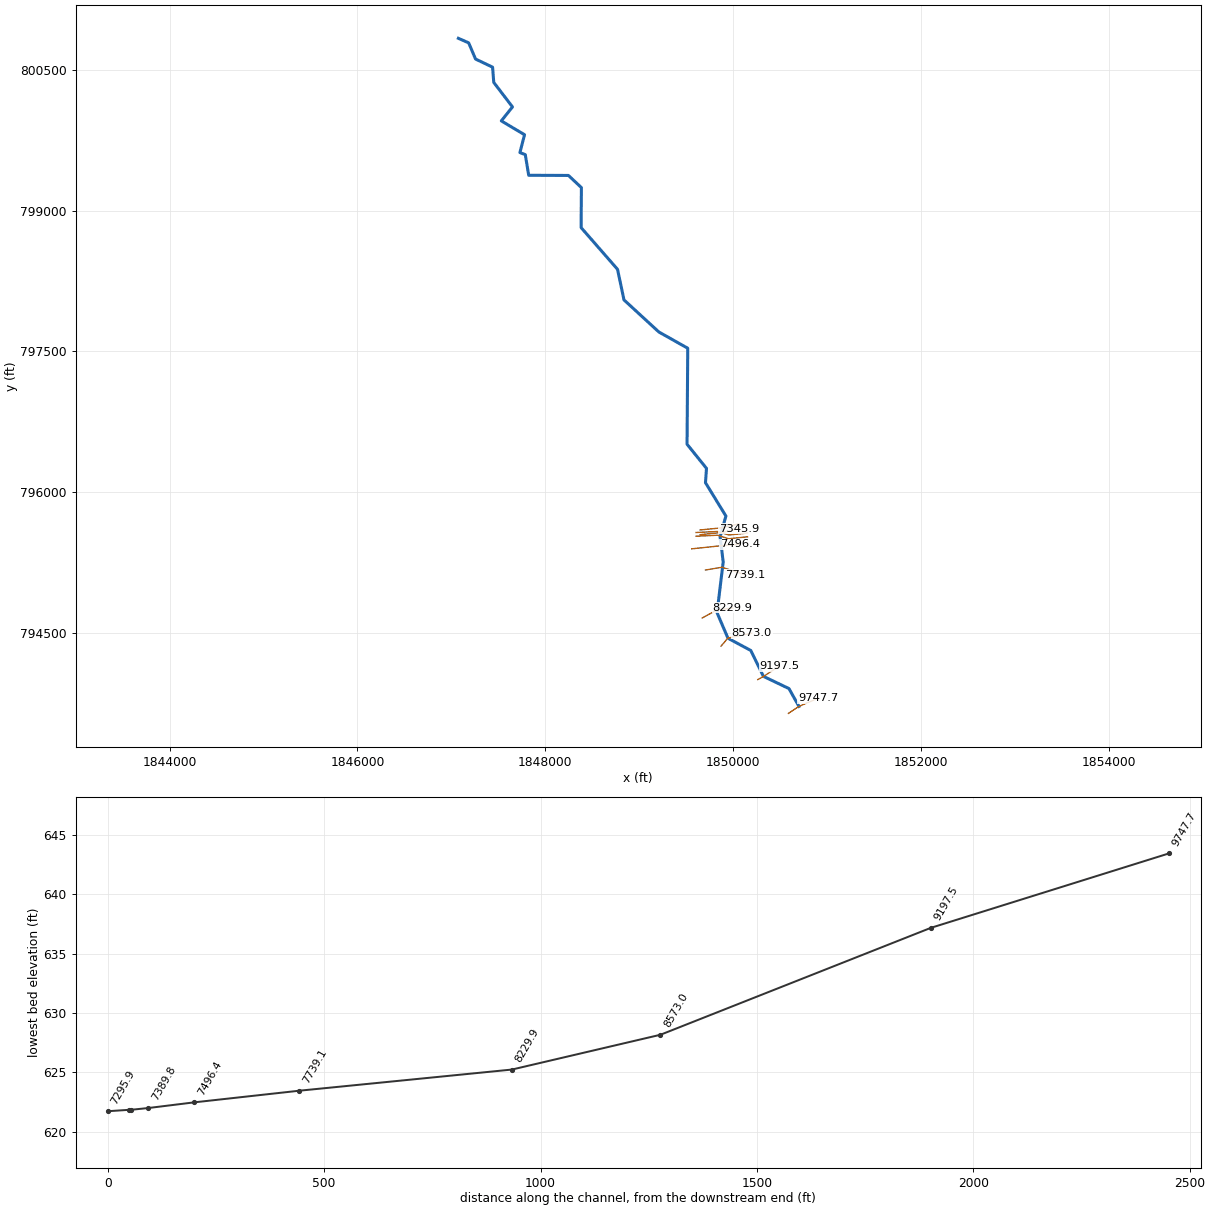
--- LITTLE CREEK TRIBUTARY 2.PRJ (project) ---

Proj Title=Little Creek Tributary 2
Current Plan=p01
Default Exp/Contr=0.3,0.1
English Units
Geom File=g01
Flow File=f01
Plan File=p01
Y Axis Title=Elevation
X Axis Title(PF)=Main Channel Distance
X Axis Title(XS)=Station
BEGIN DESCRIPTION:
Haw-Big Alamance
LITTLE CREEK TRIBUTARY 2
HCFCD Unit X###-##-##
Floodway Model
1% Event
Filename:  N:\NC_flood\60273\Approximates\Eng\Haw-Big_Alamance\Eng\Little Creek Tributary 2\Little Creek Tributary 2.prj
Prepared by:  ________     Date: ________
Reviewed by:  ________     Date: ________
STATUS (Draft RAS, SVSQ, FINAL)
END DESCRIPTION:
DSS Export Rating Curves= 0
DSS Export Rating Curve Sorted= 0
DSS Export Volume Flow Curves= 0
DXF OffsetX= 0
DXF OffsetY= 0
DXF ScaleX= 1
DXF ScaleY= 10

--- LITTLE CREEK TRIBUTARY 2.p01 (plan) ---

Plan Title=100-Year-Single
Program Version=3.10
Short Identifier=Plan01
Geom File=g01
Flow File=f01
Subcritical Flow
K Sum by GR= 0
Std Step Tol= 0.01
Critical Tol= 0.01
Num of Std Step Trials= 20
Max Error Tol= 0.3
Flow Tol Ratio= 0.001
Split Flow NTrial= 30
Split Flow Tol= 0.02
Split Flow Ratio= 0.02
Log Output Level= 0
Friction Slope Method= 1
Unsteady Friction Slope Method= 2
Parabolic Critical Depth
Global Vel Dist= 0 , 0 , 0
Global Log Level= 0
CheckData=True
Encroach Param=-1 ,0,0, 2
Encroach River=LittleCreekTribu
Encroach Reach=Reach - 1
Encroach Node=9747.7
       1 4986.14 5043.15
Encroach Node=9197.5
       1 4989.51 5029.87
Encroach Node=8573.0
       1 4988.42 5029.42
Encroach Node=8229.9
       1 4948.06  5033.5
Encroach Node=7739.1
       1    4950    5040
Encroach Node=7496.4
       1    4940    5040
Encroach Node=7389.8
       1    4940    5025
Encroach Node=7369.8
       4      .7
Encroach Node=7349.8
       1    4940    5025
Encroach Node=7345.9
       1    4945    5030
Encroach Node=7320.9
       4      .7
Encroach Node=7295.9
       1    4945    5030
Encroach Node=7015.1
       1    4970 5044.56
Encroach Node=6562.1
       1 4996.25 5028.13
Encroach Node=5956.4
       1 4978.88 5088.76
Encroach Node=5491.3
       1    4985    5060
Encroach Node=5095.7
       1    4975    5020
Encroach Node=5073.2
       1    4975    5020
Encroach Node=5050.7
       1    4975    5020
Encroach Node=4827.6
       1    4941    5015
Encroach Node=4504.1
       1    4940 5020.12
Encroach Node=4220.8
       1 4986.97 5039.73
Encroach Node=3548.2
       1 4978.54  5027.2
Encroach Node=3138.9
       1  4994.4  5079.9
Encroach Node=2689.8
       1 4946.99 5009.83
Encroach Node=2154.2
       1 4983.92 5020.22
Encroach Node=1599.9
       1 4962.44 5016.89
Encroach Node=995.0
       1  4943.8 5014.38
Encroach Node=380.0
       1    4980    5020
Encroach Node=172.3
       1 4989.94 5029.55
Computation Interval=1HOUR
Output Interval=1HOUR
Run HTab= 0
Run UNet= 0
Run PostProcess= 0
UNET Theta= 1
UNET Theta Warmup= 1
UNET ZTol= 0.02
UNET ZSATol= 0.05
UNET MxIter= 20
UNET MaxInSteps= 1
UNET DtIC= 0
UNET DtMin= 0
UNET MaxCRTS= 20
UNET WFStab= 2
UNET SFStab= 1
UNET WFX= 1
UNET SFX= 1
UNET DSS MLevel= 4
UNET Convert EG Bridges=-1
UNET Use Existing IB Tables=-1
UNET Froude Reduction=False
UNET Froude Limit= 1
UNET Froude Power= 10
Instantaneous Interval=1HOUR
Write IC File= 0
Echo Input=False
Echo Output=False
Write Detailed= 0

--- LITTLE CREEK TRIBUTARY 2.f01 (steady flow) ---

Flow Title= 100-Year-Single
Program Version=3.10
Number of Profiles= 2
Profile Names=100-Year,AFW
River Rch & RM=LittleCreekTribu,Reach - 1       ,9747.7
     863     863
River Rch & RM=LittleCreekTribu,Reach - 1       ,5050.7
    1020    1020
Boundary for River Rch & Prof#=LittleCreekTribu,Reach - 1       , 1
Up Type= 0
Dn Type= 3
Dn Slope=0.0076
DSS Import GetInterval= 0
DSS Import GetPeak= 0
DSS Import FillOption= 0

--- LITTLE CREEK TRIBUTARY 2.g01 (geometry) ---

Geom Title=Geom 01 by CodeH2 for Windows

River Reach=LittleCreekTribu,Reach - 1
Reach XY= 30
      1850702.17       793714.09      1850595.88       793903.94
      1850323.63       794034.56      1850189.25        794310.5
      1849946.12       794441.19      1849829.87       794713.44
      1849895.25       795254.31      1849862.63       795522.94
      1849924.25       795744.37       1849706.5       796100.12
      1849717.37       796252.63       1849510.5       796510.38
      1849517.75       797534.06      1849209.13       797708.31
      1848838.87       798049.56      1848769.87       798376.25
      1848382.13       798820.75      1848385.25       799247.19
      1848247.38       799377.13      1847824.12       799378.75
      1847787.63       799599.06       1847730.5       799621.25
      1847779.75        799811.5      1847532.38       799958.94
      1847651.25       800108.06         1847452       800369.25
      1847439.25       800531.94      1847257.87       800618.69
      1847184.87       800791.19       1847075.5        800839.5

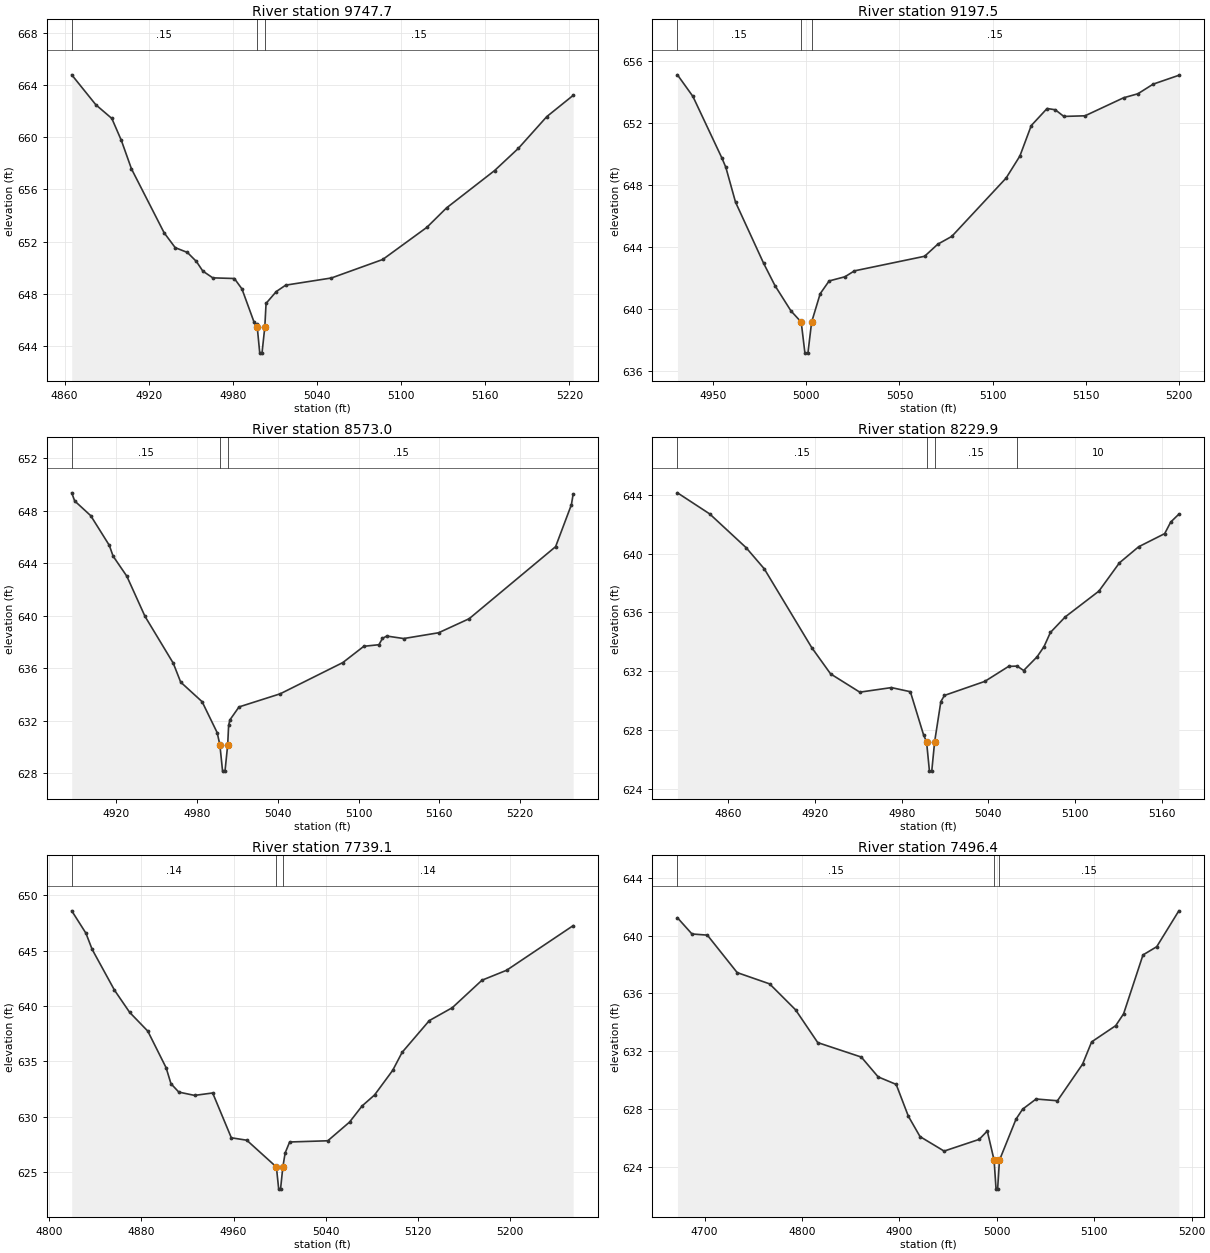
Type RM Length L Ch R = 1 ,9747.7,550.2,550.2,550.2
XS GIS Cut Line= 3
      1850589.76       793639.66      1850698.39       793712.37
      1850906.98       793801.70
BEGIN DESCRIPTION:
Little Creek Tributary 2 26.0
END DESCRIPTION:
#Sta/Elev= 30
  4865.1   664.8  4882.3   662.5  4893.7  661.45  4900.5  659.76  4907.7  657.58
    4931  652.67  4938.9  651.53  4947.6  651.16    4954  650.47  4958.6  649.73
  4965.7  649.21  4981.1  649.16  4986.5  648.36    4995  645.85  4997.1  645.43
  4997.2  645.66  4999.2  643.43  5000.8  643.43  5002.8  645.43  5003.7  647.25
    5011  648.16  5017.7  648.65  5050.3   649.2  5086.9  650.62  5118.4  653.09
  5132.4  654.58  5166.7  657.45  5183.7  659.16  5203.9  661.59  5222.7  663.22
#Mann= 3 , 1 , 0
 4865.10    0.15       0  4997.1    0.05       0  5002.8    0.15       0
Bank Sta=4997.10,5002.80
Exp/Cntr=0.3,0.1

Type RM Length L Ch R = 1 ,9197.5,624.5,624.5,624.5
XS GIS Cut Line= 3
      1850264.01       794000.16      1850325.43       794033.65
      1850491.62       794144.03
BEGIN DESCRIPTION:
Little Creek Tributary 2 25.0
END DESCRIPTION:
#Sta/Elev= 30
  4930.7  655.09    4939   653.7  4954.7   649.7  4956.7  649.13  4961.9  646.89
    4977  642.95  4983.1  641.51  4991.7  639.88  4997.2  639.16  4999.2  637.16
  5000.8  637.16  5002.8  639.16  5007.4  640.99  5012.2  641.81  5020.7  642.08
  5025.8  642.46  5063.5   643.4  5070.6  644.18  5078.1  644.68  5107.3  648.44
  5114.7  649.86  5120.8  651.82  5129.3  652.92  5133.7  652.84  5138.3  652.41
  5149.7  652.45  5170.4  653.61  5178.1  653.87  5186.3  654.49  5200.1  655.06
#Mann= 3 , 1 , 0
 4930.70    0.15       0  4997.2    0.05       0  5002.8    0.15       0
Bank Sta=4997.20,5002.80
Exp/Cntr=0.3,0.1

Type RM Length L Ch R = 1 ,8573.0,343.1,343.1,343.1
XS GIS Cut Line= 3
      1849872.48       794357.04      1849945.74       794442.56
      1850200.10       794494.89
BEGIN DESCRIPTION:
Little Creek Tributary 2 24.0
END DESCRIPTION:
#Sta/Elev= 30
    4887  649.36  4889.2  648.74  4901.1  647.62  4914.9  645.36  4917.7  644.54
  4927.9  643.01  4941.4  639.95  4962.4  636.38  4967.9  634.94  4983.8  633.45
    4995  631.09    4997  630.16    4999  628.16  5000.8  628.16  5002.8  630.16
  5003.5  631.65  5004.5  632.07  5011.2  633.05  5041.8  634.05  5088.3  636.43
  5103.9  637.67  5115.1  637.79  5117.7  638.27  5120.9  638.45  5133.5  638.26
  5159.4   638.7  5182.1  639.77  5246.3  645.26    5258  648.45  5259.3  649.25
#Mann= 3 , 1 , 0
 4887.00    0.15       0    4997    0.05       0  5002.8    0.15       0
Bank Sta=4997.00,5002.80
Exp/Cntr=0.3,0.1

Type RM Length L Ch R = 1 ,8229.9,490.8,490.8,490.8
XS GIS Cut Line= 3
      1849672.31       794657.53      1849826.66       794741.37
      1849996.38       794764.79
BEGIN DESCRIPTION:
Little Creek Tributary 2 23.0
END DESCRIPTION:
#Sta/Elev= 30
  4824.8  644.12  4847.1  642.69  4872.3   640.4  4884.9  638.96  4917.7  633.62
  4930.8  631.83    4951  630.59  4972.9   630.9    4986  630.62  4995.2  627.67
  4997.2  627.23  4999.2  625.23  5000.8  625.23  5002.8  627.23  5007.1  629.95
  5009.6  630.37  5037.5  631.32    5054  632.34  5059.9  632.36  5064.4  632.06
  5073.7  632.99  5078.5  633.68  5082.9  634.64  5093.2   635.7  5116.5  637.45
  5130.7  639.37    5144  640.46    5162  641.35  5166.2  642.14  5171.8  642.67
#Mann= 4 , 1 , 0
 4824.80    0.15       0  4997.2    0.05       0  5002.8    0.15       0
  5059.9      10       0
Bank Sta=4997.20,5002.80
Exp/Cntr=0.3,0.1

Type RM Length L Ch R = 1 ,7739.1,242.7,242.7,242.7
XS GIS Cut Line= 3
      1849706.54       795168.74      1849882.97       795198.35
      1850126.47       795118.53
BEGIN DESCRIPTION:
Little Creek Tributary 2 22.0
END DESCRIPTION:
#Sta/Elev= 30
  4819.6   648.6  4831.9  646.58  4837.3  645.12  4856.7  641.43  4869.9  639.42
  4885.6  637.73  4901.5  634.42  4905.7  632.98  4912.5  632.22  4926.2  631.92
  4941.9  632.14  4958.1  628.09  4971.5  627.87  4997.2  625.45  4999.2  623.45
  5000.8  623.45  5002.8  625.45  5004.8  626.72  5008.7  627.71  5041.8  627.82
  5060.7  629.51  5071.6  630.97  5082.4  631.96  5098.1  634.18  5106.3  635.81
  5129.9  638.68  5149.9  639.85  5175.6  642.33    5197  643.23  5254.7  647.26
#Mann= 3 , 1 , 0
 4819.60    0.14       0  4997.2    0.05       0  5002.8    0.14       0
Bank Sta=4997.20,5002.80
Exp/Cntr=0.3,0.1

Type RM Length L Ch R = 1 ,7496.4,106.6,106.6,106.6
XS GIS Cut Line= 3
      1849560.48       795394.68      1849886.89       795429.19
      1850072.64       795444.60
BEGIN DESCRIPTION:
Little Creek Tributary 2 21.0
END DESCRIPTION:
#Sta/Elev= 30
  4672.2  641.23  4687.1  640.11  4702.9  640.03  4733.5  637.44  4766.8  636.66
  4793.4  634.87  4816.2   632.6  4860.9   631.6  4878.2  630.23  4896.7  629.71
  4909.2  627.51  4921.2   626.1  4945.9   625.1  4981.9  625.91  4990.2  626.49
  4997.2  624.47  4999.2  622.47  5000.8  622.47  5002.7  624.47  5019.7  627.31
  5026.5     628  5040.3   628.7  5062.2  628.58    5088  631.11  5097.3  632.65
    5122  633.77  5130.1  634.59    5150  638.66  5164.1  639.23  5186.8  641.71
#Mann= 3 , 1 , 0
 4672.20    0.15       0  4997.2    0.05       0  5002.7    0.15       0
Bank Sta=4997.20,5002.70
Exp/Cntr=0.5,0.3

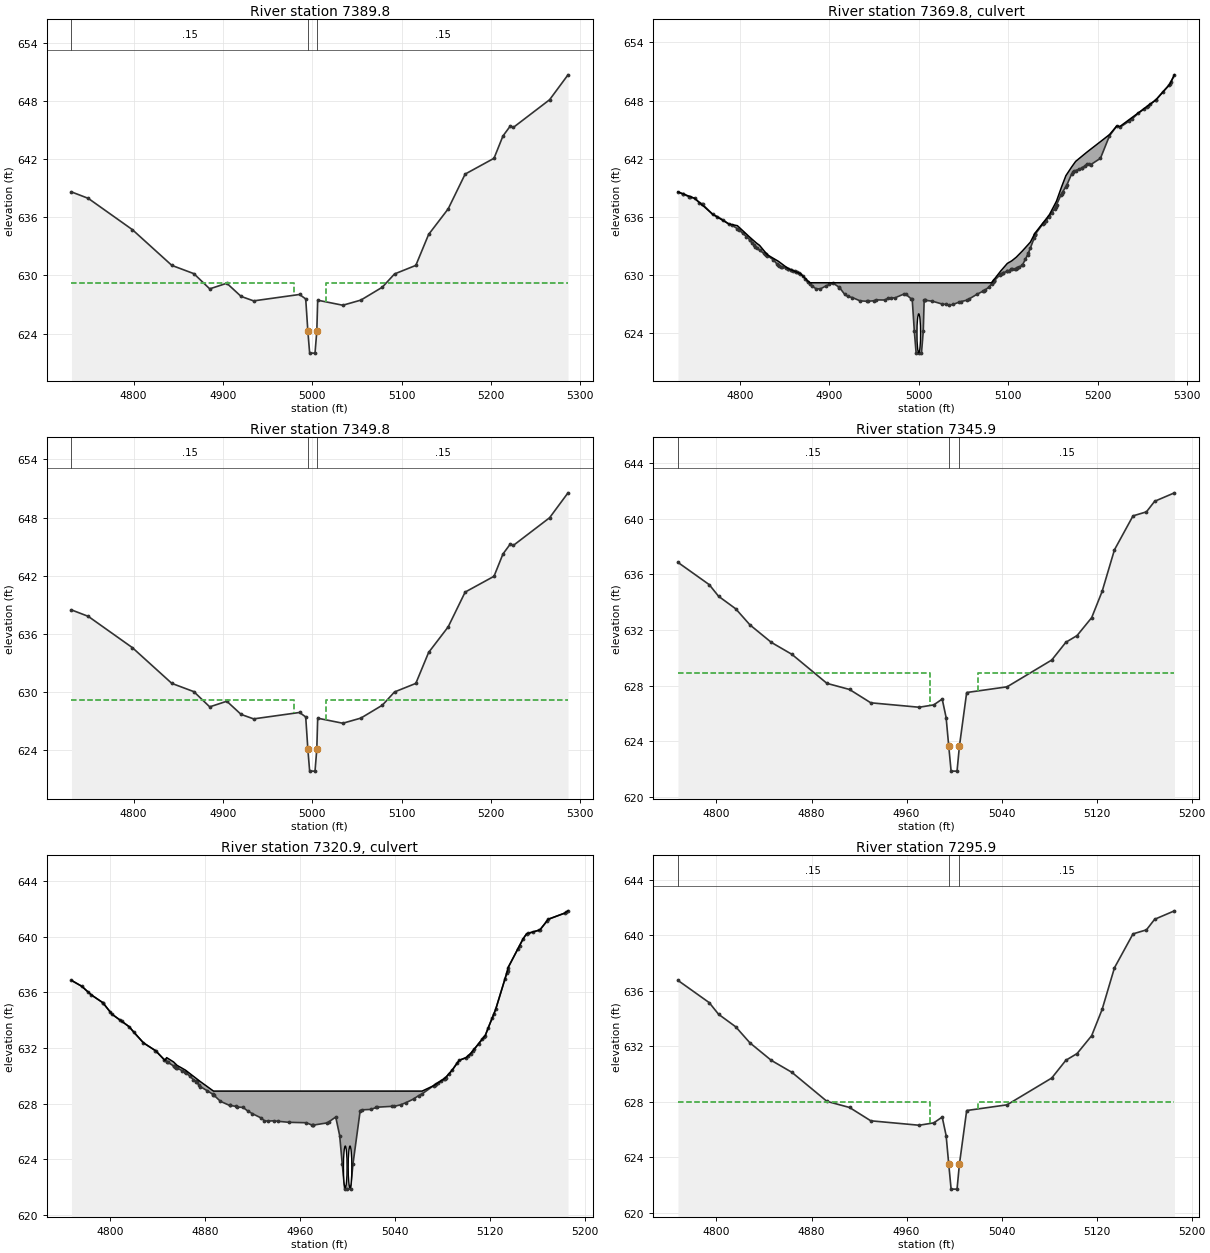
Type RM Length L Ch R = 1 ,7389.8,40,40,40
XS GIS Cut Line= 4
      1849606.08       795528.87      1849837.00       795539.68
      1849953.99       795502.19      1850154.48       795523.10
BEGIN DESCRIPTION:
Upstream Section of Bridge/Culvert/Weir
END DESCRIPTION:
#Sta/Elev= 30
  4730.5  638.62  4749.2  637.96  4798.6  634.73  4842.8  631.04  4867.4  630.19
  4885.2  628.62  4904.3   629.2  4920.3  627.84  4934.3  627.38  4985.7  628.04
  4992.6  627.58    4995  624.24    4997  621.99    5003  621.99    5005  624.24
    5006  627.45  5034.1  626.93  5054.3  627.46  5078.3  628.79    5092  630.16
  5115.8  631.04  5130.1  634.23    5152  636.87    5171  640.46  5203.3  642.09
  5213.3  644.39  5221.6  645.43    5225  645.28  5265.5  648.13  5286.1   650.7
#Mann= 3 , 1 , 0
 4730.50    0.15       0    4995    0.05       0    5005    0.15       0
#XS Ineff= 2 , 0
       0    4980   629.2    5015       0   629.2
Bank Sta=4995.00,5005.00
Exp/Cntr=0.5,0.3

Type RM Length L Ch R = 2 ,7369.8,,,
BEGIN DESCRIPTION:
Private Rd1-TOR
Structure ID: NCF-0046
Approximate Survey Structure
END DESCRIPTION:
Bridge Culvert--1,0,-1,-1, 0
Deck Dist Width WeirC Skew NumUp NumDn MinLoCord MaxHiCord MaxSubmerge Is_Ogee
10,20,3,, 60, 60,,,0.95,0,1,1,,
  4730.5  4749.2  4769.5  4787.5    4797    4811  4818.4  4821.8  4830.5  4837.4
  4842.8    4854  4867.4    4878  4885.2    4890  4904.3  4911.2    4917  4920.3
  4934.3    4962    4966  4985.7  4992.6    4995    4997    5003    5005    5006
  5034.1  5038.3  5054.3  5073.8  5081.4    5092  5099.1    5104  5109.1  5115.8
  5122.1  5124.9    5129  5130.1    5146    5152  5154.1  5159.8  5164.6    5171
  5175.5  5187.9  5192.2  5203.3  5213.3  5221.6    5225  5265.5  5280.5  5286.1
  638.57  637.91  636.25  635.26  635.09  633.89  633.29  633.06  632.09  631.71
  631.42  630.65  630.14   629.2   629.2   629.2   629.2   629.2   629.2   629.2
   629.2   629.2   629.2   629.2   629.2   629.2   629.2   629.2   629.2   629.2
   629.2   629.2   629.2   629.2   629.2  630.45   631.2  631.46  631.84  632.47
  633.11   633.4  634.14  634.33   636.2  637.25  637.63   639.1  640.25  641.14
  641.72  642.66  642.97  643.76  644.48  645.38  645.32  648.08  649.63  650.65
  638.57  637.91  636.25  635.26  634.78  633.63  632.79  632.56  632.01  631.55
  630.99  630.63  630.14  629.05  628.57  628.57  629.15  628.71  628.01  627.79
  627.33  627.42  627.62  627.99  627.53  624.19  621.94  621.94  624.19   627.4
  626.88  626.96  627.41  628.42  629.09  630.11  630.39  630.65  630.64  630.99
  632.11   632.8  633.78  634.18  636.05  636.82  637.25   638.4  639.12  640.41
  640.77  641.41  641.37  642.04  644.34  645.38  645.23  648.08  649.63  650.65
  4730.5  4749.2  4769.5  4787.5    4797    4811  4818.4  4830.5  4837.4  4842.8
  4857.2  4867.4    4878  4885.2    4890  4904.3  4911.2    4917  4920.3  4934.3
    4962  4985.7  4992.6    4995    4997    5003    5005    5006  5034.1  5038.3
  5054.3  5073.8  5081.4    5092  5099.1    5104  5109.1  5115.8  5122.1  5124.9
    5129  5130.1  5139.7    5146    5152  5154.1  5159.8  5164.6    5171  5175.5
  5187.9  5192.2  5203.3  5213.3  5221.6    5225  5251.9  5265.5  5280.5  5286.1
  638.52  637.86   636.2  635.21  635.09  633.89  633.29  632.09  631.71  631.42
  630.45   630.1   629.2   629.2   629.2   629.2   629.2   629.2   629.2   629.2
   629.2   629.2   629.2   629.2   629.2   629.2   629.2   629.2   629.2   629.2
   629.2   629.2   629.2  630.45   631.2  631.46  631.84  632.47  633.11   633.4
  634.14  634.33  635.33   636.2  637.25  637.63   639.1  640.25  641.14  641.72
  642.66  642.97  643.76  644.48  645.34  645.32  647.24  648.03  649.58   650.6
  638.47  637.81  636.15  635.16  634.68  633.53  632.69  631.91  631.45  630.89
  630.39  630.04  628.95  628.47  628.47  629.05  628.61  627.91  627.69  627.23
  627.32  627.89  627.43  624.09  621.84  621.84  624.09   627.3  626.78  626.86
  627.31  628.32  628.99  630.01  630.29  630.55  630.54  630.89  632.01   632.7
  633.68  634.08  635.28  635.95  636.72  637.15   638.3  639.02  640.31  640.67
  641.31  641.27  641.94  644.24  645.28  645.13  647.01  647.98  649.53  650.55
BR Coef= 1 , 0 , 0 ,1.25, 0 ,,,0.8,-1,2,0,
Wspro=,,,, 1 ,,,, 0 ,,,, 0 ,,,,-1 ,-1 ,-1 , 0 , 0 , 0 , 0 , 0
Culvert=1,4.0,,20.0,0.024,0.5,1.0,2,1,621.99,4999.96,621.84,4999.96,Culvert #1  ,0,10
BC Design=,, 0 ,, 0 ,,,,,,
BR U #Sta/Elev= 170
  4730.5  638.57  4735.9  638.37  4736.2  638.35  4742.8  638.08  4743.8  638.06
  4749.2  637.91  4754.5  637.46  4756.9  637.35  4758.1  637.28  4769.5  636.25
  4774.7  636.02  4780.4  635.71  4787.5  635.26  4790.7  635.15    4797  634.78
  4798.6  634.68  4803.2  634.29  4807.1  633.96    4811  633.63  4811.3   633.6
  4813.5  633.33  4815.4  633.11  4817.2  632.91  4818.4  632.79  4821.8  632.56
  4826.6  632.23  4828.3  632.16  4828.9  632.12  4829.5  632.08  4830.5  632.01
  4837.4  631.55  4841.3  631.13  4842.8  630.99  4843.7  630.95  4845.4  630.86
  4846.9  630.82  4851.6  630.69  4853.9  630.63    4854  630.63  4857.2  630.49
  4857.3  630.49  4859.3  630.44  4861.6  630.39  4862.7  630.36  4864.1  630.31
  4866.2   630.2  4867.4  630.14  4870.5  629.89  4873.2  629.55  4875.7  629.23
    4878  629.05  4880.2  628.87  4885.2  628.57    4890  628.57  4895.9  628.86
  4899.9  629.02  4904.3  629.15  4910.6  628.75  4911.2  628.71    4917  628.01
  4920.3  627.79  4925.8  627.67  4934.3  627.33  4942.5  627.29  4943.6   627.3
  4949.8  627.34  4952.5  627.43    4962  627.42    4966  627.62  4968.9  627.61
  4973.6  627.66  4983.3  628.03  4985.7  627.99  4991.8  627.52  4992.6  627.53
    4995  624.19    4997  621.94    5000  621.94    5003  621.94    5005  624.19
    5006   627.4  5006.7  627.41    5007  627.39  5015.1   627.3  5025.5  627.02
  5030.4  626.96  5034.1  626.88  5038.3  626.96  5045.4  627.21  5047.3  627.26
  5054.3  627.41    5056  627.51  5065.1  628.01  5072.3  628.35  5073.1  628.38
  5073.8  628.42  5078.3  628.74  5081.4  629.09  5082.7  629.24  5083.3  629.31
    5084  629.39  5084.5  629.43  5084.7  629.45    5091  630.02    5092  630.11
  5094.1  630.21  5094.5  630.23  5099.1  630.39  5099.2  630.39  5100.6  630.42
    5103  630.58    5104  630.65  5107.8  630.62  5109.1  630.64  5109.6  630.68
  5110.4  630.75  5111.8  630.81  5115.8  630.99  5116.3  631.08  5119.2   631.6
  5122.1  632.11  5122.5  632.22  5124.9   632.8    5129  633.78    5130  634.14
  5130.1  634.18  5130.5  634.23    5139  635.29  5139.7  635.38  5142.3  635.59
  5145.8  636.03    5146  636.05  5148.8  636.43    5152  636.82    5153  637.02
  5154.1  637.25    5159  638.24  5159.8   638.4  5160.9  638.56  5164.6  639.12
  5165.6  639.27    5171  640.41  5172.5  640.58  5173.5  640.69  5175.5  640.77
  5179.4  640.92  5182.6  641.04    5183  641.06  5186.2  641.29  5187.9  641.41
  5190.2  641.46  5192.2  641.37  5203.3  642.04  5213.3  644.34  5221.6  645.38
    5225  645.23  5235.5  645.88  5238.6  646.09  5245.8   646.7  5251.9  647.11
  5255.4  647.35  5256.4  647.42  5258.8  647.59  5265.3  648.07  5265.5  648.08
  5273.4  648.93  5280.5  649.63  5280.8  649.67  5282.1  649.92  5286.1  650.65
BR U #Mann= 3
 4730.50    0.15    4995    0.05    5005    0.15
BR U Banks=4995.00,5005.00
BR D #Sta/Elev= 170
  4730.5  638.47  4735.9  638.27  4736.2  638.25  4742.8  637.98  4743.8  637.96
  4749.2  637.81  4754.5  637.36  4756.9  637.25  4758.1  637.18  4769.5  636.15
  4774.7  635.92  4780.4  635.61  4787.5  635.16  4790.7  635.05    4797  634.68
  4798.6  634.58  4803.2  634.19  4807.1  633.86    4811  633.53  4811.3   633.5
  4813.5  633.23  4815.4  633.01  4817.2  632.81  4818.4  632.69  4821.8  632.46
  4826.6  632.13  4828.3  632.06  4828.9  632.02  4829.5  631.98  4830.5  631.91
  4837.4  631.45  4841.3  631.03  4842.8  630.89  4843.7  630.85  4845.4  630.76
  4846.9  630.72  4851.6  630.59  4853.9  630.53    4854  630.53  4857.2  630.39
  4857.3  630.39  4859.3  630.34  4861.6  630.29  4862.7  630.26  4864.1  630.21
  4866.2   630.1  4867.4  630.04  4870.5  629.79  4873.2  629.45  4875.7  629.13
    4878  628.95  4880.2  628.77  4885.2  628.47    4890  628.47  4895.9  628.76
  4899.9  628.92  4904.3  629.05  4910.6  628.65  4911.2  628.61    4917  627.91
  4920.3  627.69  4925.8  627.57  4934.3  627.23  4942.5  627.19  4943.6   627.2
  4949.8  627.24  4952.5  627.33    4962  627.32    4966  627.52  4968.9  627.51
  4973.6  627.56  4983.3  627.93  4985.7  627.89  4991.8  627.42  4992.6  627.43
    4995  624.09    4997  621.84    5000  621.84    5003  621.84    5005  624.09
    5006   627.3  5006.7  627.31    5007  627.29  5015.1   627.2  5025.5  626.92
  5030.4  626.86  5034.1  626.78  5038.3  626.86  5045.4  627.11  5047.3  627.16
  5054.3  627.31    5056  627.41  5065.1  627.91  5072.3  628.25  5073.1  628.28
  5073.8  628.32  5078.3  628.64  5081.4  628.99  5082.7  629.14  5083.3  629.21
    5084  629.29  5084.5  629.33  5084.7  629.35    5091  629.92    5092  630.01
  5094.1  630.11  5094.5  630.13  5099.1  630.29  5099.2  630.29  5100.6  630.32
    5103  630.48    5104  630.55  5107.8  630.52  5109.1  630.54  5109.6  630.58
  5110.4  630.65  5111.8  630.71  5115.8  630.89  5116.3  630.98  5119.2   631.5
  5122.1  632.01  5122.5  632.12  5124.9   632.7    5129  633.68    5130  634.04
  5130.1  634.08  5130.5  634.13    5139  635.19  5139.7  635.28  5142.3  635.49
  5145.8  635.93    5146  635.95  5148.8  636.33    5152  636.72    5153  636.92
  5154.1  637.15    5159  638.14  5159.8   638.3  5160.9  638.46  5164.6  639.02
  5165.6  639.17    5171  640.31  5172.5  640.48  5173.5  640.59  5175.5  640.67
  5179.4  640.82  5182.6  640.94    5183  640.96  5186.2  641.19  5187.9  641.31
  5190.2  641.36  5192.2  641.27  5203.3  641.94  5213.3  644.24  5221.6  645.28
    5225  645.13  5235.5  645.78  5238.6  645.99  5245.8   646.6  5251.9  647.01
  5255.4  647.25  5256.4  647.32  5258.8  647.49  5265.3  647.97  5265.5  647.98
  5273.4  648.83  5280.5  649.53  5280.8  649.57  5282.1  649.82  5286.1  650.55
BR D #Mann= 3
 4730.50    0.15    4995    0.05    5005    0.15
BR D Banks=4995.00,5005.00

Type RM Length L Ch R = 1 ,7349.8,3.9,3.9,3.9
XS GIS Cut Line= 4
      1849606.08       795568.87      1849837.00       795579.68
      1849953.99       795542.19      1850154.48       795563.10
BEGIN DESCRIPTION:
Downstream Section of Bridge/Culvert/Weir
END DESCRIPTION:
#Sta/Elev= 30
  4730.5  638.47  4749.2  637.81  4798.6  634.58  4842.8  630.89  4867.4  630.04
  4885.2  628.47  4904.3  629.05  4920.3  627.69  4934.3  627.23  4985.7  627.89
  4992.6  627.43    4995  624.09    4997  621.84    5003  621.84    5005  624.09
    5006   627.3  5034.1  626.78  5054.3  627.31  5078.3  628.64    5092  630.01
  5115.8  630.89  5130.1  634.08    5152  636.72    5171  640.31  5203.3  641.94
  5213.3  644.24  5221.6  645.28    5225  645.13  5265.5  647.98  5286.1  650.55
#Mann= 3 , 1 , 0
 4730.50    0.15       0    4995    0.05       0    5005    0.15       0
#XS Ineff= 2 , 0
       0    4980   629.2    5015       0   629.2
Bank Sta=4995.00,5005.00
Exp/Cntr=0.5,0.3

Type RM Length L Ch R = 1 ,7345.9,50,50,50
XS GIS Cut Line= 4
      1849649.50       795545.75      1849882.06       795568.95
      1850050.84       795608.20      1850061.33       795611.15
BEGIN DESCRIPTION:
Upstream Section of Bridge/Culvert/Weir
END DESCRIPTION:
#Sta/Elev= 30
  4767.6  636.87  4793.9  635.27  4801.8  634.43  4816.2  633.53  4828.2  632.37
  4846.2  631.11  4863.5  630.25    4893  628.16    4912  627.72  4929.9  626.76
  4970.6  626.44  4982.9  626.61    4990  627.03  4993.3   625.7  4995.5  623.64
  4997.5  621.84  5002.5  621.84  5004.5  623.64  5010.6   627.5  5044.6  627.91
  5082.2  629.84  5094.1  631.12  5103.5   631.6  5115.8  632.89  5124.6  634.78
    5135  637.78  5150.6  640.22  5161.9  640.51  5168.8  641.27  5185.5  641.88
#Mann= 3 , 1 , 0
 4767.60    0.15       0  4995.5    0.05       0  5004.5    0.15       0
#XS Ineff= 2 , 0
       0    4980   628.9    5020       0   628.9
Bank Sta=4995.50,5004.50
Exp/Cntr=0.5,0.3

Type RM Length L Ch R = 2 ,7320.9,,,
BEGIN DESCRIPTION:
Vernon Ln-TOR
Structure ID: NCF-0045
Approximate Survey Structure
END DESCRIPTION:
Bridge Culvert--1,0,-1,-1, 0
Deck Dist Width WeirC Skew NumUp NumDn MinLoCord MaxHiCord MaxSubmerge Is_Ogee
10,30,3,, 53, 53,,,0.95,0,1,1,,
  4767.6  4776.4  4784.4  4793.9  4801.8  4816.2  4828.2  4838.3  4846.2  4847.7
  4853.5  4856.5  4863.5  4872.6  4876.1  4887.1    4893  4900.6    4912  4916.2
  4927.3  4929.9  4965.2  4970.6  4982.9    4990  4993.3  4997.5  5002.5  5004.5
  5010.6  5019.8  5024.9  5039.1  5044.6  5055.5  5062.7  5072.4  5082.2  5088.2
  5094.1  5099.8  5103.5  5115.8  5124.6  5134.6    5135  5147.7  5150.6  5161.9
  5168.8  5182.9  5185.5
  636.87  636.44  635.82  635.27  634.43  633.53  632.37  631.81  631.11  631.31
     631  630.75  630.41  629.81  629.58   628.9   628.9   628.9   628.9   628.9
   628.9   628.9   628.9   628.9   628.9   628.9   628.9   628.9   628.9   628.9
   628.9   628.9   628.9   628.9   628.9   628.9   628.9  629.29  629.84  630.43
  631.12  631.31   631.6  632.89  634.78  637.58  637.78  639.86  640.22  640.51
  641.27  641.72  641.88
  636.87  636.44  635.82  635.27  634.43  633.53  632.37  631.81  631.11  631.03
  630.71  630.56  630.25  629.58  629.22  628.63  628.16  627.87  627.72  627.45
  626.96  626.76  626.62  626.44  626.61  627.03   625.7  621.84  621.84  623.64
   627.5  627.58  627.74   627.8  627.91  628.33   628.7  629.29  629.84  630.43
  631.12  631.31   631.6  632.89  634.78  637.58  637.78  639.86  640.22  640.51
  641.27  641.72  641.88
  4767.6  4776.4  4784.4  4793.9  4801.8  4816.2  4828.2  4838.3  4846.2  4847.7
  4853.5  4856.5  4863.5  4872.6  4876.1  4887.1    4893  4900.6    4912  4916.2
  4927.3  4929.9  4965.2  4970.6  4982.9    4990  4993.3  4997.5  5002.5  5004.5
  5010.6  5019.8  5024.9  5039.1  5044.6  5055.5  5062.7  5072.4  5082.2  5088.2
  5094.1  5099.8  5103.5  5115.8  5124.6  5134.6    5135  5147.7  5150.6  5161.9
  5168.8  5182.9  5185.5
  636.85  636.42   635.8  635.25  634.41  633.51  632.35  631.79  631.09  631.31
     631  630.75  630.41  629.81  629.58   628.9   628.9   628.9   628.9   628.9
   628.9   628.9   628.9   628.9   628.9   628.9   628.9   628.9   628.9   628.9
   628.9   628.9   628.9   628.9   628.9   628.9   628.9  629.28  629.83  630.42
  631.11   631.3  631.59  632.88  634.77  637.57  637.77  639.85  640.21  640.49
  641.25   641.7  641.86
  636.82  636.39  635.77  635.22  634.38  633.48  632.32  631.76  631.06  630.98
  630.66  630.51   630.2  629.53  629.17  628.58  628.11  627.82  627.67   627.4
  626.91  626.71  626.57  626.39  626.56  626.98  625.65  621.79  621.79  623.59
  627.45  627.53  627.69  627.75  627.86  628.28  628.65  629.24  629.79  630.38
  631.07  631.26  631.55  632.84  634.73  637.53  637.73  639.81  640.17  640.46
  641.22  641.67  641.83
BR Coef= 1 , 0 , 0 ,1.25, 0 ,,,0.8,-1,2,0,
Wspro=,,,, 1 ,,,, 0 ,,,, 0 ,,,,-1 ,-1 ,-1 , 0 , 0 , 0 , 0 , 0
Culvert=1,3.0,,30.0,0.024,0.5,1.0,2,1,621.94,4998.02,621.79,4998.02,Culvert #1  ,0,10
Culvert=1,3.0,,30.0,0.024,0.4,1.0,2,1,621.94,5002.02,621.79,5002.02,Culvert #2  ,0,10
BC Design=,, 0 ,, 0 ,,,,,,
BR U #Sta/Elev= 121
  4767.6  636.87  4776.4  636.44  4781.5  636.03  4784.4  635.82  4793.9  635.27
  4794.3  635.24  4800.1   634.6  4801.8  634.43  4808.2  634.03  4810.1  633.92
  4816.2  633.53  4819.9  633.14  4828.2  632.37  4838.3  631.81    4839  631.76
  4845.7  631.16  4846.2  631.11  4847.7  631.03  4848.8  630.97  4853.5  630.71
  4853.6   630.7  4854.6  630.65  4855.7  630.59  4856.5  630.56  4860.5  630.38
  4863.5  630.25  4864.2   630.2  4867.4  629.96  4870.1  629.73  4872.3   629.6
  4872.6  629.58    4873  629.54    4875  629.33  4876.1  629.22  4881.9  628.92
  4886.4  628.68  4887.1  628.63  4887.5   628.6    4893  628.16  4900.6  627.87
  4900.7  627.87    4906   627.8  4906.7  627.76    4912  627.72  4916.2  627.45
  4919.9  627.27  4927.3  626.96  4929.9  626.76  4932.6  626.74  4938.1  626.76
  4941.7  626.72  4950.9  626.65  4965.2  626.62  4970.1  626.45  4970.6  626.44
  4971.1  626.45  4982.9  626.61  4984.3  626.69    4990  627.03  4993.3   625.7
  4995.5  623.64  4997.5  621.84  4999.9  621.84  5002.5  621.84  5004.5  623.64
  5010.6   627.5  5012.2  627.55  5019.8  627.58    5024  627.72  5024.9  627.74
    5037   627.8  5039.1   627.8  5044.6  627.91  5049.3  628.07  5055.5  628.33
  5059.9  628.58  5062.7   628.7  5072.4  629.29  5073.4  629.35  5073.6  629.36
  5074.2  629.39  5075.9  629.49  5078.4  629.63  5081.2  629.78  5081.6   629.8
  5082.2  629.84  5082.5  629.87  5085.5  630.16  5088.2  630.43  5092.1  630.93
  5094.1  631.12  5099.8  631.31  5101.1  631.41  5103.5   631.6  5105.7  631.82
  5106.6  631.91  5110.2  632.31  5113.5  632.68  5114.8   632.8  5115.8  632.89
  5118.1  633.41  5121.5  634.13  5123.1  634.46  5124.6  634.78  5132.3  636.94
    5134  637.41  5134.6  637.58    5135  637.78  5143.3  639.14  5144.7  639.37
  5147.7  639.86  5150.6  640.22    5152  640.27  5155.7  640.35  5160.9  640.48
  5161.9  640.51  5167.7  641.13  5168.8  641.27  5182.9  641.72  5184.1  641.77
  5185.5  641.88
BR U #Mann= 3
 4767.60    0.15  4995.5    0.05  5004.5    0.15
BR U Banks=4995.50,5004.50
BR D #Sta/Elev= 121
  4767.6  636.82  4776.4  636.39  4781.5  635.98  4784.4  635.77  4793.9  635.22
  4794.3  635.19  4800.1  634.55  4801.8  634.38  4808.2  633.98  4810.1  633.87
  4816.2  633.48  4819.9  633.09  4828.2  632.32  4838.3  631.76    4839  631.71
  4845.7  631.11  4846.2  631.06  4847.7  630.98  4848.8  630.92  4853.5  630.66
  4853.6  630.65  4854.6   630.6  4855.7  630.54  4856.5  630.51  4860.5  630.33
  4863.5   630.2  4864.2  630.15  4867.4  629.91  4870.1  629.68  4872.3  629.55
  4872.6  629.53    4873  629.49    4875  629.28  4876.1  629.17  4881.9  628.87
  4886.4  628.63  4887.1  628.58  4887.5  628.55    4893  628.11  4900.6  627.82
  4900.7  627.82    4906  627.75  4906.7  627.71    4912  627.67  4916.2   627.4
  4919.9  627.22  4927.3  626.91  4929.9  626.71  4932.6  626.69  4938.1  626.71
  4941.7  626.67  4950.9   626.6  4965.2  626.57  4970.1   626.4  4970.6  626.39
  4971.1   626.4  4982.9  626.56  4984.3  626.64    4990  626.98  4993.3  625.65
  4995.5  623.59  4997.5  621.79  4999.9  621.79  5002.5  621.79  5004.5  623.59
  5010.6  627.45  5012.2   627.5  5019.8  627.53    5024  627.67  5024.9  627.69
    5037  627.75  5039.1  627.75  5044.6  627.86  5049.3  628.02  5055.5  628.28
  5059.9  628.53  5062.7  628.65  5072.4  629.24  5073.4   629.3  5073.6  629.31
  5074.2  629.34  5075.9  629.44  5078.4  629.58  5081.2  629.73  5081.6  629.75
  5082.2  629.79  5082.5  629.82  5085.5  630.11  5088.2  630.38  5092.1  630.88
  5094.1  631.07  5099.8  631.26  5101.1  631.36  5103.5  631.55  5105.7  631.77
  5106.6  631.86  5110.2  632.26  5113.5  632.63  5114.8  632.75  5115.8  632.84
  5118.1  633.36  5121.5  634.08  5123.1  634.41  5124.6  634.73  5132.3  636.89
    5134  637.36  5134.6  637.53    5135  637.73  5143.3  639.09  5144.7  639.32
  5147.7  639.81  5150.6  640.17    5152  640.22  5155.7   640.3  5160.9  640.43
  5161.9  640.46  5167.7  641.08  5168.8  641.22  5182.9  641.67  5184.1  641.72
  5185.5  641.83
BR D #Mann= 3
 4767.60    0.15  4995.5    0.05  5004.5    0.15
BR D Banks=4995.50,5004.50

Type RM Length L Ch R = 1 ,7295.9,280.8,280.8,280.8
XS GIS Cut Line= 4
      1849649.50       795595.75      1849882.06       795618.95
      1850050.84       795658.20      1850061.33       795661.15
BEGIN DESCRIPTION:
Downstream Section of Bridge/Culvert/Weir
END DESCRIPTION:
#Sta/Elev= 30
  4767.6  636.75  4793.9  635.15  4801.8  634.31  4816.2  633.41  4828.2  632.25
  4846.2  630.99  4863.5  630.13    4893  628.04    4912   627.6  4929.9  626.64
  4970.6  626.32  4982.9  626.49    4990  626.91  4993.3  625.58  4995.5  623.52
  4997.5  621.72  5002.5  621.72  5004.5  623.52  5010.6  627.38  5044.6  627.79
  5082.2  629.72  5094.1     631  5103.5  631.48  5115.8  632.77  5124.6  634.66
    5135  637.66  5150.6   640.1  5161.9  640.39  5168.8  641.15  5185.5  641.76
#Mann= 3 , 1 , 0
 4767.60    0.15       0  4995.5    0.05       0  5004.5    0.15       0
#XS Ineff= 2 , 0
       0    4980     628    5020       0     628
Bank Sta=4995.50,5004.50
Exp/Cntr=0.5,0.3