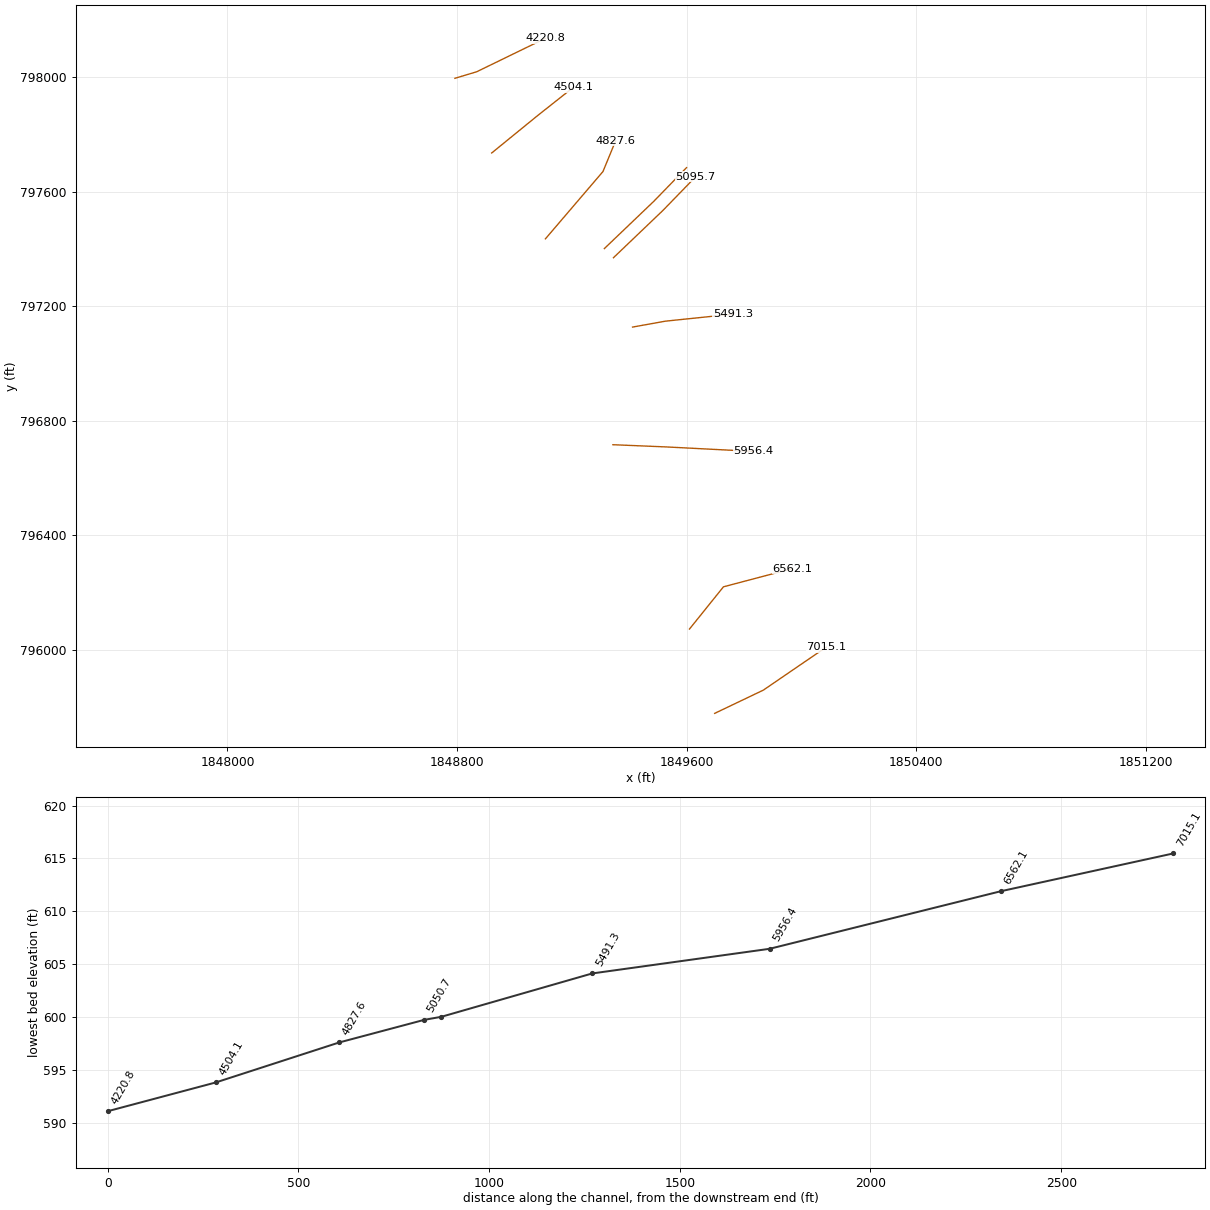
HEC-RAS study LITTLE CREEK TRIBUTARY 2.PRJ: Little Creek Tributary 2

--- LITTLE CREEK TRIBUTARY 2.g01 (geometry) --- (continued)

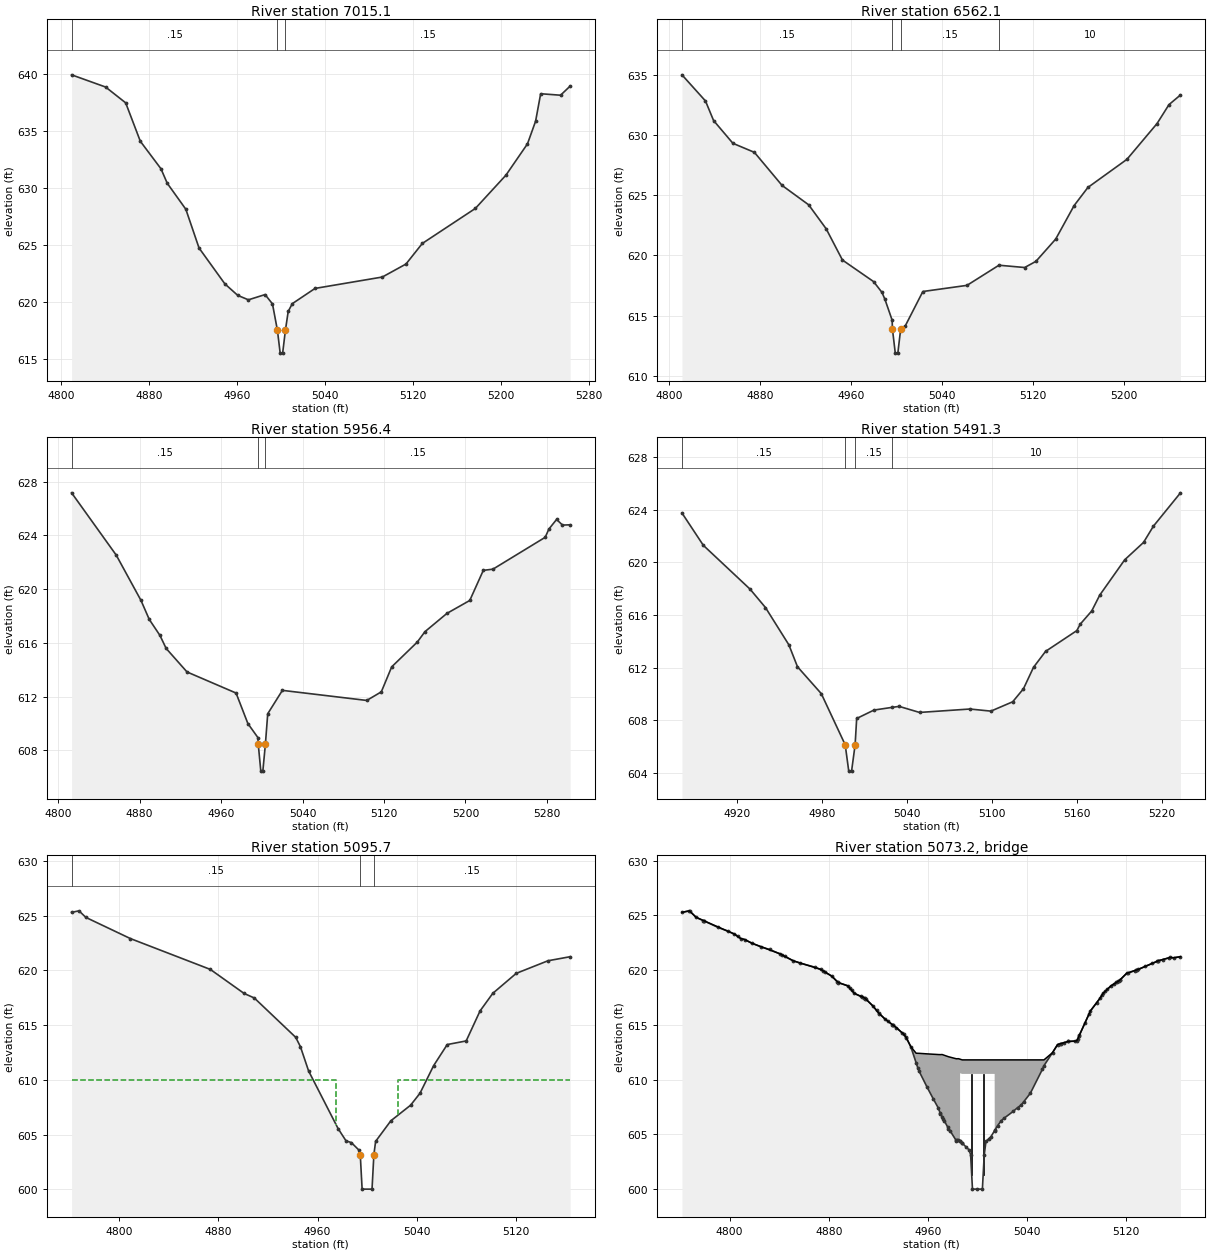
Type RM Length L Ch R = 1 ,7015.1,453,453,453
XS GIS Cut Line= 3
      1849697.78       795778.38      1849867.19       795859.44
      1850086.31       796009.47
BEGIN DESCRIPTION:
Little Creek Tributary 2 16.0
END DESCRIPTION:
#Sta/Elev= 30
  4809.3  639.91  4840.2  638.84  4858.5  637.45  4871.8  634.08  4890.6  631.66
  4896.3  630.39  4913.2  628.11  4925.2  624.71  4948.7  621.56  4960.4  620.55
  4970.1  620.16  4985.3  620.62    4992   619.8  4996.5  617.48    4999  615.48
 5001.25  615.48 5003.75  617.48  5006.3  619.14    5010  619.82  5030.7  621.16
  5091.9  622.16  5113.4   623.3  5128.3  625.11  5176.5  628.18  5204.3   631.1
  5223.9  633.85  5231.3  635.84  5235.9  638.25    5254  638.12  5262.7  638.92
#Mann= 3 , 1 , 0
 4809.30    0.15       0  4996.5    0.05       0 5003.75    0.15       0
Bank Sta=4996.50,5003.75
Exp/Cntr=0.3,0.1

Type RM Length L Ch R = 1 ,6562.1,605.7,605.7,605.7
XS GIS Cut Line= 3
      1849610.03       796072.86      1849728.43       796220.29
      1849969.36       796284.02
BEGIN DESCRIPTION:
Little Creek Tributary 2 15.0
END DESCRIPTION:
#Sta/Elev= 30
  4811.2  634.98  4831.9  632.81    4839  631.19    4856   629.3  4874.9  628.55
  4899.2  625.81  4922.6   624.2    4938  622.21  4952.3  619.62  4979.7  617.83
  4987.1  616.93  4989.7  616.35    4996  614.63 4996.25   613.9 4998.75   611.9
    5001   611.9  5003.5   613.9  5007.7  614.19    5023  617.01  5061.8  617.52
  5089.9  619.19  5112.5     619  5122.4  619.51  5139.8  621.36    5156  624.14
  5168.1  625.64  5202.4  627.97  5228.9  630.94  5239.4  632.51  5249.5  633.31
#Mann= 4 , 1 , 0
 4811.20    0.15       0 4996.25    0.05       0  5003.5    0.15       0
  5089.9      10       0
Bank Sta=4996.25,5003.50
Exp/Cntr=0.3,0.1

Type RM Length L Ch R = 1 ,5956.4,465.1,465.1,465.1
XS GIS Cut Line= 3
      1849343.21       796716.48      1849531.31       796708.63
      1849832.44       796693.10
BEGIN DESCRIPTION:
Little Creek Tributary 2 14.0
END DESCRIPTION:
#Sta/Elev= 30
  4813.1  627.17    4857  622.53  4881.3  619.16  4889.4  617.75  4899.9  616.56
    4906  615.59  4926.5  613.84  4974.7  612.27  4986.3     610  4996.2  608.95
  4996.5  608.46    4999  606.46    5001  606.46  5003.5  608.46  5005.8  610.73
  5020.2  612.47  5103.1  611.72  5117.4  612.36  5127.6  614.22  5152.7  616.06
  5160.3  616.84  5181.9   618.2  5204.3  619.16  5217.6   621.4  5227.1  621.49
  5278.4  623.86    5282  624.47  5289.6  625.19  5295.4  624.77  5302.9  624.79
#Mann= 3 , 1 , 0
 4813.10    0.15       0  4996.5    0.05       0  5003.5    0.15       0
Bank Sta=4996.50,5003.50
Exp/Cntr=0.3,0.1

Type RM Length L Ch R = 1 ,5491.3,395.6,395.6,395.6
XS GIS Cut Line= 3
      1849411.67       797127.23      1849526.32       797147.85
      1849760.64       797172.31
BEGIN DESCRIPTION:
Little Creek Tributary 2 13.0
END DESCRIPTION:
#Sta/Elev= 30
  4881.2  623.75  4896.3  621.29  4929.3  617.96  4940.2  616.56  4956.7  613.73
  4962.8  612.06  4979.6  610.02  4996.5  606.13    4999  604.13    5001  604.13
  5003.5  606.13  5004.6  608.13  5016.8  608.77  5029.9  608.98  5034.6  609.05
    5049  608.59  5084.6  608.85  5099.4  608.69  5114.8   609.4  5122.4  610.39
  5129.5  612.02    5138  613.23  5160.1  614.81  5162.5   615.3  5170.6   616.3
  5176.3  617.51  5193.9  620.19  5207.2  621.51  5214.2  622.75  5233.3  625.28
#Mann= 4 , 1 , 0
 4881.20    0.15       0  4996.5    0.05       0  5003.5    0.15       0
  5029.9      10       0
Bank Sta=4996.50,5003.50
Exp/Cntr=0.5,0.3

Type RM Length L Ch R = 1 ,5095.7,45,45,45
XS GIS Cut Line= 3
      1849345.15       797369.41      1849517.45       797534.44
      1849631.50       797652.03
BEGIN DESCRIPTION:
Upstream Section of Bridge/Culvert/Weir
END DESCRIPTION:
#Sta/Elev= 30
  4761.5   625.3  4767.5  625.44    4773  624.84  4808.9  622.91  4873.5  620.09
  4900.7   617.9    4909  617.48  4942.4  613.89  4946.2  613.04  4952.8  610.82
  4976.6  605.56    4983  604.44  4987.3  604.28  4993.2  603.62  4994.5  603.18
    4996  600.03    5004  600.03  5005.5  603.18  5006.9  604.39  5019.2  606.27
  5035.1  607.69  5042.7  608.78  5053.7   611.3  5064.7  613.23    5080  613.56
  5091.2   616.3  5101.5  617.91  5120.4  619.73    5146  620.88  5163.9  621.25
#Mann= 3 , 1 , 0
 4761.50    0.15       0  4994.5    0.05       0  5005.5    0.15       0
#XS Ineff= 2 , 0
       0    4975     610    5025       0     610
Bank Sta=4994.50,5005.50
Exp/Cntr=0.5,0.3

Type RM Length L Ch R = 3 ,5073.2,,,
BEGIN DESCRIPTION:
Mount Zion Rd-TOR
Structure ID: NCF-0044
Approximate Survey Structure
END DESCRIPTION:
Bridge Culvert--1,0,-1,-1, 0
Deck Dist Width WeirC Skew NumUp NumDn MinLoCord MaxHiCord MaxSubmerge Is_Ogee
10,25,2.6,, 56, 56,,,0.95,0,1,1,,
  4761.5  4767.5    4773  4803.4  4808.9  4812.1    4818  4840.9  4851.3  4873.5
  4882.4  4887.7  4895.4  4900.7    4909  4915.5  4920.3  4925.3  4934.6  4940.5
  4942.4  4946.2  4950.5  4952.8  4959.3  4968.2  4970.1  4971.5  4976.6    4983
  4984.6 4985.91    4986  4987.8 5013.89    5014  5019.2  5035.1  5042.7  5053.7
  5060.6  5064.7  5073.2    5080  5080.8  5091.2  5098.9  5101.5  5107.7  5114.4
  5120.4  5129.8    5146  5155.6  5158.3  5163.9
  625.27  625.41  624.81  623.31  622.88  622.79  622.45  621.47  620.85  620.06
  619.45  618.86  618.56  617.87  617.45  616.74  616.08  615.54  614.74  614.14
  613.86  613.01  612.41   612.4  612.35  612.29  612.28  612.29  612.09   611.9
  611.91  611.87  611.86   611.8   611.8   611.8   611.8   611.8   611.8   611.8
  612.46   613.2  613.48  613.53  613.67  616.27  617.42  617.88  618.55  619.03
   619.7  620.06  620.85  621.15  621.12  621.22
  625.27  625.41  624.81  623.31  622.88  622.79  622.45  621.47  620.85  620.06
  619.45  618.86  618.56  617.87  617.45  616.74  616.08  615.54  614.74  614.14
  613.86  613.01  611.54  610.79  609.32  607.45   606.9  606.61  605.53  604.41
  604.49  604.37  610.58  610.52  610.52  605.37  606.24  607.66  608.75  611.27
  612.46   613.2  613.48  613.53  613.67  616.27  617.42  617.88  618.55  619.03
   619.7  620.06  620.85  621.15  621.12  621.22
  4761.5  4767.5    4773  4803.4  4808.9  4812.1    4818  4840.9  4851.3  4873.5
  4882.4  4887.7  4895.4  4900.7    4909  4915.5  4920.3  4925.3  4934.6  4940.5
  4942.4  4946.2  4950.5  4952.8  4959.3  4968.2  4970.1  4971.5  4976.6    4983
  4984.6 4985.91    4986  4987.8 5013.89    5014  5019.2  5035.1  5042.7  5053.7
  5060.6  5064.7  5073.2    5080  5080.8  5091.2  5098.9  5101.5  5107.7  5114.4
  5120.4  5129.8    5146  5155.6  5158.3  5163.9
  625.15  625.29  624.69  623.19  622.76  622.67  622.33  621.35  620.73  619.94
  619.33  618.74  618.44  617.76  617.34  616.63  615.97  615.43  614.63  614.03
  613.75   612.9  612.41   612.4  612.35  612.29  612.28  612.29  612.09   611.9
  611.91  611.87  611.86   611.8   611.8   611.8   611.8   611.8   611.8   611.8
  612.35  613.09  613.37  613.42  613.56  616.16  617.31  617.77  618.44  618.92
  619.59  619.95  620.74  621.03     621   621.1
  625.02  625.16  624.56  623.06  622.63  622.54   622.2  621.22   620.6  619.81
   619.2  618.61  618.31  617.62   617.2  616.49  615.83  615.29  614.49  613.89
  613.61  612.76  611.29  610.54  609.07   607.2  606.65  606.36  605.28  604.16
  604.24  604.12  610.33  610.27  610.27  605.12  605.99  607.41   608.5  611.02
  612.21  612.95  613.23  613.28  613.42  616.02  617.17  617.63   618.3  618.78
  619.45  619.81   620.6   620.9  620.87  620.97
Pier Skew, UpSta & Num, DnSta & Num=,4995.4, 2 ,4995.4, 2 , 0 , 0 , 0 ,,
       1       1
  599.21  611.52
       1       1
  598.96  611.27
Pier Skew, UpSta & Num, DnSta & Num=,5004.6, 2 ,5004.6, 2 , 0 , 0 , 0 ,,
       1       1
  599.21  611.52
       1       1
  598.96  611.27
Abutment Skew #Up #Dn=, 2 , 2
 4985.80 4990.80
  610.58  603.86
 4985.80 4990.80
  610.33  603.61
Abutment Skew #Up #Dn=, 2 , 2
 5009.30 5014.09
  604.61  610.52
 5009.30 5014.09
  604.36  610.27
BR Coef= 1 , 1 , 0 ,1.25, 0 ,,,0.8,0,2,0,
Wspro=,,,, 1 ,,,, 0 ,,,, 0 ,,,,-1 ,-1 ,-1 , 0 , 0 , 0 , 0 , 0
BC Design=,, 0 ,, 0 ,,,,,,
BR U #Sta/Elev= 144
  4761.5  625.27  4767.5  625.41  4767.7   625.4    4773  624.81  4778.8  624.52
  4779.1   624.5  4779.4  624.49  4790.7  623.89  4798.7  623.55  4803.4  623.31
  4806.8  623.09  4808.9  622.88  4812.1  622.79    4818  622.45  4825.1  622.13
  4832.2  621.88  4840.9  621.47    4842  621.37  4844.5  621.25  4851.3  620.85
    4857  620.63  4868.7  620.27  4873.5  620.06  4875.6  619.92  4877.2  619.79
  4882.4  619.45  4886.8  618.94  4887.3   618.9  4887.7  618.86  4895.4  618.56
    4897  618.35  4898.4  618.16  4900.7  617.87  4905.7   617.6  4906.6  617.55
  4908.6  617.47    4909  617.45  4909.6  617.39  4909.8  617.37  4915.5  616.74
  4918.6  616.31  4920.3  616.08  4920.9  616.02  4925.3  615.54  4927.7  615.33
  4931.2  615.03  4931.7  614.96  4931.8  614.95  4934.6  614.74  4938.9   614.3
  4940.5  614.14  4942.4  613.86  4942.5  613.84  4946.2  613.01  4950.5  611.54
  4951.9  611.06  4952.8  610.79  4959.3  609.32  4964.4  608.23  4968.2  607.45
  4969.9  606.96  4970.1   606.9  4971.5  606.61  4972.3  606.44  4973.2  606.25
  4976.1  605.64  4976.6  605.53  4978.1  605.29  4982.7  604.46    4983  604.41
  4983.8  604.45  4984.6  604.49 4985.91  604.37    4986  604.37  4987.3  604.25
  4987.8  604.19  4990.8  603.86  4993.2  603.59  4994.5  603.15    4996     600
  4999.9     600    5004     600  5005.5  603.15  5006.9  604.36  5009.3  604.61
  5010.8  604.77 5013.89  605.35    5014  605.37  5016.2  605.78  5019.2  606.24
  5021.7  606.49  5028.9   607.1  5032.4  607.44  5035.1  607.66  5037.2  607.95
  5042.7  608.75  5052.4  610.93  5053.7  611.27  5060.6  612.46  5064.7   613.2
  5066.8  613.27  5067.3  613.28  5069.9  613.37  5073.2  613.48  5073.3  613.48
  5078.7  613.51    5080  613.53  5080.8  613.67    5082  613.99  5082.3  614.07
  5086.9  615.21  5089.9  615.95  5091.2  616.27  5096.3  617.03  5098.9  617.42
  5100.5  617.74  5101.5  617.88  5103.2  618.06  5104.7  618.23  5107.7  618.55
  5110.3  618.74  5112.1  618.87  5112.6   618.9  5113.4  618.96  5114.4  619.03
  5114.8  619.07  5115.3  619.12  5120.4   619.7  5121.5  619.74  5126.8  619.95
  5127.6  619.98  5128.1  619.99  5128.7  620.02  5129.8  620.06  5135.6  620.34
  5141.2  620.61  5144.9  620.79  5145.5  620.83    5146  620.85  5149.6  620.96
  5154.8  621.12  5155.6  621.15  5158.3  621.12  5163.9  621.22
BR U #Mann= 3
 4761.50    0.15  4994.5    0.05  5005.5    0.15
BR U Banks=4994.50,5005.50
BR D #Sta/Elev= 144
  4761.5  625.02  4767.5  625.16  4767.7  625.15    4773  624.56  4778.8  624.27
  4779.1  624.25  4779.4  624.24  4790.7  623.64  4798.7   623.3  4803.4  623.06
  4806.8  622.84  4808.9  622.63  4812.1  622.54    4818   622.2  4825.1  621.88
  4832.2  621.63  4840.9  621.22    4842  621.12  4844.5     621  4851.3   620.6
    4857  620.38  4868.7  620.02  4873.5  619.81  4875.6  619.67  4877.2  619.54
  4882.4   619.2  4886.8  618.69  4887.3  618.65  4887.7  618.61  4895.4  618.31
    4897   618.1  4898.4  617.91  4900.7  617.62  4905.7  617.35  4906.6   617.3
  4908.6  617.22    4909   617.2  4909.6  617.14  4909.8  617.12  4915.5  616.49
  4918.6  616.06  4920.3  615.83  4920.9  615.77  4925.3  615.29  4927.7  615.08
  4931.2  614.78  4931.7  614.71  4931.8   614.7  4934.6  614.49  4938.9  614.05
  4940.5  613.89  4942.4  613.61  4942.5  613.59  4946.2  612.76  4950.5  611.29
  4951.9  610.81  4952.8  610.54  4959.3  609.07  4964.4  607.98  4968.2   607.2
  4969.9  606.71  4970.1  606.65  4971.5  606.36  4972.3  606.19  4973.2     606
  4976.1  605.39  4976.6  605.28  4978.1  605.04  4982.7  604.21    4983  604.16
  4983.8   604.2  4984.6  604.24 4985.91  604.12    4986  604.12  4987.3     604
  4987.8  603.94  4990.8  603.61  4993.2  603.34  4994.5   602.9    4996  599.75
  4999.9  599.75    5004  599.75  5005.5   602.9  5006.9  604.11  5009.3  604.36
  5010.8  604.52 5013.89   605.1    5014  605.12  5016.2  605.53  5019.2  605.99
  5021.7  606.24  5028.9  606.85  5032.4  607.19  5035.1  607.41  5037.2   607.7
  5042.7   608.5  5052.4  610.68  5053.7  611.02  5060.6  612.21  5064.7  612.95
  5066.8  613.02  5067.3  613.03  5069.9  613.12  5073.2  613.23  5073.3  613.23
  5078.7  613.26    5080  613.28  5080.8  613.42    5082  613.74  5082.3  613.82
  5086.9  614.96  5089.9   615.7  5091.2  616.02  5096.3  616.78  5098.9  617.17
  5100.5  617.49  5101.5  617.63  5103.2  617.81  5104.7  617.98  5107.7   618.3
  5110.3  618.49  5112.1  618.62  5112.6  618.65  5113.4  618.71  5114.4  618.78
  5114.8  618.82  5115.3  618.87  5120.4  619.45  5121.5  619.49  5126.8   619.7
  5127.6  619.73  5128.1  619.74  5128.7  619.77  5129.8  619.81  5135.6  620.09
  5141.2  620.36  5144.9  620.54  5145.5  620.58    5146   620.6  5149.6  620.71
  5154.8  620.87  5155.6   620.9  5158.3  620.87  5163.9  620.97
BR D #Mann= 3
 4761.50    0.15  4994.5    0.05  5005.5    0.15
BR D Banks=4994.50,5005.50

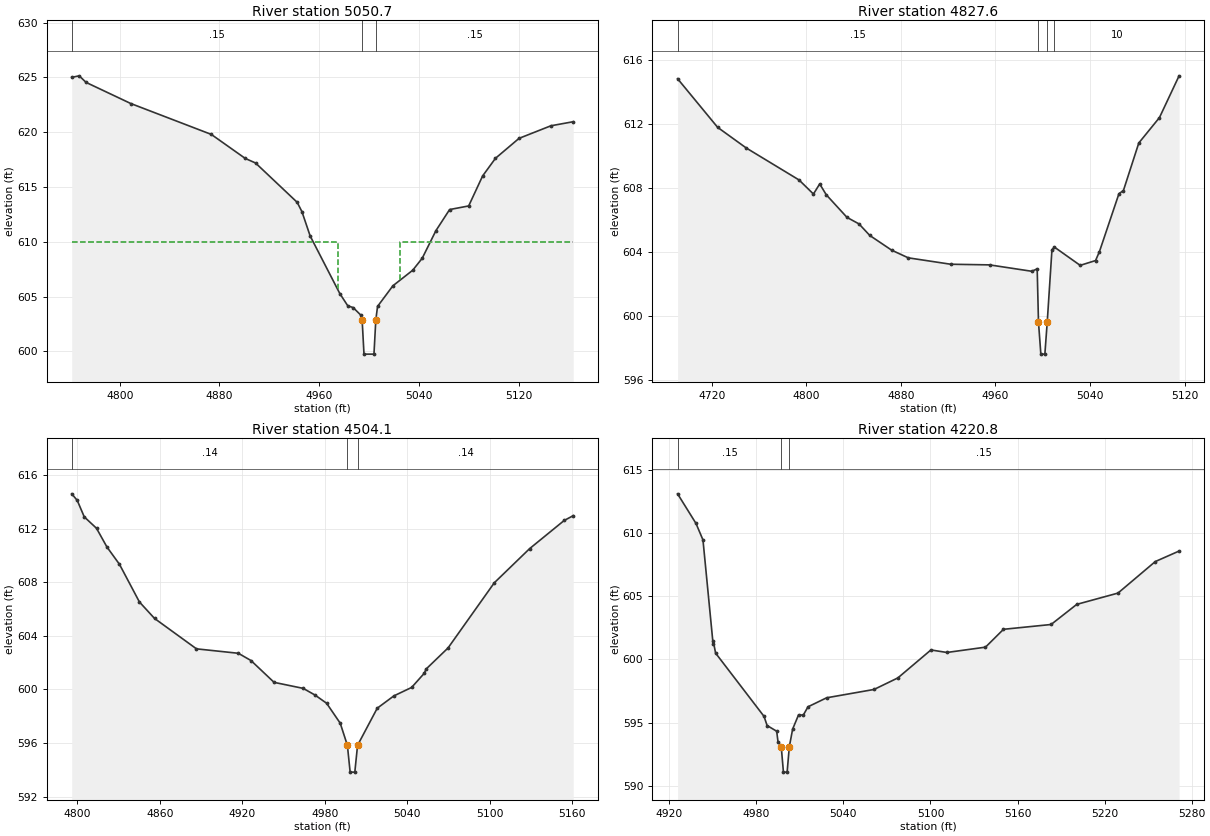
Type RM Length L Ch R = 1 ,5050.7,223.1,223.1,223.1
XS GIS Cut Line= 3
      1849313.38       797401.27      1849485.67       797566.30
      1849599.73       797683.90
BEGIN DESCRIPTION:
Downstream Section of Bridge/Culvert/Weir
END DESCRIPTION:
#Sta/Elev= 30
  4761.5  625.01  4767.5  625.15    4773  624.55  4808.9  622.62  4873.5   619.8
  4900.7  617.61    4909  617.19  4942.4   613.6  4946.2  612.75  4952.8  610.53
  4976.6  605.27    4983  604.15  4987.3  603.99  4993.2  603.33  4994.5  602.89
    4996  599.74    5004  599.74  5005.5  602.89  5006.9   604.1  5019.2  605.98
  5035.1   607.4  5042.7  608.49  5053.7  611.01  5064.7  612.94    5080  613.27
  5091.2  616.01  5101.5  617.62  5120.4  619.44    5146  620.59  5163.9  620.96
#Mann= 3 , 1 , 0
 4761.50    0.15       0  4994.5    0.05       0  5005.5    0.15       0
#XS Ineff= 2 , 0
       0    4975     610    5025       0     610
Bank Sta=4994.50,5005.50
Exp/Cntr=0.5,0.3

Type RM Length L Ch R = 1 ,4827.6,323.5,323.5,323.5
XS GIS Cut Line= 3
      1849108.05       797435.31      1849308.50       797670.17
      1849352.60       797777.19
BEGIN DESCRIPTION:
Little Creek Tributary 2 10.0
END DESCRIPTION:
#Sta/Elev= 30
  4690.9  614.82  4724.8  611.78    4749  610.49  4793.7  608.49  4805.9  607.61
  4811.2  608.24  4816.8  607.56  4834.3  606.15  4844.5  605.74  4853.6  605.02
  4872.1   604.1  4886.2  603.62  4922.1  603.22    4955  603.18  4990.7  602.78
  4995.3  602.93  4996.4   599.6  4998.4   597.6  5001.8   597.6  5003.8   599.6
  5007.8  604.13  5009.9  604.29  5031.7  603.15  5044.7  603.45    5048  604.01
  5064.5  607.63  5068.3  607.83  5081.3   610.8  5098.8  612.39  5115.4     615
#Mann= 4 , 1 , 0
 4690.90    0.15       0  4996.4    0.05       0  5003.8    0.15       0
  5009.9      10       0
Bank Sta=4996.40,5003.80
Exp/Cntr=0.3,0.1

Type RM Length L Ch R = 1 ,4504.1,283.3,283.3,283.3
XS GIS Cut Line= 3
      1848920.77       797735.01      1849079.63       797864.64
      1849204.62       797963.76
BEGIN DESCRIPTION:
Little Creek Tributary 2 9.0
END DESCRIPTION:
#Sta/Elev= 30
    4796  614.59    4800   614.1  4805.1  612.87    4814  612.02  4821.6  610.62
  4830.7  609.33  4845.2  606.52  4856.2  605.29  4886.7  603.02  4917.1  602.69
  4926.3  602.15  4943.1  600.52  4964.3  600.07  4972.9  599.57  4981.3  598.96
  4991.2  597.47  4996.4  595.82  4998.4  593.82  5001.8  593.82  5003.8  595.82
  5018.1  598.59  5030.2  599.51  5043.1  600.14  5052.4  601.21  5053.5   601.5
  5069.6  603.09  5103.2  607.95  5128.9   610.5    5154   612.6  5160.6  612.96
#Mann= 3 , 1 , 0
 4796.00    0.14       0  4996.4   0.045       0  5003.8    0.14       0
Bank Sta=4996.40,5003.80
Exp/Cntr=0.3,0.1

Type RM Length L Ch R = 1 ,4220.8,672.6,672.6,672.6
XS GIS Cut Line= 3
      1848792.70       797995.89      1848868.70       798018.72
      1849108.05       798135.40
BEGIN DESCRIPTION:
Little Creek Tributary 2 8.0
END DESCRIPTION:
#Sta/Elev= 30
  4925.7  613.08  4938.4  610.74  4943.2  609.44  4950.2  601.19  4950.3  601.45
  4951.9   600.5  4985.3   595.5  4987.4  594.78    4994  594.33  4994.9  593.51
 4997.15   593.1 4998.65   591.1  5001.2   591.1  5002.7   593.1    5005   594.5
  5009.1  595.63  5012.3   595.6  5015.6  596.26  5028.4  596.97  5061.1  597.63
  5077.5  598.54  5100.3  600.75  5111.3  600.55  5137.9  600.97  5150.3  602.38
  5183.1  602.76  5200.8  604.35  5229.2  605.24  5254.9  607.73  5271.3  608.56
#Mann= 3 , 1 , 0
 4925.70    0.15       0 4997.15    0.05       0  5002.7    0.15       0
Bank Sta=4997.15,5002.70
Exp/Cntr=0.3,0.1