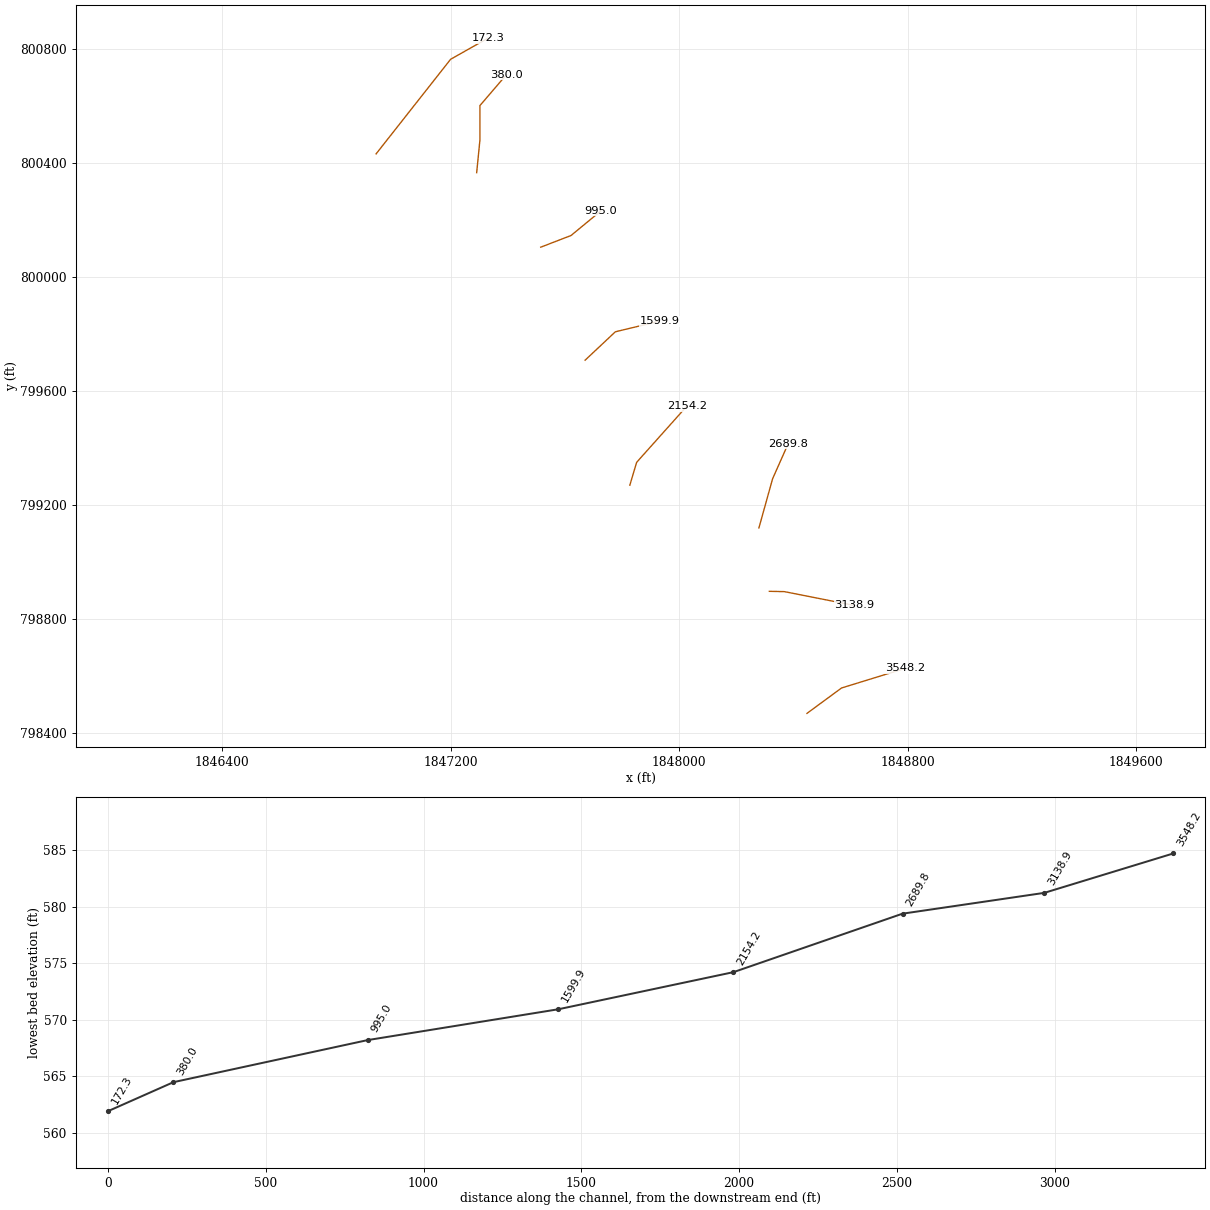
HEC-RAS study LITTLE CREEK TRIBUTARY 2.PRJ: Little Creek Tributary 2

--- LITTLE CREEK TRIBUTARY 2.g01 (geometry) --- (continued)

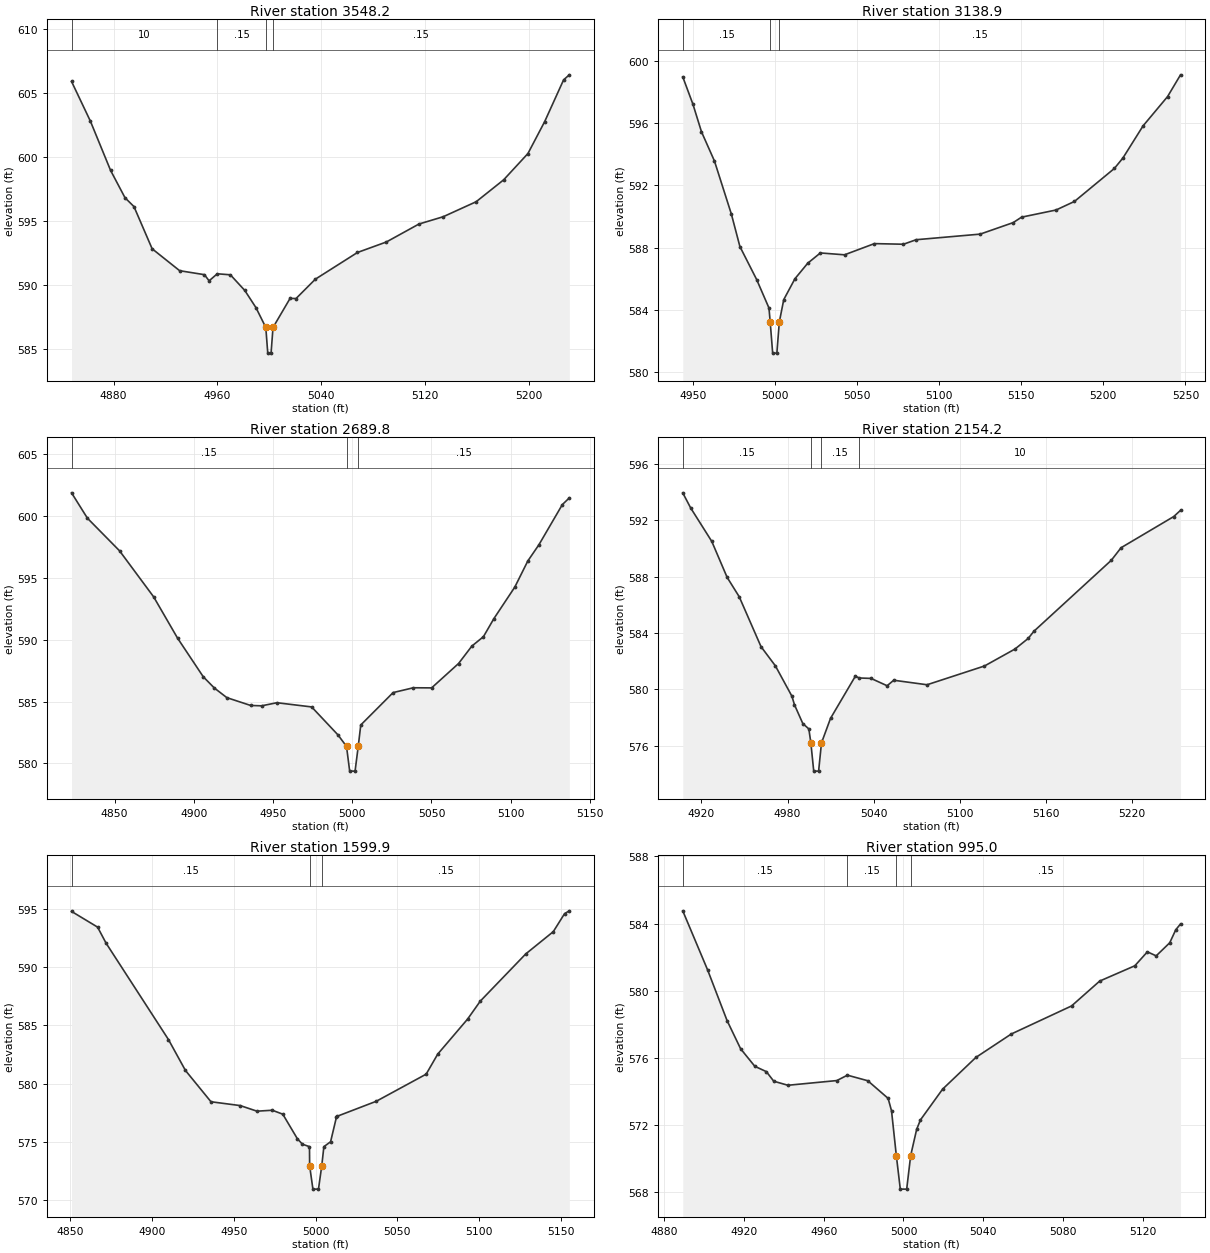
Type RM Length L Ch R = 1 ,3548.2,409.3,409.3,409.3
XS GIS Cut Line= 3
      1848446.95       798468.14      1848568.02       798557.25
      1848790.91       798626.06
BEGIN DESCRIPTION:
Little Creek Tributary 2 7.0
END DESCRIPTION:
#Sta/Elev= 30
  4847.6   605.9  4862.1  602.81  4877.7  598.96  4888.8  596.83  4895.7  596.14
  4909.7  592.85  4930.9  591.14    4950  590.83  4953.6  590.35  4959.9   590.9
    4970  590.82  4981.1   589.6  4989.7  588.26  4997.3  586.71  4998.8  584.71
 5001.35  584.71 5002.85  586.71    5016  588.98  5020.6  588.97  5035.5  590.48
  5067.9  592.56  5090.2  593.38  5115.3  594.78    5134  595.35  5159.4  596.52
  5180.6  598.23  5199.3  600.28  5212.2  602.77  5226.8  606.03  5231.2  606.42
#Mann= 4 , 1 , 0
 4847.60      10       0  4959.9    0.15       0  4997.3    0.05       0
 5002.85    0.15       0
Bank Sta=4997.30,5002.85
Exp/Cntr=0.3,0.1

Type RM Length L Ch R = 1 ,3138.9,449.1,449.1,449.1
XS GIS Cut Line= 3
      1848315.23       798896.25      1848367.71       798895.22
      1848613.55       798846.59
BEGIN DESCRIPTION:
Little Creek Tributary 2 6.0
END DESCRIPTION:
#Sta/Elev= 30
  4943.9  598.98  4950.1  597.22  4955.3  595.45  4963.2  593.57  4973.5  590.16
  4978.7  588.07  4988.9  585.95  4996.4  584.12 4997.15  583.22 4998.65  581.22
  5001.2  581.22  5002.7  583.22  5005.4  584.66  5012.2     586    5020     587
  5027.7  587.66  5042.4  587.54  5060.6  588.26  5078.3  588.22    5086  588.51
    5125  588.87  5145.1  589.61  5150.2  589.96  5171.2  590.42  5182.4  590.97
  5206.7  593.09  5211.9  593.76  5224.2  595.83  5239.1  597.71    5247  599.11
#Mann= 3 , 1 , 0
 4943.90    0.15       0 4997.15    0.05       0  5002.7    0.15       0
Bank Sta=4997.15,5002.70
Exp/Cntr=0.3,0.1

Type RM Length L Ch R = 1 ,2689.8,535.6,535.6,535.6
XS GIS Cut Line= 3
      1848278.74       799118.78      1848326.70       799291.44
      1848381.45       799414.75
BEGIN DESCRIPTION:
Little Creek Tributary 2 5.0
END DESCRIPTION:
#Sta/Elev= 30
  4822.9  601.88  4832.9  599.83  4853.2  597.19  4874.7  593.47  4889.8  590.13
    4906  587.01    4913   586.1  4920.9  585.32  4935.9  584.69  4942.8  584.66
  4952.5  584.91  4974.4  584.57    4991  582.31  4996.4  581.38  4998.4  579.38
  5001.8  579.38  5003.8  581.38  5005.4  583.11  5025.8  585.73  5038.6  586.12
  5050.1  586.11  5067.1  588.08  5075.5  589.49  5082.8  590.25  5089.4  591.71
  5102.6  594.26  5110.8  596.37  5117.8  597.68  5132.6  600.93    5137  601.47
#Mann= 3 , 1 , 0
 4822.90    0.15       0  4996.4    0.05       0  5003.8    0.15       0
Bank Sta=4996.40,5003.80
Exp/Cntr=0.3,0.1

Type RM Length L Ch R = 1 ,2154.2,554.3,554.3,554.3
XS GIS Cut Line= 3
      1847826.91       799268.59      1847850.73       799348.79
      1848025.80       799544.99
BEGIN DESCRIPTION:
Little Creek Tributary 2 4.0
END DESCRIPTION:
#Sta/Elev= 30
    4907  593.93  4912.5  592.86  4927.2  590.49  4937.9  587.94  4946.3  586.57
  4961.5  583.03  4971.5  581.67    4983  579.52  4984.8  578.91  4990.6  577.58
  4994.8   577.2  4996.2  576.21  4998.2  574.21  5001.6  574.21  5003.6  576.21
  5009.9  577.95  5027.2  580.94  5029.9  580.81  5038.1  580.78  5049.3  580.26
  5053.9  580.65  5077.1  580.33  5117.1  581.66  5138.3  582.86  5147.5  583.61
  5151.5  584.12  5205.4  589.15  5212.2  590.04  5248.9  592.25  5253.6  592.69
#Mann= 4 , 1 , 0
 4907.00    0.15       0  4996.2    0.05       0  5003.6    0.15       0
  5029.9      10       0
Bank Sta=4996.20,5003.60
Exp/Cntr=0.3,0.1

Type RM Length L Ch R = 1 ,1599.9,604.9,604.9,604.9
XS GIS Cut Line= 3
      1847670.31       799706.95      1847776.16       799806.65
      1847930.47       799843.80
BEGIN DESCRIPTION:
Little Creek Tributary 2 3.0
END DESCRIPTION:
#Sta/Elev= 30
  4850.9   594.8  4866.8  593.45    4872  592.07  4910.1  583.79  4920.5  581.13
  4936.1  578.44    4954  578.11  4964.2  577.63  4973.6  577.71    4980  577.37
  4988.9  575.26    4992  574.79  4996.3  574.58  4996.4  572.93  4998.4  570.93
  5001.8  570.93  5003.8  572.93  5005.1  574.58  5009.2     575  5012.8  577.13
  5013.2  577.19  5037.1  578.48  5067.6  580.81  5074.7  582.54  5092.9  585.54
  5100.7  587.09  5128.5  591.15  5145.3  593.06  5152.2  594.61  5155.1  594.85
#Mann= 3 , 1 , 0
 4850.90    0.15       0  4996.4    0.05       0  5003.8    0.15       0
Bank Sta=4996.40,5003.80
Exp/Cntr=0.3,0.1

Type RM Length L Ch R = 1 ,995.0,615,615,615
XS GIS Cut Line= 3
      1847514.88       800103.37      1847620.97       800144.34
      1847725.58       800230.66
BEGIN DESCRIPTION:
Little Creek Tributary 2 2.0
END DESCRIPTION:
#Sta/Elev= 30
  4889.4  584.76  4901.9  581.23  4911.6  578.23  4918.4  576.55  4925.5  575.51
  4931.3  575.19    4935  574.62  4942.1  574.38  4966.6  574.66  4971.9  574.98
  4982.1  574.65  4992.3   573.6    4994  572.86  4996.4   570.2  4998.4   568.2
  5001.6   568.2  5003.6   570.2  5006.6  571.76  5008.5  572.32  5019.6  574.15
  5036.3  576.04    5054  577.43  5084.2   579.1  5098.3  580.58  5115.9  581.49
  5122.2  582.32  5126.6  582.08  5133.4  582.86  5136.4  583.63  5138.8  583.98
#Mann= 4 , 1 , 0
 4889.40    0.15       0  4971.9    0.15       0  4996.4    0.05       0
  5003.6    0.15       0
Bank Sta=4996.40,5003.60
Exp/Cntr=0.3,0.1

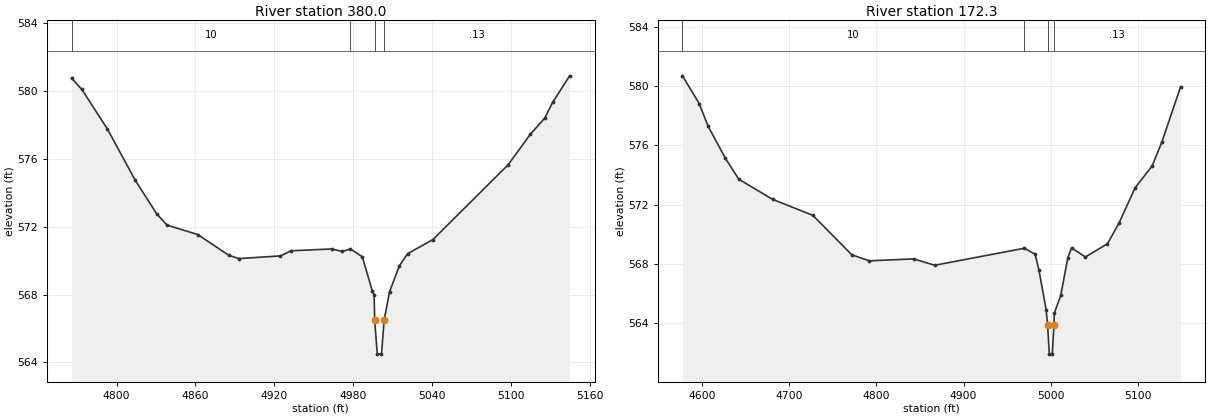
Type RM Length L Ch R = 1 ,380.0,207.7,207.7,207.7
XS GIS Cut Line= 4
      1847290.76       800364.72      1847302.13       800478.99
      1847302.13       800600.20      1847395.23       800708.82
BEGIN DESCRIPTION:
Little Creek Tributary 2 1.0
END DESCRIPTION:
#Sta/Elev= 30
  4765.7  580.77  4773.5  580.11  4792.9  577.78  4814.2  574.74  4830.6  572.75
  4838.3   572.1  4861.7  571.54  4885.5  570.31    4893  570.12  4924.7  570.28
  4932.7  570.58  4963.8  570.69  4971.8  570.54  4977.9  570.69    4987  570.23
  4994.7  568.18    4996     568  4996.4  566.48  4998.4  564.48  5001.6  564.48
  5003.6  566.48  5007.7  568.15  5015.1  569.68  5021.5  570.41  5040.7  571.24
  5098.1  575.67  5114.8  577.45  5125.9  578.42  5131.9  579.35  5144.8  580.91
#Mann= 4 , 1 , 0
 4765.70      10       0  4977.9    0.13       0  4996.4   0.045       0
  5003.6    0.13       0
Bank Sta=4996.40,5003.60
Exp/Cntr=0.3,0.1

Type RM Length L Ch R = 1 ,172.3,0,0,0
XS GIS Cut Line= 3
      1846938.69       800430.69      1847199.53       800762.52
      1847329.41       800836.00
BEGIN DESCRIPTION:
Little Creek Tributary 2 0.5
END DESCRIPTION:
#Sta/Elev= 30
  4577.6   580.7  4596.8  578.83    4607   577.3  4626.7  575.15  4642.2  573.72
    4681  572.36  4727.2  571.28    4772  568.61    4792  568.21    4843  568.34
  4866.9  567.91  4969.9  569.06  4982.2  568.65  4986.5  567.59  4994.8   564.9
  4996.4  563.91  4998.4  561.91  5001.8  561.91  5003.8  563.91  5004.1  564.67
  5011.5  565.87  5019.7  568.43  5023.9  569.08  5039.8  568.47  5065.1  569.36
  5078.3  570.75  5096.8  573.14  5116.3  574.61  5127.5  576.23  5148.9  579.94
#Mann= 4 , 1 , 0
 4577.60      10       0  4969.9    0.13       0  4996.4   0.045       0
  5003.8    0.13       0
Bank Sta=4996.40,5003.80
Exp/Cntr=0.3,0.1

Chan Stop Cuts=-1