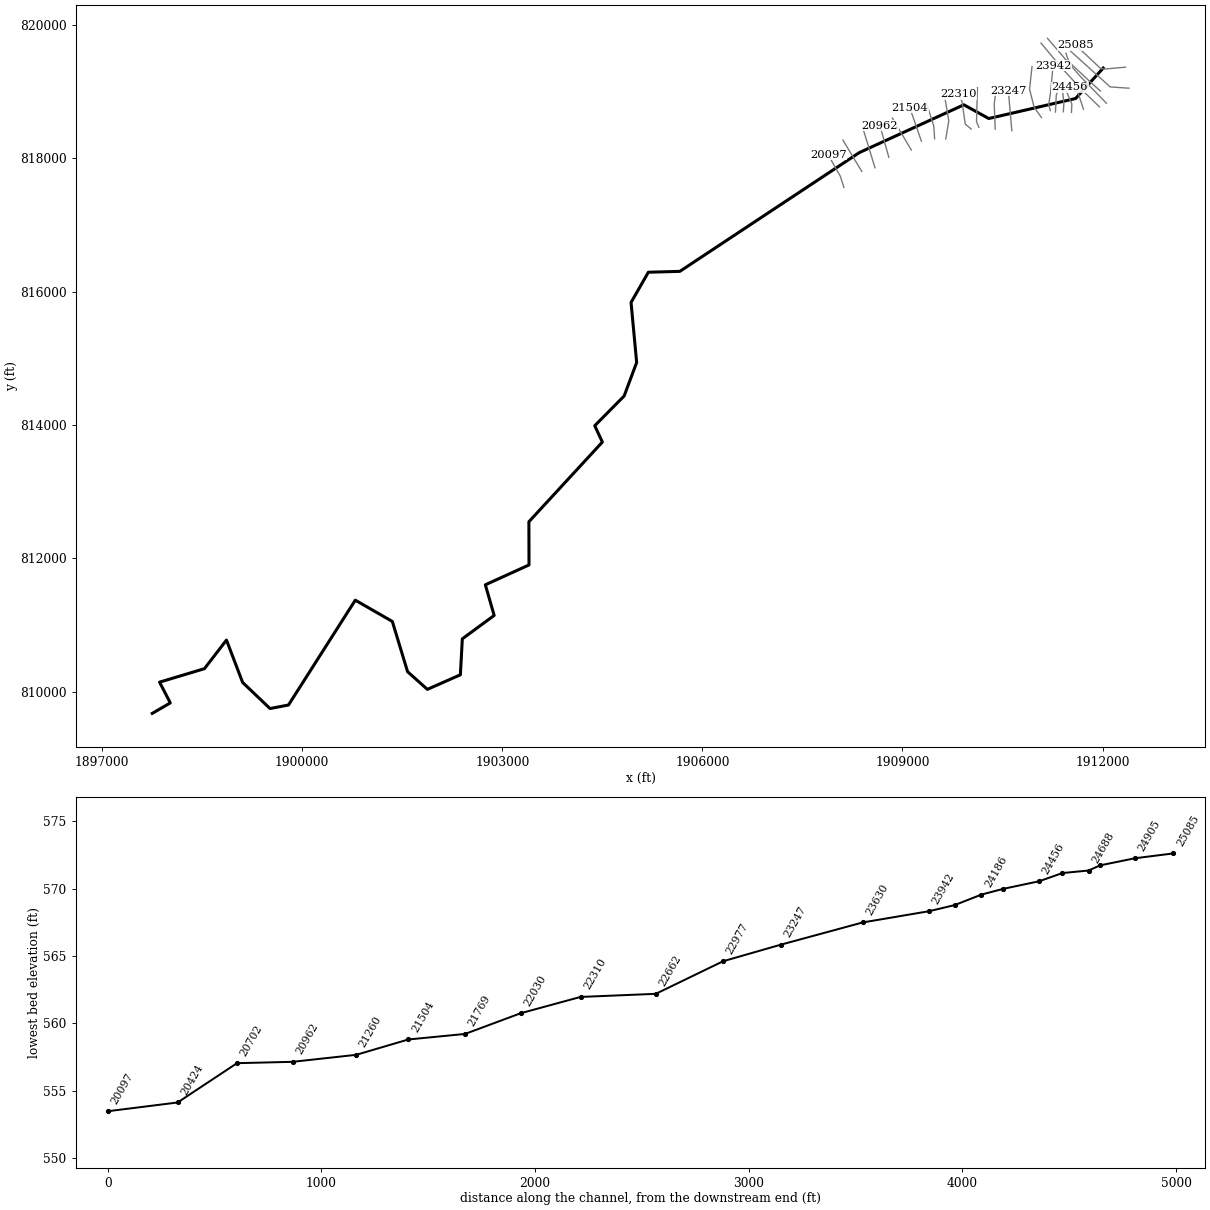
--- MeadowCreek.prj (project) ---

Proj Title=MeadowCreek Detailed Study
Current Plan=p01
Default Exp/Contr=0.3,0.1
English Units
Geom File=g01
Flow File=f01
Flow File=f02
Flow File=f03
Plan File=p01
Plan File=p02
Plan File=p03
Y Axis Title=Elevation
X Axis Title(PF)=Main Channel Distance
X Axis Title(XS)=Station
BEGIN DESCRIPTION:
North Carolina Floodplain Mapping Program
Alamance County, NC Flood Insurance Study
Stream Name: Meadow Creek
Study Type:  Detailed Study
Study Contractor:  ESP Associates, P.A.
Contract Number: 286-0000-23 ESP
Delivery Order:  14
Vertical Datum:  NAVD88
Hydraulic analyses were performed using HEC-RAS, version 4.1, applying steady state hydraulic modeling techniques to develop flood profiles for the 10%, 4%, 2%, 1%, 0.2% annual chance events, and three (3) defined future conditions profiles (1% annual chance discharge assuming an urban area with 10%, 20%, and 35% impervious levels).
This HEC-RAS model contains three (3) plans with individual steady flow files and one universal geometry file ("NCFMP LiDAR, Survey Structures & Channel") to model the eight (8) profiles.
Multi Profiles Existing Condition Plan:  This HEC-RAS plan is used to analyze the five (5) regulatory and non-regulatory flood events.  The five profiles include the 10%, 4%, 2%, 1%, and 0.2% annual chance events.
Defined Future Condition Profiles Plan:  This HEC-RAS plan is used to analyze three (3) defined future conditions discharges ("1%@10% Imp," "1%@20% Imp," and "1%@35% Imp").  The discharges were developed using USGS Urban Regression equations calculating the 1% annual chance discharge assuming 10%, 20%, and 35% impervious levels.
Floodway Run Plan:  This HEC-RAS plan is used to analyze the 1% regulatory floodway profile.  The plan lists two profiles, the "1%" and "1%FW."
END DESCRIPTION:
DSS Export Rating Curves= 0
DSS Export Rating Curve Sorted= 0
DSS Export Volume Flow Curves= 0
DXF OffsetX= 0
DXF OffsetY= 0
DXF ScaleX= 1
DXF ScaleY= 10

--- MeadowCreek.p01 (plan) ---

Plan Title=Multi Profiles Existing Condition
Program Version=4.10
Short Identifier=Multi
Geom File=g01
Flow File=f01
Subcritical Flow
K Sum by GR= 0
Std Step Tol= 0.01
Critical Tol= 0.01
Num of Std Step Trials= 20
Max Error Tol= 0.3
Flow Tol Ratio= 0.001
Split Flow NTrial= 30
Split Flow Tol= 0.02
Split Flow Ratio= 0.02
Log Output Level= 0
Friction Slope Method= 1
Unsteady Friction Slope Method= 2
Unsteady Bridges Friction Slope Method= 1
Parabolic Critical Depth
Global Vel Dist= 0 , 0 , 0
Global Log Level= 0
CheckData=True
Encroach Param=-1 ,0,0, 0
BEGIN DESCRIPTION:
Multiple Run
END DESCRIPTION:
Computation Interval=1HOUR
Output Interval=1HOUR
Run HTab= 0
Run UNet= 0
Run PostProcess= 0
Run WQNet= 0
UNET Theta= 1
UNET Theta Warmup= 1
UNET ZTol= 0.02
UNET ZSATol= 0.05
UNET MxIter= 20
UNET MaxInSteps= 0
UNET DtIC= 0
UNET DtMin= 0
UNET MaxCRTS= 20
UNET WFStab= 2
UNET SFStab= 1
UNET WFX= 1
UNET SFX= 1
UNET DSS MLevel= 4
UNET DZMax Abort= 100
UNET Convert EG Bridges= 0
UNET Use Existing IB Tables=-1
UNET Froude Reduction=False
UNET Froude Limit= 1
UNET Froude Power= 10
UNET Time Slicing=0,0, 5
UNET Junction Losses=0
Instantaneous Interval=1HOUR
Write IC File= 0
Write IC File at Sim End=0
Echo Input=False
Echo Parameters=False
Echo Output=False
Write Detailed= 0
WQ AD Non Conservative
WQ ULTIMATE=-1
WQ Max Comp Step=1HOUR
WQ Output Interval=15MIN
WQ Output Selected Increments= 0
WQ Output face flow=0
WQ Output face velocity=0
WQ Output face area=0
WQ Output face dispersion=0
WQ Output cell volume=0
WQ Output cell surface area=0
WQ Output cell continuity=0
WQ Output cumulative cell continuity=0
WQ Output face conc=0
WQ Output face dconc_dx=0
WQ Output face courant=0
WQ Output face peclet=0
WQ Output face adv mass=0
WQ Output face disp mass=0
WQ Output cell mass=0
WQ Output cell source sink temp=0
WQ Output cell source sink nsm=0
WQ Output MaxMinRange=-1
WQ Daily Max Min Mean=-1
WQ Daily Range=0
WQ Daily Time=0
WQ Create Restart=0
WQ Fixed Restart=0
WQ System Summary=0
WQ Use Fixed Temperature=0
Sorting and Armoring Iterations= 10
XS Update Threshold= 0.02
Hydraulics Update Threshold= 0.02
Energy Slope Method= 1
Volume Change Method= 0
XS Weighting Method= 0
Number of US Weighted Cross Sections= 1
Number of DS Weighted Cross Sections= 1
Upstream XS Weight=0.25
Main XS Weight=0.5
Downstream XS Weight=0.25
Number of DS XS's Weighted with US Boundary= 1
Upstream Boundary Weight= 1
Weight of XSs Associated with US Boundary= 0
Number of US XS's Weighted with DS Boundary= 1
Downstream Boundary Weight= 0.5
Weight of XSs Associated with DS Boundary= 0.5
Sediment Output Level= 4
Mass or Volume Output= 0
Output Increment Type= 1
Profile and TS Output Increment= 10
XS Output Flag= 0
XS Output Increment= 10
Disregard all LS=0
Disregard all Conn=0
Disregard all Breaches=0
Disregard all Pumps=0

--- MeadowCreek.p02 (plan) ---

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Plan Title=Floodway Run
Short Identifier=FW
Geom File=g01
Flow File=f02
Encroach Param=-1 ,0,0, 2
Encroach River=MeadowCreek
Encroach Reach=Reach-1
Encroach Node=25085
       1    4939    5100
Encroach Node=24905
       1    4952    5074
Encroach Node=24741
       1  4962.1  5030.7
Encroach Node=24688
       1    4983  5028.2
Encroach Node=24565
       1  4985.3  5023.8
Encroach Node=24456
       1    4971  5025.1
Encroach Node=24289
       1  4979.3  5025.1
Encroach Node=24186
       1  4979.3    5031
Encroach Node=24061
       1    4957    5023
Encroach Node=23942
       1    4952    5060
Encroach Node=23630
       1    4920    5085
Encroach Node=23247
       1    4944    5060
Encroach Node=22977
       1    4942    5062
Encroach Node=22662
       1  4952.5    5088
Encroach Node=22310
       1  4880.5  5025.1
Encroach Node=22030
       1    4919    5042
Encroach Node=21769
       1  4969.8  5055.6
Encroach Node=21504
       1    4956  5063.5
Encroach Node=21260
       1    4963  5093.7
Encroach Node=20962
       1  4963.4    5065
Encroach Node=20702
       1  4964.8    5050
Encroach Node=20424
       1  4962.8  5046.5
Encroach Node=20097
       1  4961.8    5075
Encroach Node=19878
       1  4949.9  5063.3
Encroach Node=19588
       1    4923    5050
Encroach Node=19207
       1  4967.7  5035.5
Encroach Node=19125
       1    4975    5033
Encroach Node=19051
       1  4960.1  5031.2
Encroach Node=18838
       1  4974.5  5029.7
Encroach Node=18582
       1    4970  5033.6
Encroach Node=18220
       1  4974.5  5034.6
Encroach Node=17851
       1  4974.5    5050
Encroach Node=17638
       1  4973.1  5047.6
Encroach Node=17441
       1    4973  5037.4
Encroach Node=17213
       1  4978.1  5022.2
Encroach Node=16931
       1  4978.1  5022.2
Encroach Node=16684
       1  4965.6  5022.2
Encroach Node=16487
       1  4966.3    5040
Encroach Node=16285
       1    4965    5040
Encroach Node=16240
       1    4980  5031.9
Encroach Node=16150
       1    4950    5049
Encroach Node=15805
       1    4967    5040
Encroach Node=15504
       1  4958.1  5079.4
Encroach Node=15233
       1  4969.6    5071
Encroach Node=14918
       1  4948.3  5042.2
Encroach Node=14570
       1    4953    5069
Encroach Node=14179
       1    4929  5025.6
Encroach Node=13692
       1    4968  5037.8
Encroach Node=13445
       1  4962.4  5022.3
Encroach Node=13187
       1  4973.2  5050.8
Encroach Node=12955
       1  4937.3  5022.3
Encroach Node=12776
       1    4964  5064.5
Encroach Node=12517
       1    4973    5100
Encroach Node=12248
       1  4938.8  5106.9
Encroach Node=11827
       1  4892.5  5107.2
Encroach Node=11330
       1  4917.6  5096.5
Encroach Node=11036
       1  4897.8  5057.2
Encroach Node=10988
       1    4936    5040
Encroach Node=10933
       1    4969    5037
Encroach Node=10760
       1    4915  5060.7
Encroach Node=10333
       1    4915    5085
Encroach Node=10016
       1    4913    5090
Encroach Node=9726
       1    4940    5078
Encroach Node=9250
       1    4910    5026
Encroach Node=8969
       1    4915  5021.3
Encroach Node=8694
       1  4958.3  5062.2
Encroach Node=8499
       1  4978.4    5060
Encroach Node=8287
       1  4978.4    5057
Encroach Node=7979
       1  4952.3  5021.3
Encroach Node=7652
       1    4958  5027.3
Encroach Node=7402
       1  4972.6  5094.2
Encroach Node=7000
       1    4900    5035
Encroach Node=6670
       1    4923    5027
Encroach Node=6415
       1    4953    5022
Encroach Node=6080
       1    4970  5046.3
Encroach Node=5838
       1    4957  5022.2
Encroach Node=5515
       1  4956.9  5034.6
Encroach Node=5314
       1    4953  5022.2
Encroach Node=5095
       1  4973.8    5037
Encroach Node=4871
       1  4973.8    5050
Encroach Node=4564
       1  4973.8  5049.6
Encroach Node=4365
       1  4973.8  5028.6
Encroach Node=4123
       1  4973.8    5034
Encroach Node=3848
       1    4945    5100
Encroach Node=3314
       1  4961.4  5065.6
Encroach Node=3084
       1  4956.8  5035.4
Encroach Node=2925
       1    4963  5077.1
Encroach Node=2606
       1    4930    5100
Encroach Node=2362
       1    4965    5070
Encroach Node=2173
       1  4953.3  5068.1
Encroach Node=2077
       1  4951.5  5020.7
Encroach Node=2003
       1    4962  5024.1
Encroach Node=1904
       1    4950    5028
Encroach Node=1686
       1  4973.8    5060
Encroach Node=1422
       1  4973.8  5080.9
Encroach Node=1150
       1    4950    5030
Encroach Node=945
       1    4948    5045
Floodway Run

--- MeadowCreek.p03 (plan) ---

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Plan Title=Defined Future Condition Profiles
Short Identifier=DFC
Geom File=g01
Flow File=f03

--- MeadowCreek.f01 (steady flow) ---

Flow Title=Effective FIS 2006 Discharges
Program Version=4.10
Number of Profiles= 5
Profile Names=10%,4%,2%,1%,0.2%
River Rch & RM=MeadowCreek,Reach-1         ,25085
     704     998    1200    1490    2470
River Rch & RM=MeadowCreek,Reach-1         ,12776
     852    1200    1450    1790    2940
River Rch & RM=MeadowCreek,Reach-1         ,10333
    1120    1610    1950    2430    4090
Boundary for River Rch & Prof#=MeadowCreek,Reach-1         , 1
Up Type= 0
Dn Type= 3
Dn Slope=0.003
Boundary for River Rch & Prof#=MeadowCreek,Reach-1         , 2
Up Type= 0
Dn Type= 3
Dn Slope=0.003
Boundary for River Rch & Prof#=MeadowCreek,Reach-1         , 3
Up Type= 0
Dn Type= 3
Dn Slope=0.003
Boundary for River Rch & Prof#=MeadowCreek,Reach-1         , 4
Up Type= 0
Dn Type= 3
Dn Slope=0.003
Boundary for River Rch & Prof#=MeadowCreek,Reach-1         , 5
Up Type= 0
Dn Type= 3
Dn Slope=0.003
DSS Import GetInterval= 0
DSS Import GetPeak= 0
DSS Import FillOption= 0

--- MeadowCreek.f02 (steady flow) ---

Flow Title=FW Effective FIS 2006 Discharges
Program Version=4.10
Number of Profiles= 2
Profile Names=1%,1% FW
River Rch & RM=MeadowCreek,Reach-1         ,25085
    1490    1490
River Rch & RM=MeadowCreek,Reach-1         ,12776
    1790    1790
River Rch & RM=MeadowCreek,Reach-1         ,10333
    2430    2430
Boundary for River Rch & Prof#=MeadowCreek,Reach-1         , 1
Up Type= 0
Dn Type= 3
Dn Slope=0.003
Boundary for River Rch & Prof#=MeadowCreek,Reach-1         , 2
Up Type= 0
Dn Type= 3
Dn Slope=0.003
DSS Import GetInterval= 0
DSS Import GetPeak= 0
DSS Import FillOption= 0

--- MeadowCreek.f03 (steady flow) ---

Flow Title=DFC 01 USGS Urban Regression, FS 007-00
Program Version=4.10
Number of Profiles= 3
Profile Names=1%@10% Imp,1%@20% Imp,1%@35% Imp
River Rch & RM=MeadowCreek,Reach-1         ,25085
    1490    1490    1810
River Rch & RM=MeadowCreek,Reach-1         ,24289
    1490    1590    1940
River Rch & RM=MeadowCreek,Reach-1         ,21769
    1490    1770    2160
River Rch & RM=MeadowCreek,Reach-1         ,18838
    1510    1930    2360
River Rch & RM=MeadowCreek,Reach-1         ,15805
    1670    2130    2610
River Rch & RM=MeadowCreek,Reach-1         ,12517
    1860    2390    2920
River Rch & RM=MeadowCreek,Reach-1         ,10333
    2430    2510    3060
River Rch & RM=MeadowCreek,Reach-1         ,5838
    2430    2690    3290
River Rch & RM=MeadowCreek,Reach-1         ,1686
    2430    2840    3460
Boundary for River Rch & Prof#=MeadowCreek,Reach-1         , 1
Up Type= 0
Dn Type= 3
Dn Slope=0.003
Boundary for River Rch & Prof#=MeadowCreek,Reach-1         , 2
Up Type= 0
Dn Type= 3
Dn Slope=0.003
Boundary for River Rch & Prof#=MeadowCreek,Reach-1         , 3
Up Type= 0
Dn Type= 3
Dn Slope=0.003
DSS Import GetInterval= 0
DSS Import GetPeak= 0
DSS Import FillOption= 0

--- MeadowCreek.g01 (geometry) ---

Geom Title=NCFMP LiDAR, Survey Structures&Channel
Program Version=4.10

River Reach=MeadowCreek     ,Reach-1
Reach XY= 30
      1912009.43       819356.38      1911595.56       818899.81
      1910293.39       818599.34      1909920.05       818805.52
      1908353.84       818088.85      1905662.48       816306.61
      1905190.14       816293.32      1904930.82       815840.26
      1905014.83       814939.72      1904827.09       814436.51
      1904386.46       813990.73       1904500.9       813745.99
      1903399.33       812550.54      1903401.04       811902.03
      1902746.37       811604.28      1902878.66       811144.91
      1902401.48       810794.02       1902371.9       810253.95
      1901877.27       810035.78      1901580.66       810300.67
      1901352.03       811054.58      1900796.75       811373.92
      1899795.09       809800.98      1899518.61       809748.02
      1899108.02       810139.08       1898865.4       810774.93
      1898535.11       810346.11      1897862.36       810143.86
      1898023.39       809832.66        1897753.        809675.5

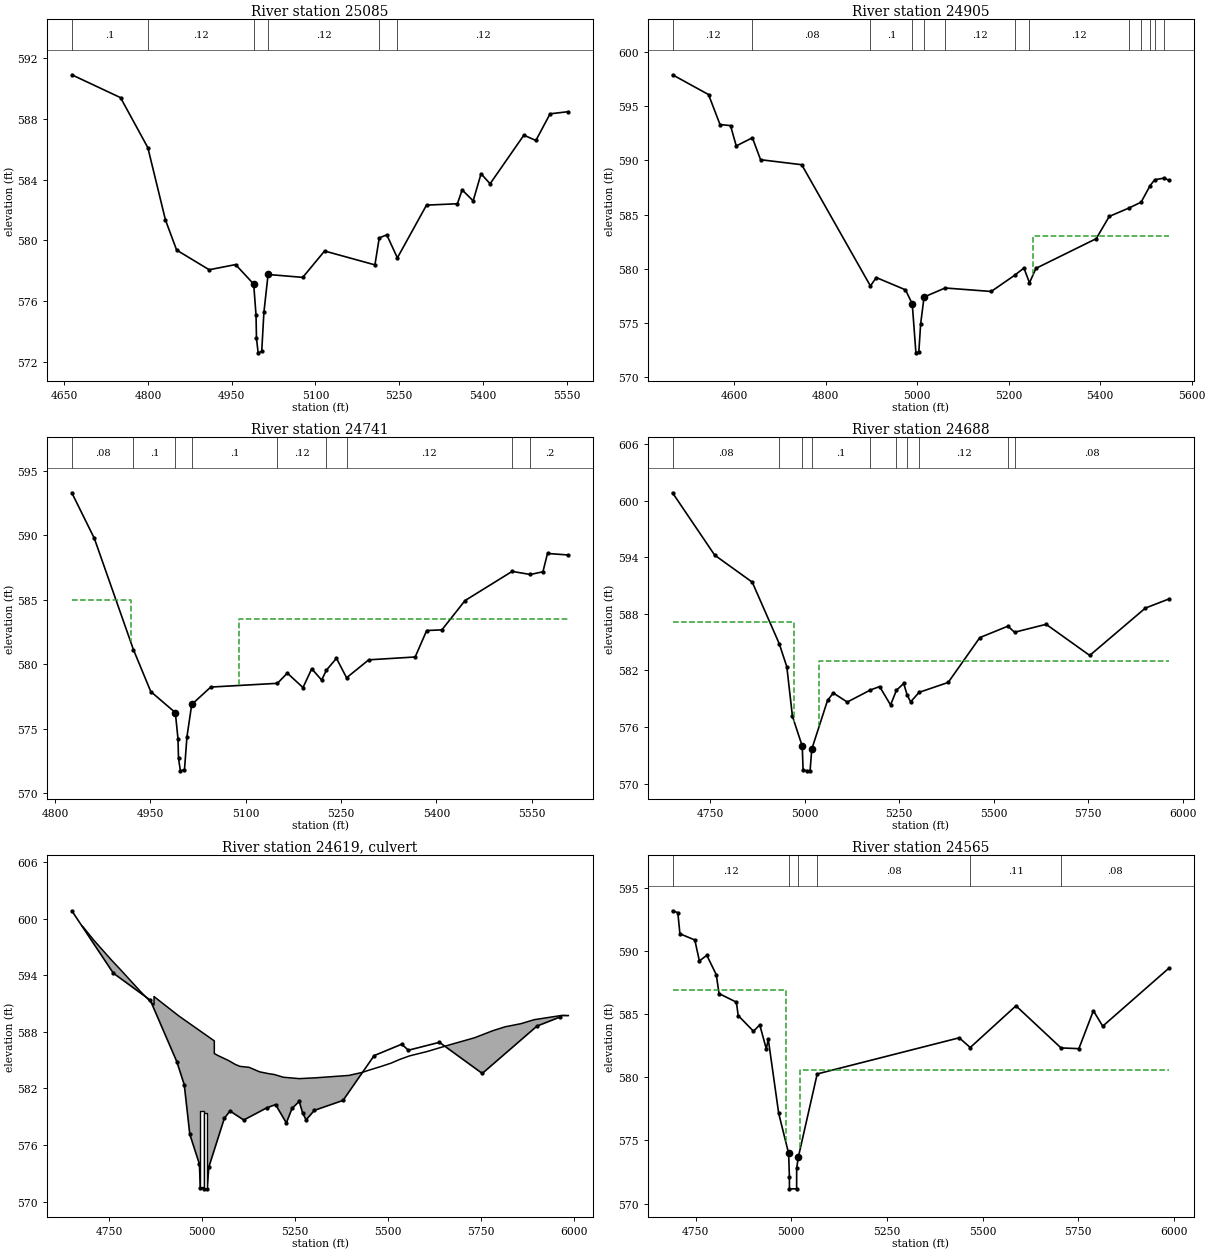
Type RM Length L Ch R = 1 ,25085   ,164,180,111
BEGIN DESCRIPTION:
Meadow Creek 86.0
END DESCRIPTION:
XS GIS Cut Line= 6
      1912345.14       819369.74      1912235.98       819360.57
      1912047.53       819342.77       1911972.8       819347.18
      1911701.06        819603.2      1911596.56       819700.02
#Sta/Elev= 30
  4663.5  590.87  4750.8  589.37  4799.7  586.09  4831.3  581.34  4851.3  579.37
  4909.6  578.08  4956.9  578.42  4989.3  577.14  4993.5  575.11  4994.3  573.59
  4997.3  572.63  5003.7  572.72  5007.6  575.28  5015.1  577.77  5077.2  577.58
  5116.3  579.31  5206.5   578.4  5214.2  580.17  5227.7  580.37  5246.7  578.86
  5298.9  582.32  5354.3  582.41  5362.7  583.32  5382.5   582.6  5396.6  584.38
  5412.8  583.72  5473.3  586.91  5494.8  586.56  5520.3  588.31    5553  588.45
#Mann= 6 ,-1 , 0
  4663.5      .1       0  4799.7     .12       0  4989.3     .05       0
  5015.1     .12       0  5214.2     .05       0  5246.7     .12       0
Bank Sta=4989.3,5015.1
XS Rating Curve= 0 ,0
Exp/Cntr=0.3,0.1

Type RM Length L Ch R = 1 ,24905   ,145,164,143
BEGIN DESCRIPTION:
Meadow Creek 85.0
END DESCRIPTION:
XS GIS Cut Line= 3
      1912395.04       819054.28      1912113.33       819073.81
      1911517.86        819612.4
#Sta/Elev= 30
  4465.3  597.87    4544  596.05  4569.1  593.29  4592.1  593.19  4604.6  591.32
  4639.9  592.07  4657.8  590.05  4747.7  589.59  4897.8  578.43  4910.8   579.2
  4974.5  578.07  4989.3  576.78  4997.3  572.27  5003.7  572.36  5007.6  574.92
  5015.1  577.41  5061.2  578.24  5161.9  577.92  5213.4  579.42  5233.4  580.08
  5245.5  578.72  5259.7  580.05  5391.3  582.78  5419.9  584.83  5463.3  585.61
  5489.5  586.14  5509.1  587.66  5519.3  588.21  5540.4  588.36  5550.6  588.14
#Mann= 13 ,-1 , 0
  4465.3     .12       0  4639.9     .08       0  4897.8      .1       0
  4989.3     .05       0  5015.1      .1       0  5061.2     .12       0
  5213.4     .05       0  5245.5     .12       0  5463.3      .1       0
  5489.5      .2       0  5509.1      .1       0  5519.3      .2       0
  5540.4      .1       0
#XS Ineff= 2 , 0
       0                    5253       0     583
Permanent Ineff=
       F       F
Bank Sta=4989.3,5015.1
XS Rating Curve= 0 ,0
Exp/Cntr=0.3,0.1

Type RM Length L Ch R = 1 ,24741   ,54,53,49
BEGIN DESCRIPTION:
Meadow Creek 84.0
END DESCRIPTION:
XS GIS Cut Line= 4
      1911967.87         819012.      1911843.45       819122.69
      1911495.99       819447.87      1911449.89       819578.45
#Sta/Elev= 30
  4826.5  593.28  4861.9  589.75  4923.4  581.13  4950.7  577.88  4989.3  576.25
  4993.5  574.22  4994.3   572.7  4997.3  571.74  5003.7  571.83  5007.6  574.39
  5015.1  576.88    5045  578.23  5149.9  578.52  5165.4  579.31  5190.1  578.19
  5203.8  579.65  5219.4  578.77  5226.8  579.53  5242.7  580.46  5258.6  578.95
  5293.5  580.34  5366.5  580.56  5384.6  582.61  5408.5  582.66  5444.9  584.93
    5519  587.19  5547.6  586.95  5567.4  587.16  5574.6  588.58  5607.4  588.46
#Mann= 9 ,-1 , 0
  4826.5     .08       0  4923.4      .1       0  4989.3     .05       0
  5015.1      .1       0  5149.9     .12       0  5226.8     .05       0
  5258.6     .12       0    5519      .1       0  5547.6      .2       0
#XS Ineff= 2 , 0
       0  4919.3     585  5089.8       0   583.5
Permanent Ineff=
       F       F
Bank Sta=4989.3,5015.1
XS Rating Curve= 0 ,0
Exp/Cntr=0.5,0.3

Type RM Length L Ch R = 1 ,24688   ,121,123,144
BEGIN DESCRIPTION:
Meadow Creek NC Hwy 54 US
END DESCRIPTION:
XS GIS Cut Line= 4
      1912057.04        818828.9       1911660.3       819237.44
      1911489.42       819434.17      1911173.86       819802.39
#Sta/Elev= 30
  4649.4  600.83  4761.1  594.22  4860.5  591.36  4931.9  584.85  4952.1  582.39
    4967  577.14    4993  573.97  4995.2  571.45  5005.7  571.36  5013.7  571.36
  5018.2  573.66    5060  578.83  5075.3  579.61  5112.2  578.65  5173.5  579.93
  5197.9  580.29  5226.9  578.34  5242.3  579.89  5261.6  580.62  5270.9  579.38
  5280.1  578.67  5302.5  579.68  5379.5  580.73  5463.2  585.48  5537.5  586.69
  5555.3  586.05  5638.9  586.89  5754.3  583.59  5901.6  588.61  5964.4  589.58
#Mann= 10 ,-1 , 0
  4649.4     .08       0  4931.9      .1       0    4993    .065       0
  5018.2      .1       0  5173.5     .12       0  5242.3     .05       0
  5270.9     .08       0  5302.5     .12       0  5537.5      .1       0
  5555.3     .08       0
#XS Ineff= 2 , 0
       0  4972.3  587.11  5036.8       0  583.04
Permanent Ineff=
       F       F
Bank Sta=4993,5018.2
XS Rating Curve= 0 ,0
Exp/Cntr=0.5,0.3

Type RM Length L Ch R = 2 ,24619   ,,,
BEGIN DESCRIPTION:
NC Hwy 54 (NC 54) - MEC_05 - Survey Date: 10/15/10
END DESCRIPTION:
Bridge Culvert--1,0,-1,-1, 0
Deck Dist Width WeirC Skew NumUp NumDn MinLoCord MaxHiCord MaxSubmerge Is_Ogee
23,92,3,0, 42, 42, 583.04, , 0.95, 0, 1,1,,
  4677.4  4679.6  4708.5  4728.3  4756.3    4780  4804.9  4833.9  4860.5  4870.7
  4870.7  4937.6    5033    5033  5042.7  5070.7  5089.8  5102.3  5126.5  5155.1
  5178.9  5194.1  5218.7  5261.5  5306.5  5395.1  5432.1  5447.2    5481  5509.3
  5530.5  5558.5  5605.5  5667.8  5733.4  5782.6  5815.4  5858.8  5894.2  5940.2
  5970.3    5986
   599.2  599.13  597.72  596.84   595.6  594.61  593.54  592.29  591.22  590.85
  591.74  589.68  587.04   585.7  585.49  584.97  584.54  584.34  584.24  583.76
  583.57  583.48  583.19  583.04  583.13  583.38  583.71  583.91  584.32  584.69
  585.05  585.45  585.91  586.64  587.37  588.12  588.53  588.87  589.29  589.57
  589.75  589.73
   551.7   551.7   551.7   551.7   551.7   551.7   551.7   551.7   551.7   551.7
   551.7   551.7   551.7   551.7   551.7   551.7   551.7   551.7   551.7   551.7
   551.7   551.7   551.7   551.7   551.7   551.7   551.7   551.7   551.7   551.7
   551.7   551.7   551.7   551.7   551.7   551.7   551.7   551.7   551.7   551.7
   551.7   551.7
  4677.4  4679.6  4708.5  4728.3  4756.3    4780  4804.9  4833.9  4860.5  4870.7
  4870.7  4937.6    5033    5033  5042.7  5070.7  5089.8  5102.3  5126.5  5155.1
  5178.9  5194.1  5218.7  5261.5  5306.5  5395.1  5432.1  5447.2    5481  5509.3
  5530.5  5558.5  5605.5  5667.8  5733.4  5782.6  5815.4  5858.8  5894.2  5940.2
  5970.3    5986
   599.2  599.13  597.72  596.84   595.6  594.61  593.54  592.29  591.22  590.85
  591.74  589.68  587.04   585.7  585.49  584.97  584.54  584.34  584.24  583.76
  583.57  583.48  583.19  583.04  583.13  583.38  583.71  583.91  584.32  584.69
  585.05  585.45  585.91  586.64  587.37  588.12  588.53  588.87  589.29  589.57
  589.75  589.73
   551.9   551.9   551.9   551.9   551.9   551.9   551.9   551.9   551.9   551.9
   551.9   551.9   551.9   551.9   551.9   551.9   551.9   551.9   551.9   551.9
   551.9   551.9   551.9   551.9   551.9   551.9   551.9   551.9   551.9   551.9
   551.9   551.9   551.9   551.9   551.9   551.9   551.9   551.9   551.9   551.9
   551.9   551.9
BR Coef=-1 , 0 , 0 ,, 0 ,,,0.8,-1,,0,
WSPro=,,,, 1 ,,,, 0 ,,,, 0 ,,,,-1 ,-1 ,-1 , 0 , 0 , 0 , 0 , 0
Culvert=2,8,9,93,0.012,0.2,1,9,1,571.57,4999.8,571.25,4999.8,Culvert #1  , 0 ,22
Culvert Bottom n=0.012
Culvert=2,8,9,93,0.012,0.2,1,9,1,571.45,5009.3,571.28,5009.3,Culvert #2  , 0 ,22
Culvert Bottom n=0.012
BC Design=,, 0 ,, 0 ,,,,,,
BC HTab HWMax=600.83
BC Use User HTab Curves=0
BC User HTab FreeFlow(D)= 0

Type RM Length L Ch R = 1 ,24565   ,118,109,81
BEGIN DESCRIPTION:
Meadow Creek NC Hwy 54 DS
END DESCRIPTION:
XS GIS Cut Line= 4
      1911953.15       818774.12      1911681.28       819038.14
      1911388.86       819356.14      1911076.85       819730.86
#Sta/Elev= 30
  4689.3  593.17  4703.2  593.02  4708.7  591.35  4747.6  590.86  4759.6   589.2
    4779  589.65  4803.8  588.11  4810.9  586.62  4856.3  585.94  4861.1  584.88
    4901  583.64  4917.5  584.14  4934.6  582.24  4939.7  583.02    4967  577.14
    4993  573.97    4995  572.11  4995.1  571.17  5013.9  571.17    5014  572.79
  5018.2  573.66  5067.7  580.26  5439.1  583.12  5467.9  582.35  5587.5  585.65
  5705.3  582.32    5752  582.26    5790  585.26  5814.4  584.04  5987.9  588.64
#Mann= 6 ,-1 , 0
  4689.3     .12       0    4993    .065       0  5018.2     .12       0
  5067.7     .08       0  5467.9     .11       0  5705.3     .08       0
#XS Ineff= 2 , 0
       0  4985.3  586.92  5023.8       0   580.6
Permanent Ineff=
       F       F
Bank Sta=4993,5018.2
XS Rating Curve= 0 ,0
Exp/Cntr=0.5,0.3

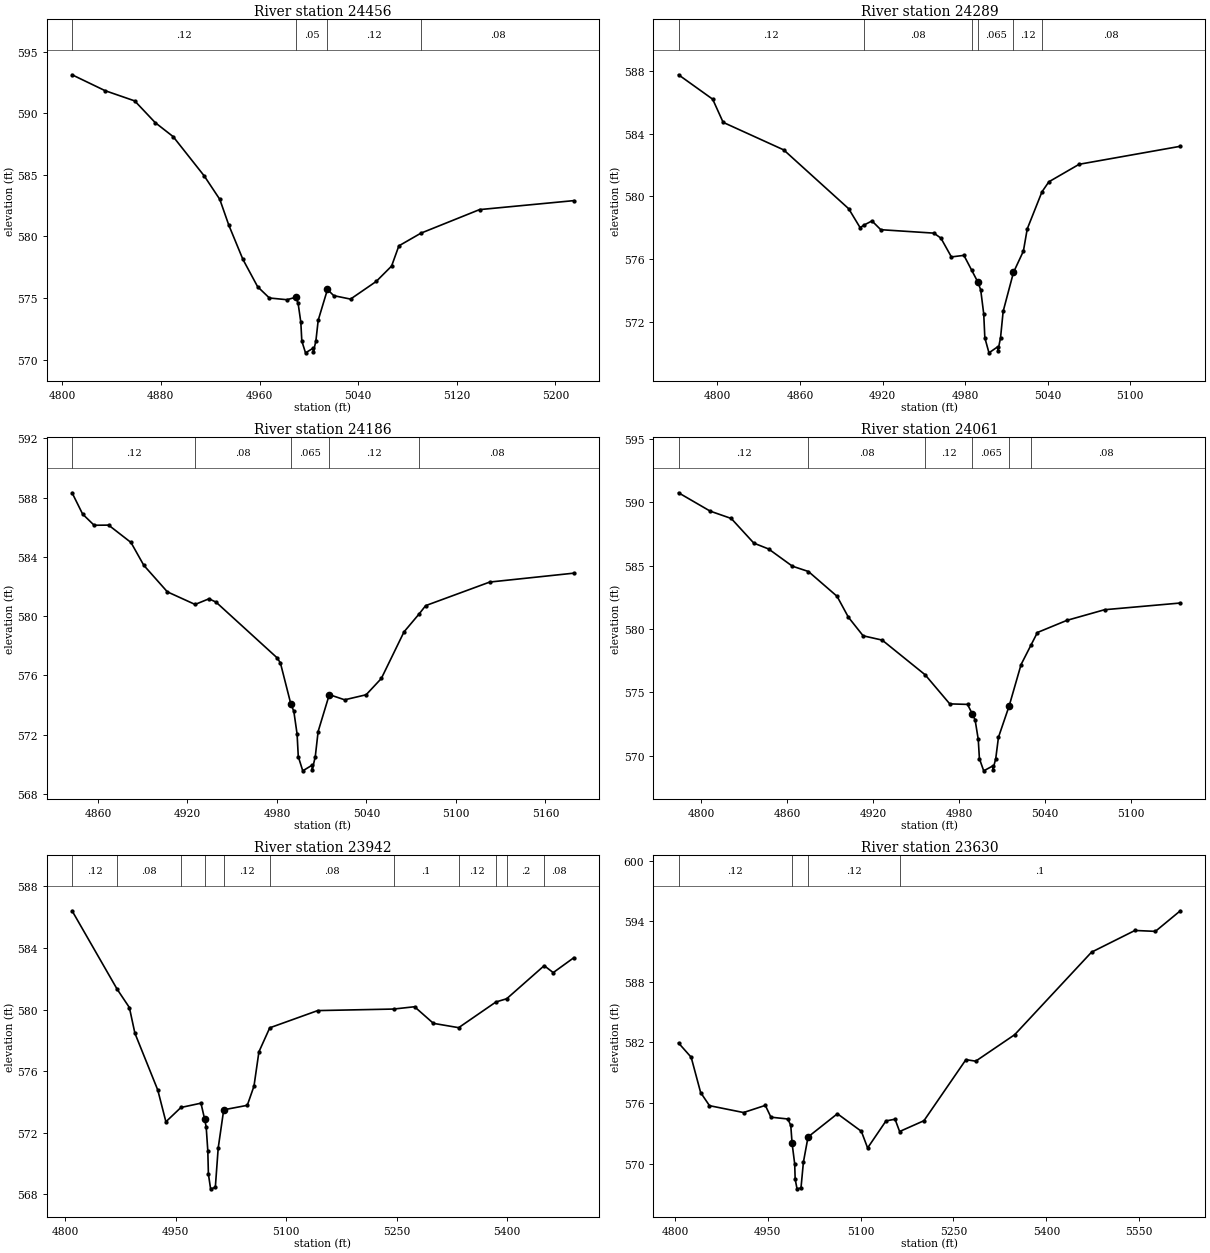
Type RM Length L Ch R = 1 ,24456   ,146,167,158
BEGIN DESCRIPTION:
Meadow Creek 83.0 (A_MEC_05DSX)
END DESCRIPTION:
XS GIS Cut Line= 3
      1911712.76       818739.15       1911633.2       818983.94
      1911507.96       819065.58
#Sta/Elev= 30
    4808  593.12  4834.8  591.83  4858.8     591  4875.4  589.24    4890   588.1
  4915.2  584.91  4927.8  583.01  4935.1  580.92  4946.5  578.15  4958.5  575.92
    4968  575.01  4982.3  574.87  4989.3  575.07  4991.3  574.58  4993.5  573.04
  4994.3  571.52  4997.3  570.56  5003.7  570.95  5003.7  570.65  5005.7  571.52
  5007.6  573.21  5015.1   575.7  5020.2   575.2  5033.8  574.92  5054.6  576.35
  5067.1   577.6    5073  579.24  5090.9  580.27  5138.4  582.18  5214.9  582.91
#Mann= 4 ,-1 , 0
    4808     .12       0  4989.3     .05       0  5015.1     .12       0
  5090.9     .08       0
Bank Sta=4989.3,5015.1
XS Rating Curve= 0 ,0
Exp/Cntr=0.3,0.1

Type RM Length L Ch R = 1 ,24289   ,107,103,85
BEGIN DESCRIPTION:
Meadow Creek 82.0
END DESCRIPTION:
XS GIS Cut Line= 4
      1911533.55       818691.08       1911538.8       818818.73
      1911474.56       818967.97      1911443.85       819035.59
#Sta/Elev= 30
  4771.8  587.77  4796.6  586.21  4804.2  584.73  4848.2  582.97  4895.4  579.21
  4903.7     578  4906.4  578.16  4912.3  578.43  4918.7  577.87  4957.3  577.65
  4962.4  577.33    4970  576.13  4979.1  576.23  4984.8  575.27  4989.3  574.51
  4991.3  574.02  4993.5  572.48  4994.3  570.96  4997.3     570  5003.7  570.39
  5003.7  570.09  5005.7  570.96  5007.6  572.65  5015.1  575.14  5022.3   576.5
  5025.1  577.92  5035.8  580.29  5040.8  580.93  5062.8  582.05  5136.3   583.2
#Mann= 6 ,-1 , 0
  4771.8     .12       0  4906.4     .08       0  4984.8     .12       0
  4989.3    .065       0  5015.1     .12       0  5035.8     .08       0
Bank Sta=4989.3,5015.1
XS Rating Curve= 0 ,0
Exp/Cntr=0.3,0.1

Type RM Length L Ch R = 1 ,24186   ,118,125,111
BEGIN DESCRIPTION:
Meadow Creek 81.0
END DESCRIPTION:
XS GIS Cut Line= 3
      1911411.18       818701.65      1911419.04       818817.86
      1911398.94       819036.96
#Sta/Elev= 30
  4842.6  588.32  4849.7  586.88  4857.4  586.13  4867.1  586.14  4882.1  584.97
  4890.7  583.43  4906.5  581.64  4925.1  580.79  4934.4  581.17  4939.1  580.95
    4980   577.2  4982.3  576.85  4989.3  574.08  4991.3  573.59  4993.5  572.05
  4994.3  570.53  4997.3  569.57  5003.7  569.96  5003.7  569.66  5005.7  570.53
  5007.6  572.22  5015.1  574.71  5025.4  574.36  5039.8   574.7    5050   575.8
  5065.2  578.94  5075.5  580.17  5079.7  580.71  5122.7   582.3  5179.1   582.9
#Mann= 5 ,-1 , 0
  4842.6     .12       0  4925.1     .08       0  4989.3    .065       0
  5015.1     .12       0  5075.5     .08       0
Bank Sta=4989.3,5015.1
XS Rating Curve= 0 ,0
Exp/Cntr=0.3,0.1

Type RM Length L Ch R = 1 ,24061   ,108,119,93
BEGIN DESCRIPTION:
Meadow Creek 80.0
END DESCRIPTION:
XS GIS Cut Line= 3
      1911293.17       818696.37       1911305.4       818946.36
      1911336.01       819041.67
#Sta/Elev= 30
  4784.2  590.76  4806.3  589.31    4821  588.73  4836.8  586.78  4847.1  586.32
  4863.7  584.96  4874.9  584.54  4894.9  582.58  4902.8  580.93  4913.1  579.46
  4926.4  579.12  4956.4  576.38  4973.6  574.08    4986  574.04  4989.3   573.3
  4991.3  572.81  4993.5  571.27  4994.3  569.75  4997.3  568.79  5003.7  569.18
  5003.7  568.88  5005.7  569.75  5007.6  571.44  5015.1  573.93  5023.4  577.19
  5030.2   578.7  5034.8  579.72  5055.4  580.68  5081.7  581.52  5134.6  582.05
#Mann= 6 ,-1 , 0
  4784.2     .12       0  4874.9     .08       0  4956.4     .12       0
  4989.3    .065       0  5015.1     .12       0  5030.2     .08       0
Bank Sta=4989.3,5015.1
XS Rating Curve= 0 ,0
Exp/Cntr=0.3,0.1

Type RM Length L Ch R = 1 ,23942   ,228,312,278
BEGIN DESCRIPTION:
Meadow Creek 79.0
END DESCRIPTION:
XS GIS Cut Line= 4
      1911216.24       818719.09      1911192.64       818811.74
      1911218.87       818979.57      1911257.96       819393.56
#Sta/Elev= 30
  4809.2  586.42  4870.4  581.32    4887  580.13  4894.5  578.46  4925.6  574.76
  4936.6   572.7    4957  573.63  4984.2  573.91  4989.3  572.85  4991.3  572.36
  4993.5  570.82  4994.3   569.3  4997.3  568.34  5003.7  568.43  5007.6  570.99
  5015.1  573.48  5047.1  573.77  5056.2  575.02  5062.9  577.25  5077.6  578.81
  5142.7  579.93  5245.7  580.03  5274.2  580.18  5299.8   579.1  5334.1  578.82
  5384.7  580.49  5399.3   580.7  5450.2  582.85  5462.5   582.4  5490.5  583.37
#Mann= 11 ,-1 , 0
  4809.2     .12       0  4870.4     .08       0    4957     .12       0
  4989.3    .065       0  5015.1     .12       0  5077.6     .08       0
  5245.7      .1       0  5334.1     .12       0  5384.7     .08       0
  5399.3      .2       0  5450.2     .08       0
Bank Sta=4989.3,5015.1
XS Rating Curve= 0 ,0
Exp/Cntr=0.3,0.1

Type RM Length L Ch R = 1 ,23630   ,392,383,349
BEGIN DESCRIPTION:
Meadow Creek 78.0
END DESCRIPTION:
XS GIS Cut Line= 4
      1911083.39       818613.29      1910972.36        818772.4
      1910905.05       819040.76      1910941.97       819378.55
#Sta/Elev= 30
  4805.9  581.95  4826.3  580.54  4841.6  577.04  4855.9  575.74  4910.9  575.06
  4946.1  575.77  4955.1   574.6  4982.5  574.42  4987.2  573.78  4989.3  572.01
  4993.5  569.98  4994.3  568.46  4997.3   567.5  5003.7  567.59  5007.6  570.15
  5015.1  572.64  5062.5  574.94  5101.2   573.2  5111.3  571.55    5141  574.23
  5155.6   574.4    5163  573.18  5202.3  574.25  5270.1   580.3  5285.9  580.15
  5348.8  582.77    5473  590.95  5543.1   593.1  5576.1  593.01  5616.4  595.05
#Mann= 4 ,-1 , 0
  4805.9     .12       0  4989.3    .065       0  5015.1     .12       0
    5163      .1       0
Bank Sta=4989.3,5015.1
XS Rating Curve= 0 ,0
Exp/Cntr=0.3,0.1

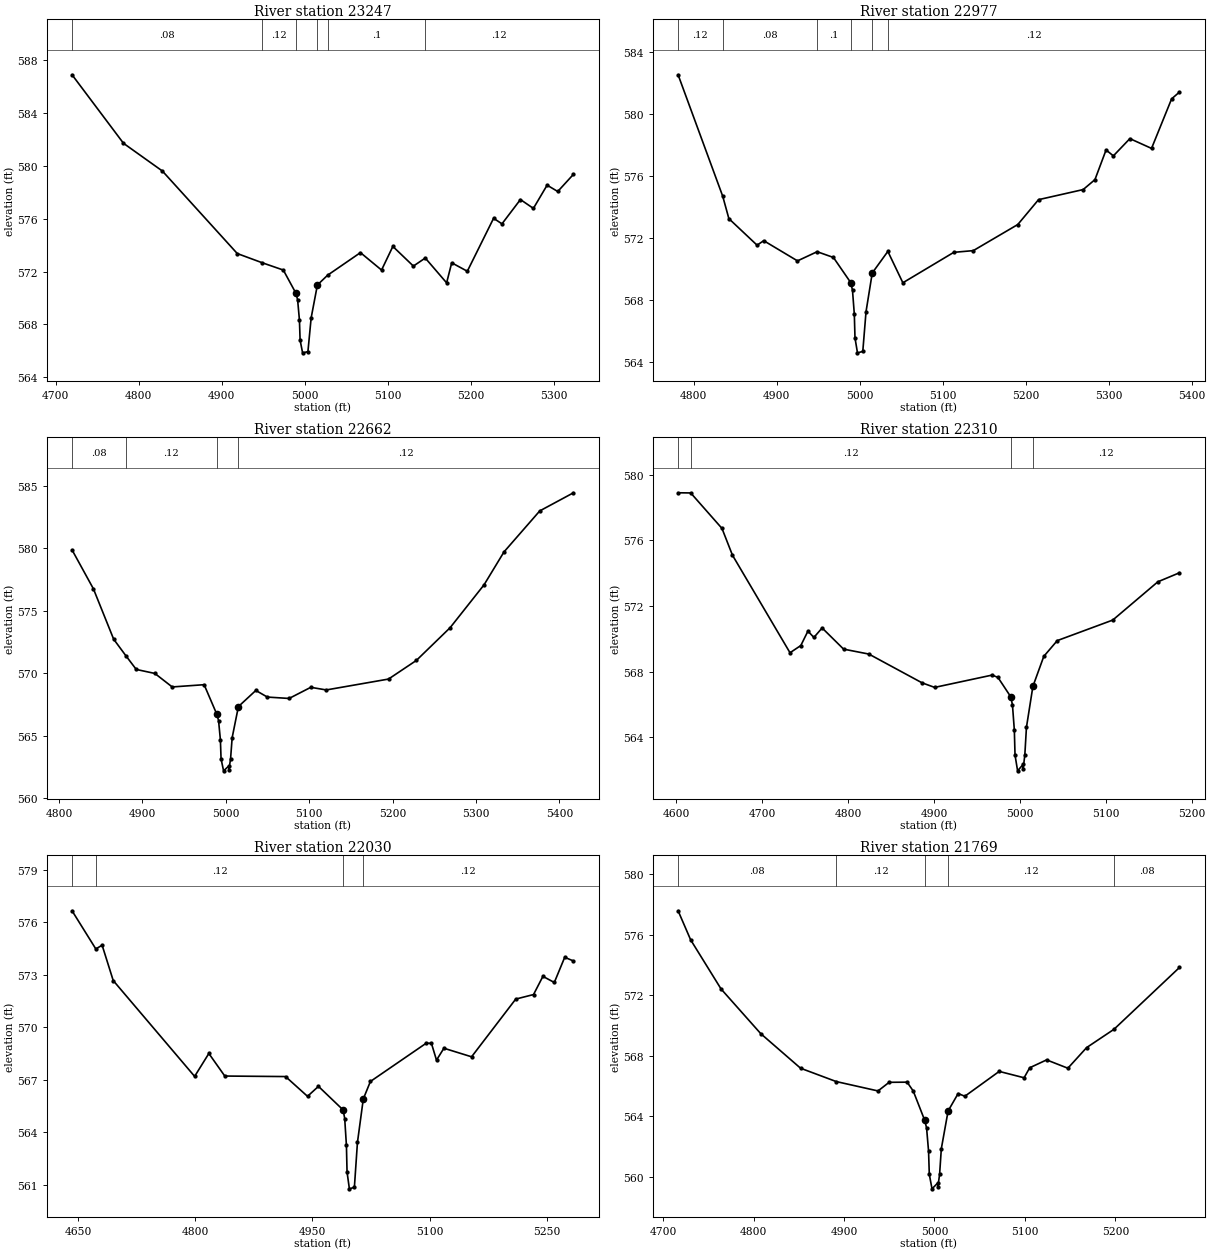
Type RM Length L Ch R = 1 ,23247   ,244,270,233
BEGIN DESCRIPTION:
Meadow Creek 77.0
END DESCRIPTION:
XS GIS Cut Line= 2
      1910639.05       818417.84      1910586.87       819018.88
#Sta/Elev= 30
  4719.9  586.91  4781.8  581.72  4828.6  579.62  4918.7  573.37  4948.4  572.68
  4974.1  572.12  4989.3  570.36  4991.3  569.87  4993.5  568.33  4994.3  566.81
  4997.3  565.85  5003.7  565.94  5007.6   568.5  5015.1  570.99  5027.4  571.73
  5066.9  573.44  5092.3  572.12  5105.9  573.91  5130.6  572.42  5144.9  573.03
  5170.6  571.15  5176.7  572.67  5195.5  572.03  5227.1  576.04  5237.2  575.62
  5259.4  577.46    5275  576.79  5291.5  578.55  5304.3  578.07  5323.2  579.37
#Mann= 6 ,-1 , 0
  4719.9     .08       0  4948.4     .12       0  4989.3    .065       0
  5015.1     .12       0  5027.4      .1       0  5144.9     .12       0
Bank Sta=4989.3,5015.1
XS Rating Curve= 0 ,0
Exp/Cntr=0.3,0.1

Type RM Length L Ch R = 1 ,22977   ,276,315,264
BEGIN DESCRIPTION:
Meadow Creek 76.0
END DESCRIPTION:
XS GIS Cut Line= 3
      1910390.19       818440.26      1910375.33       818816.11
      1910403.93       819042.47
#Sta/Elev= 30
  4781.1  582.52  4834.9   574.7  4842.3  573.26  4876.3  571.55  4884.3  571.84
    4925  570.54  4948.7  571.13  4968.3  570.76  4989.3  569.13  4991.3  568.64
  4993.5   567.1  4994.3  565.58  4997.3  564.62  5003.7  564.71  5007.6  567.27
  5015.1  569.76  5033.9  571.15    5052  569.13  5113.4  571.09  5136.9   571.2
  5190.5  572.88  5215.5  574.48  5269.3  575.13  5283.5  575.77  5296.9  577.68
  5305.7   577.3  5325.6  578.41  5351.7  577.78  5375.9  580.97  5385.4  581.41
#Mann= 6 ,-1 , 0
  4781.1     .12       0  4834.9     .08       0  4948.7      .1       0
  4989.3    .065       0  5015.1      .1       0  5033.9     .12       0
Bank Sta=4989.3,5015.1
XS Rating Curve= 0 ,0
Exp/Cntr=0.3,0.1

Type RM Length L Ch R = 1 ,22662   ,187,352,225
BEGIN DESCRIPTION:
Meadow Creek 75.0
END DESCRIPTION:
XS GIS Cut Line= 3
      1910145.42       818467.36       1910109.6       818551.25
      1910124.08       819061.13
#Sta/Elev= 30
  4815.6  579.87  4841.2  576.76  4865.5  572.73  4880.1  571.41  4892.6  570.31
  4914.9  569.99  4935.7  568.91    4974  569.09  4989.3  566.71  4991.3  566.22
  4993.5  564.68  4994.3  563.16  4997.3   562.2  5003.7  562.59  5003.7  562.29
  5005.7  563.16  5007.6  564.85  5015.1  567.34    5036  568.63  5049.8   568.1
  5075.9  567.99  5101.9  568.88  5120.5  568.67  5195.1  569.54  5228.5  571.03
    5269  573.65  5309.7  577.08  5333.6  579.71  5376.5  582.99  5416.9  584.44
#Mann= 4 ,-1 , 0
  4815.6     .08       0  4880.1     .12       0  4989.3    .065       0
  5015.1     .12       0
Bank Sta=4989.3,5015.1
XS Rating Curve= 0 ,0
Exp/Cntr=0.3,0.1

Type RM Length L Ch R = 1 ,22310   ,242,280,248
BEGIN DESCRIPTION:
Meadow Creek 74.0
END DESCRIPTION:
XS GIS Cut Line= 4
      1910030.09       818441.95      1909940.89       818516.28
      1909891.94       818854.57      1909837.75       818968.19
#Sta/Elev= 30
    4602   578.9  4616.7  578.89  4653.1  576.73  4665.3   575.1  4732.3  569.16
  4744.9   569.6  4753.2  570.48  4760.1  570.09  4769.7  570.67  4794.7  569.38
  4824.1  569.08    4886  567.33  4900.7  567.05  4967.6   567.8  4974.4  567.66
  4989.3  566.48  4991.3  565.99  4993.5  564.45  4994.3  562.93  4997.3  561.97
  5003.7  562.36  5003.7  562.06  5005.7  562.93  5007.6  564.62  5015.1  567.11
  5027.8  568.94  5043.5   569.9  5108.1  571.15  5160.6  573.48  5185.8  574.03
#Mann= 4 ,-1 , 0
    4602     .08       0  4616.7     .12       0  4989.3    .065       0
  5015.1     .12       0
Bank Sta=4989.3,5015.1
XS Rating Curve= 0 ,0
Exp/Cntr=0.3,0.1

Type RM Length L Ch R = 1 ,22030   ,240,261,264
BEGIN DESCRIPTION:
Meadow Creek 73.0
END DESCRIPTION:
XS GIS Cut Line= 3
      1909648.93       818293.38      1909694.39       818566.11
       1909633.2       818926.25
#Sta/Elev= 30
  4642.3  576.66  4672.7  574.48  4680.8  574.69    4695  572.67  4799.2  567.19
  4817.4   568.5  4837.8  567.21  4915.6  567.18  4943.7  566.05  4957.7  566.62
  4989.3  565.27  4991.3  564.78  4993.5  563.24  4994.3  561.72  4997.3  560.76
  5003.7  560.85  5007.6  563.41  5015.1   565.9  5024.2   566.9  5095.7  569.09
  5102.3  569.08  5108.8  568.12  5118.3   568.8  5153.7  568.31  5210.2  571.61
    5233  571.87    5245  572.91  5259.6  572.56  5272.9     574  5284.1  573.79
#Mann= 4 ,-1 , 0
  4642.3     .08       0  4672.7     .12       0  4989.3    .065       0
  5015.1     .12       0
Bank Sta=4989.3,5015.1
XS Rating Curve= 0 ,0
Exp/Cntr=0.3,0.1

Type RM Length L Ch R = 1 ,21769   ,250,265,254
BEGIN DESCRIPTION:
Meadow Creek 72.0
END DESCRIPTION:
XS GIS Cut Line= 3
      1909481.97       818296.04      1909468.86       818488.31
      1909358.72       818832.71
#Sta/Elev= 30
  4716.6  577.57  4730.5  575.65  4764.1  572.41    4808  569.46    4852  567.18
  4891.4   566.3  4937.6  565.68  4949.9  566.25  4969.8  566.26  4976.6  565.67
  4989.3  563.73  4991.3  563.24  4993.5   561.7  4994.3  560.18  4997.3  559.22
  5003.7  559.61  5003.7  559.31  5005.7  560.18  5007.6  561.87  5015.1  564.36
  5026.2  565.51  5033.6  565.33  5071.6  566.97  5099.1  566.55  5105.3  567.21
    5124  567.73  5147.5  567.18  5168.2  568.54  5198.5  569.75  5270.9  573.83
#Mann= 5 ,-1 , 0
  4716.6     .08       0  4891.4     .12       0  4989.3    .045       0
  5015.1     .12       0  5198.5     .08       0
Bank Sta=4989.3,5015.1
XS Rating Curve= 0 ,0
Exp/Cntr=0.3,0.1

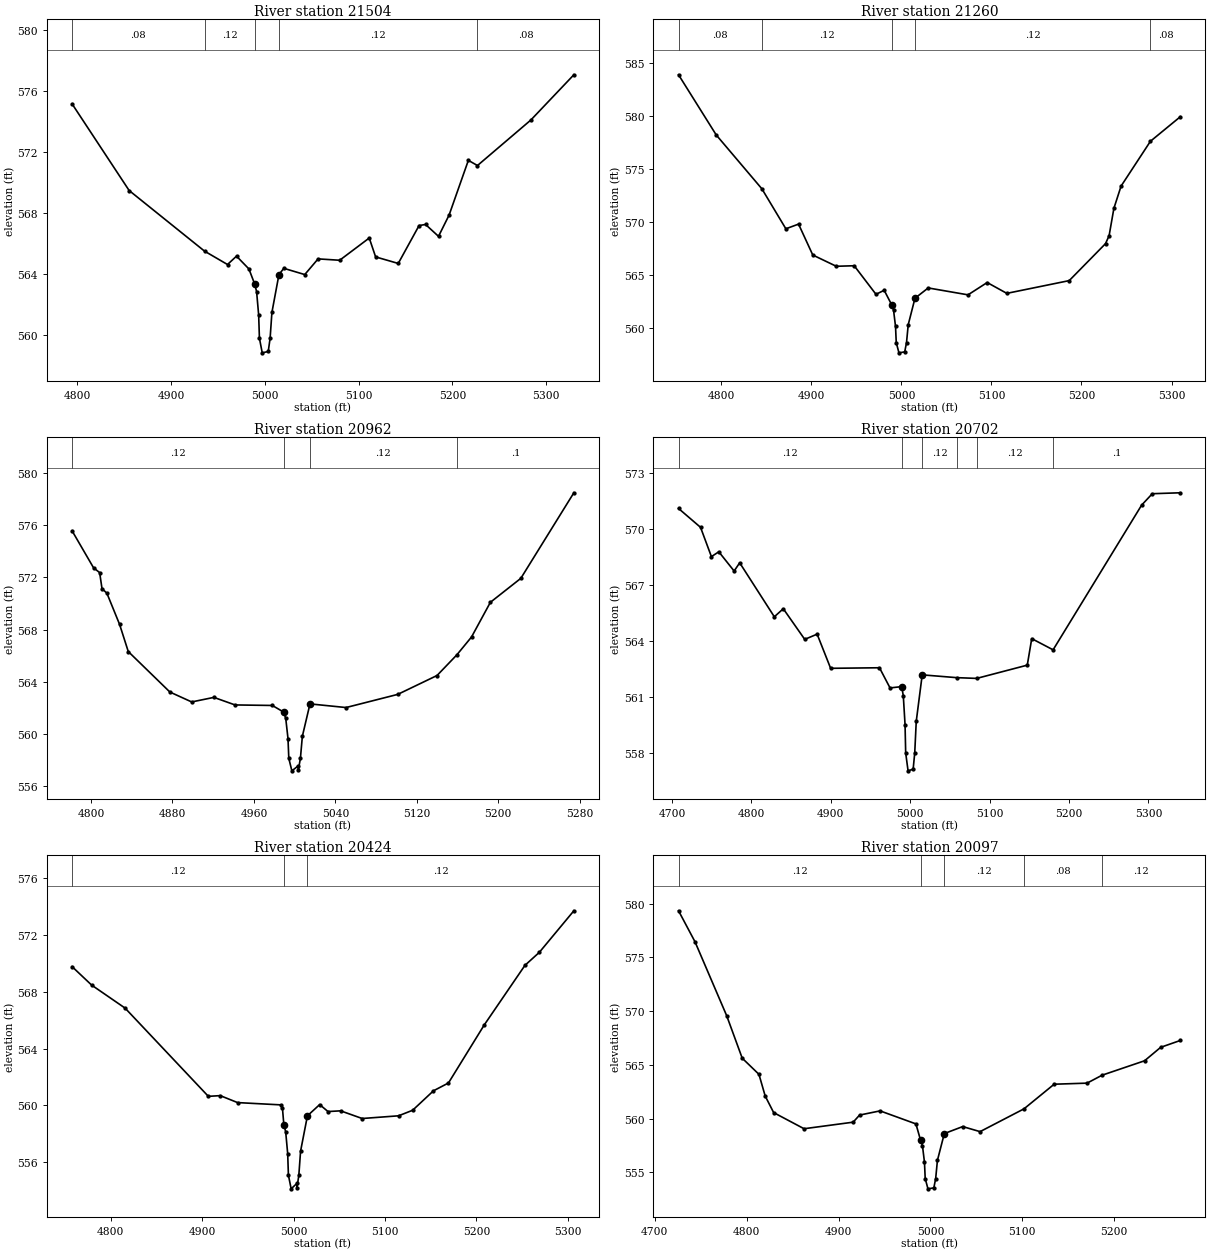
Type RM Length L Ch R = 1 ,21504   ,229,244,254
BEGIN DESCRIPTION:
Meadow Creek 71.0
END DESCRIPTION:
XS GIS Cut Line= 2
      1909283.54       818259.31      1909108.73       818764.52
#Sta/Elev= 30
  4794.7  575.16  4855.5  569.47  4935.8  565.49  4960.3  564.61  4969.9  565.16
  4983.1  564.32  4989.3  563.32  4991.3  562.83  4993.5  561.29  4994.3  559.77
  4997.3  558.81  5003.7   558.9  5005.7  559.77  5007.6  561.46  5015.1  563.95
  5020.3  564.36  5042.6  563.95  5056.8  564.98  5079.8  564.89  5111.3  566.35
  5118.1  565.11  5142.2  564.68  5164.4  567.17  5171.3  567.24  5185.1  566.46
  5196.4  567.86  5216.9  571.45  5226.6  571.11  5283.5   574.1  5329.3  577.07
#Mann= 5 ,-1 , 0
  4794.7     .08       0  4935.8     .12       0  4989.3    .045       0
  5015.1     .12       0  5226.6     .08       0
Bank Sta=4989.3,5015.1
XS Rating Curve= 0 ,0
Exp/Cntr=0.3,0.1

Type RM Length L Ch R = 1 ,21260   ,307,298,273
BEGIN DESCRIPTION:
Meadow Creek 70.0
END DESCRIPTION:
XS GIS Cut Line= 2
      1909132.34       818126.39      1908849.09       818606.35
#Sta/Elev= 30
  4752.5  583.85  4794.4  578.18  4845.1  573.11  4871.7  569.35  4885.8  569.79
  4901.6  566.88  4927.7  565.82  4947.6  565.87  4971.8  563.18  4980.9  563.56
  4989.3  562.18  4991.3  561.69  4993.5  560.15  4994.3  558.63  4997.3  557.67
  5003.7  557.76  5005.7  558.63  5007.6  560.32  5015.1  562.81  5029.8  563.78
    5074  563.13  5095.3  564.29  5117.1  563.27  5186.4  564.47  5226.7  567.95
  5230.7   568.7    5236  571.27    5244  573.37  5276.6  577.59  5309.8   579.9
#Mann= 5 ,-1 , 0
  4752.5     .08       0  4845.1     .12       0  4989.3    .045       0
  5015.1     .12       0  5276.6     .08       0
Bank Sta=4989.3,5015.1
XS Rating Curve= 0 ,0
Exp/Cntr=0.3,0.1

Type RM Length L Ch R = 1 ,20962   ,250,260,251
BEGIN DESCRIPTION:
Meadow Creek 69.0
END DESCRIPTION:
XS GIS Cut Line= 2
      1908794.91       818018.91      1908662.04       818493.56
#Sta/Elev= 30
  4781.4  575.58  4802.5  572.74  4808.5  572.37  4810.8  571.14  4815.6  570.79
  4828.1  568.39  4836.6  566.31  4877.5   563.2  4898.9  562.44  4920.7  562.79
  4941.5  562.21  4978.1  562.17  4989.3  561.66  4991.3  561.17  4993.5  559.63
  4994.3  558.11  4997.3  557.15  5003.7  557.54  5003.7  557.24  5005.7  558.11
  5007.6   559.8  5015.1  562.29  5050.5  562.01  5101.3  563.02  5139.9  564.47
  5159.3  566.05  5173.8  567.43  5192.3  570.09  5222.2  571.93  5274.3   578.5
#Mann= 4 ,-1 , 0
  4781.4     .12       0  4989.3    .045       0  5015.1     .12       0
  5159.3      .1       0
Bank Sta=4989.3,5015.1
XS Rating Curve= 0 ,0
Exp/Cntr=0.3,0.1

Type RM Length L Ch R = 1 ,20702   ,250,278,289
BEGIN DESCRIPTION:
Meadow Creek 68.0
END DESCRIPTION:
XS GIS Cut Line= 2
      1908588.19        817859.8       1908403.3       818463.94
#Sta/Elev= 30
  4708.3   571.1    4736  570.09  4749.7  568.52    4759  568.78  4778.3  567.75
  4785.3  568.19  4828.9   565.3  4840.2  565.73  4867.2  564.09  4882.8  564.37
  4899.8  562.54  4961.3  562.57  4974.6  561.49  4989.3  561.56  4991.3  561.07
  4993.5  559.53  4994.3  558.01  4997.3  557.05  5003.7  557.14  5005.7  558.01
  5007.6   559.7  5015.1  562.19  5058.6  562.04  5083.7     562  5147.4  562.71
    5153  564.13  5179.9  563.53  5291.4  571.28  5304.8  571.89  5340.1  571.94
#Mann= 6 ,-1 , 0
  4708.3     .12       0  4989.3    .045       0  5015.1     .12       0
  5058.6      .1       0  5083.7     .12       0  5179.9      .1       0
Bank Sta=4989.3,5015.1
XS Rating Curve= 0 ,0
Exp/Cntr=0.3,0.1

Type RM Length L Ch R = 1 ,20424   ,317,327,314
BEGIN DESCRIPTION:
Meadow Creek 67.0
END DESCRIPTION:
XS GIS Cut Line= 2
       1908390.2       817805.59      1908106.97       818275.89
#Sta/Elev= 30
  4757.6  569.77    4779  568.47  4815.6  566.85  4906.7  560.64  4919.7  560.69
  4938.7   560.2  4985.9  560.04  4987.8  559.79  4989.3  558.64  4991.3  558.15
  4993.5  556.61  4994.3  555.09  4997.3  554.13  5003.7  554.52  5003.7  554.22
  5005.7  555.09  5007.6  556.78  5015.1  559.27  5028.5  560.06  5037.6  559.57
  5051.4  559.62    5075  559.08  5114.8  559.27  5130.2  559.66    5153  561.03
  5169.4  561.58  5208.6  565.67  5253.1  569.86  5268.9  570.78  5306.6   573.7
#Mann= 3 ,-1 , 0
  4757.6     .12       0  4989.3    .045       0  5015.1     .12       0
Bank Sta=4989.3,5015.1
XS Rating Curve= 0 ,0
Exp/Cntr=0.3,0.1

Type RM Length L Ch R = 1 ,20097   ,220,219,214
BEGIN DESCRIPTION:
Meadow Creek 66.0
END DESCRIPTION:
XS GIS Cut Line= 3
      1908121.84        817565.2      1908067.63       817734.81
      1907885.84        818054.7
#Sta/Elev= 30
  4725.9  579.34  4743.8  576.46  4778.3  569.58  4795.2  565.63  4813.4  564.13
  4820.2  562.11  4829.4  560.57  4862.5  559.07  4915.9  559.68  4922.9  560.34
  4945.2  560.73  4984.2  559.52  4989.3  557.99  4991.3   557.5  4993.5  555.96
  4994.3  554.44  4997.3  553.48  5003.7  553.57  5005.7  554.44  5007.6  556.13
  5015.1  558.62  5035.1  559.27    5054   558.8  5101.8  560.92  5134.6  563.21
  5170.4  563.31  5186.8  564.05    5233  565.39  5250.5  566.64  5271.9  567.28
#Mann= 5 ,-1 , 0
  4725.9     .12       0  4989.3    .045       0  5015.1     .12       0
  5101.8     .08       0  5186.8     .12       0
Bank Sta=4989.3,5015.1
XS Rating Curve= 0 ,0
Exp/Cntr=0.3,0.1