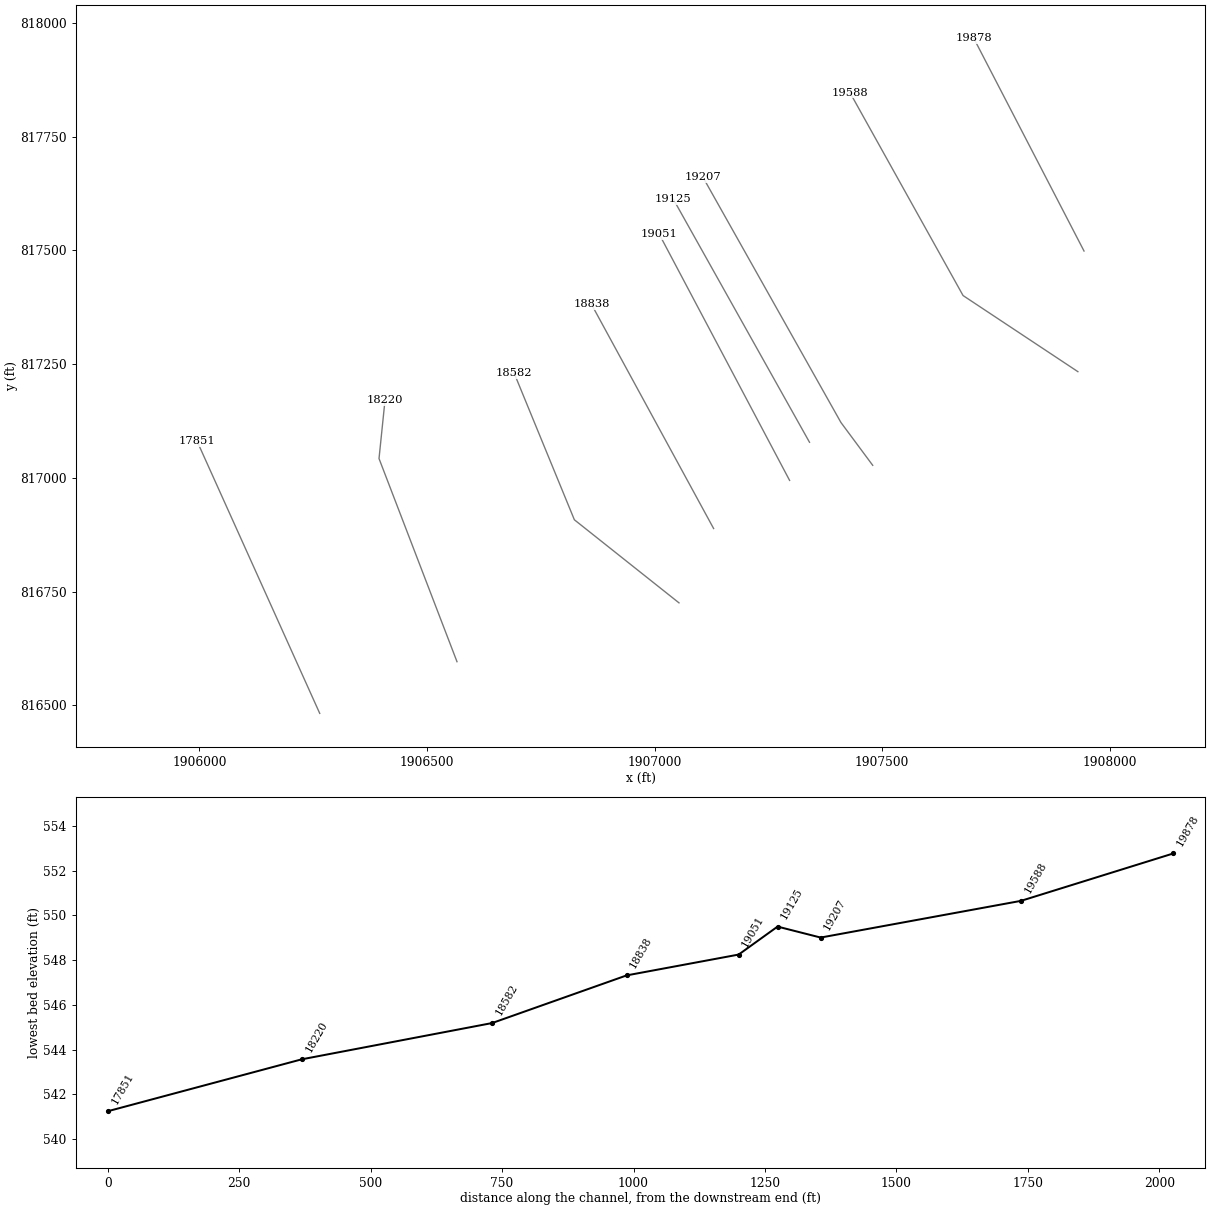
HEC-RAS study MeadowCreek.prj: MeadowCreek Detailed Study

--- MeadowCreek.g01 (geometry) --- (continued)

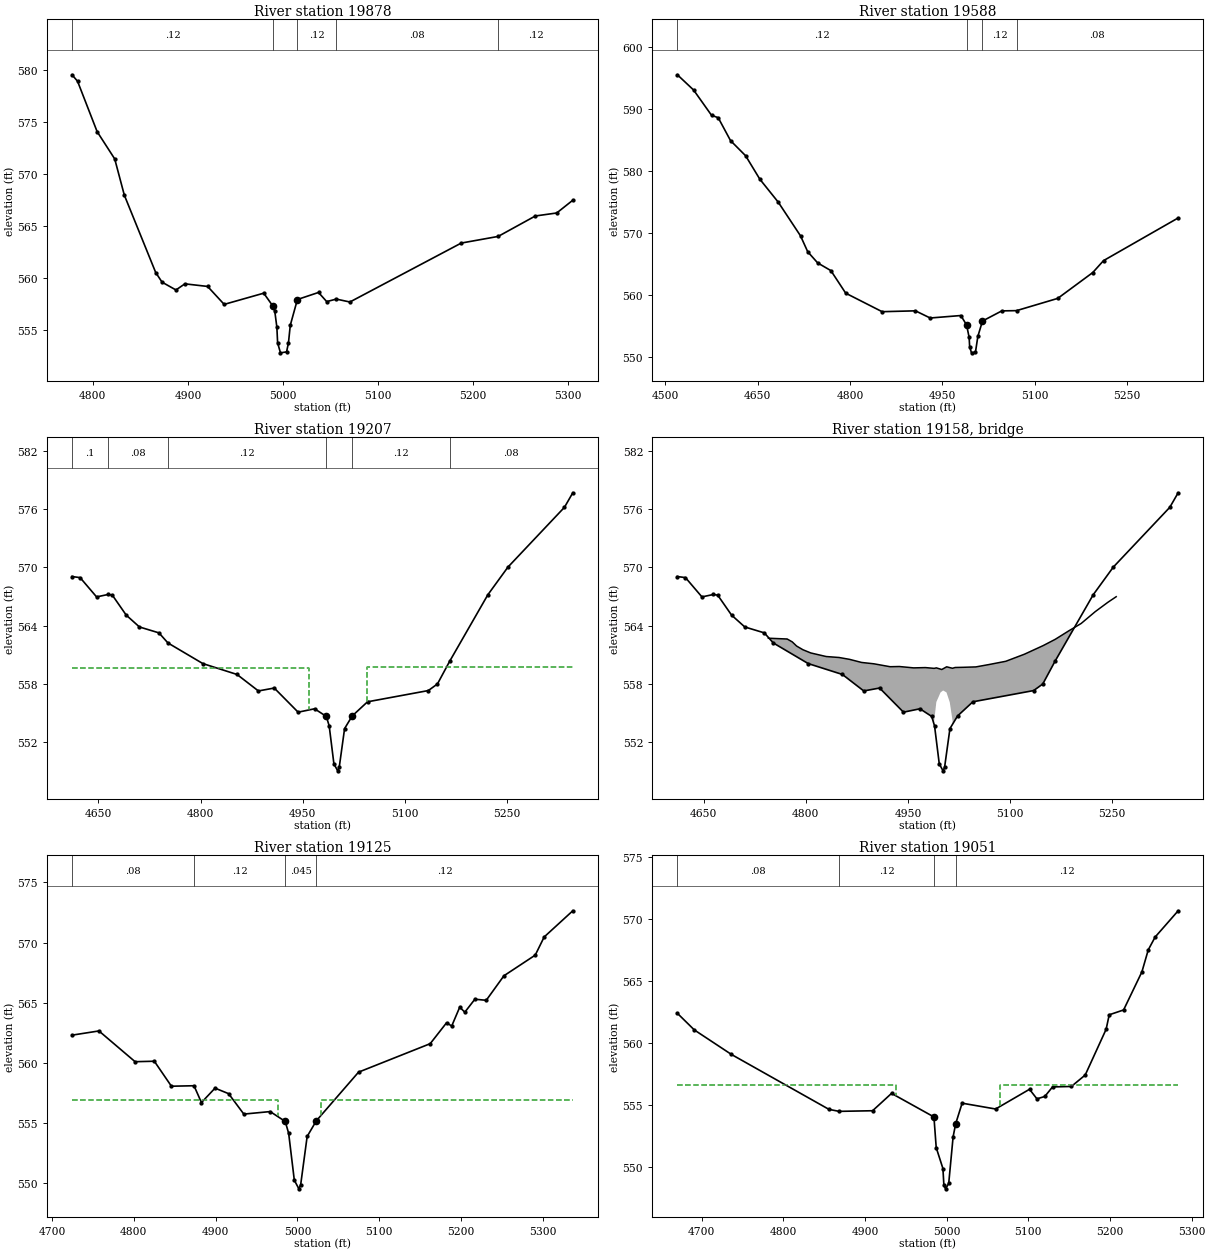
Type RM Length L Ch R = 1 ,19878   ,284,290,289
BEGIN DESCRIPTION:
Meadow Creek 65.0
END DESCRIPTION:
XS GIS Cut Line= 2
       1907943.5       817498.82      1907701.38       817966.45
#Sta/Elev= 30
  4778.1  579.57  4783.9  578.95  4804.5  574.09    4823  571.46  4833.1  567.97
  4866.1  560.51  4872.8  559.58  4887.4  558.83  4896.8  559.42  4920.7  559.17
  4938.1  557.44  4979.7  558.52  4989.3  557.28  4991.3  556.79  4993.5  555.25
  4994.3  553.73  4997.3  552.77  5003.7  552.86  5005.7  553.73  5007.6  555.42
  5015.1  557.91  5037.3  558.59  5045.9  557.71    5056  557.95  5070.3  557.67
  5187.4  563.35  5226.2  563.99  5265.3  565.96  5287.8  566.25  5304.7  567.48
#Mann= 5 ,-1 , 0
  4778.1     .12       0  4989.3    .045       0  5015.1     .12       0
    5056     .08       0  5226.2     .12       0
Bank Sta=4989.3,5015.1
XS Rating Curve= 0 ,0
Exp/Cntr=0.3,0.1

Type RM Length L Ch R = 1 ,19588   ,375,381,387
BEGIN DESCRIPTION:
Meadow Creek 64.0
END DESCRIPTION:
XS GIS Cut Line= 3
      1907930.05       817233.55      1907677.77        817400.9
      1907429.52        817846.7
#Sta/Elev= 30
  4519.8  595.59  4546.2  593.12  4575.2  589.05  4586.1  588.65  4606.1  584.95
  4630.6   582.5  4653.7  578.71  4683.5  575.01  4719.7  569.56  4731.4  566.99
  4747.6  565.18    4769  563.94  4793.1  560.29  4852.2   557.3  4906.3  557.44
  4930.2  556.28    4980  556.68  4989.3  555.16  4993.5  553.13  4994.3  551.61
  4997.3  550.65  5003.7  550.74  5007.6   553.3  5015.1  555.79  5046.5  557.43
  5070.4  557.47  5137.3  559.45  5194.2  563.63  5211.6  565.55  5332.8  572.45
#Mann= 4 ,-1 , 0
  4519.8     .12       0  4989.3    .045       0  5015.1     .12       0
  5070.4     .08       0
Bank Sta=4989.3,5015.1
XS Rating Curve= 0 ,0
Exp/Cntr=0.5,0.3

Type RM Length L Ch R = 1 ,19207   ,81,82,85
BEGIN DESCRIPTION:
Meadow Creek Phillips Chapel Rd US
END DESCRIPTION:
XS GIS Cut Line= 3
      1907479.24       817027.63      1907409.47       817121.74
      1907106.11       817661.36
#Sta/Elev= 30
  4611.1  569.05    4623  568.94  4647.2  566.95  4664.1   567.2  4670.4  567.13
  4690.8  565.07  4710.2  563.85  4738.9  563.24  4752.1   562.2  4803.5  560.07
  4853.7  558.95  4885.1  557.25  4908.4  557.55  4943.5  555.06  4967.7  555.41
    4985  554.62  4989.2  553.63  4996.1  549.73  5001.7  549.01  5003.9  549.36
  5011.8  553.37    5023  554.67  5045.5  556.13  5134.9  557.29  5148.3  557.97
  5166.1  560.29  5222.4  567.17  5251.9  570.02    5335  576.19  5347.3  577.69
#Mann= 6 ,-1 , 0
  4611.1      .1       0  4664.1     .08       0  4752.1     .12       0
    4985    .045       0    5023     .12       0  5166.1     .08       0
#XS Ineff= 2 , 0
       0  4959.6  559.63  5044.6       0  559.72
Permanent Ineff=
       F       F
Bank Sta=4985,5023
XS Rating Curve= 0 ,0
Exp/Cntr=0.5,0.3

Type RM Length L Ch R = 3 ,19158   ,,,
BEGIN DESCRIPTION:
Phillips Chapel Road (SR 2151) - MEC_04 - Survey Date: 10/15/10
END DESCRIPTION:
Bridge Culvert--1,0,-1,-1, 0
Deck Dist Width WeirC Skew NumUp NumDn MinLoCord MaxHiCord MaxSubmerge Is_Ogee
29,40,3,0, 40, 40, 559.5, , 0.95, 0, 1,1,,
  4744.9  4771.9  4772.2    4780  4786.4  4795.7  4807.2  4829.9  4848.9  4864.2
  4881.9  4900.1  4923.8  4937.5  4958.4  4975.8  4988.6  4988.6  4991.8    4998
  4999.7  5001.8  5006.7    5007  5011.5  5015.6  5015.6  5019.4  5031.9  5049.9
  5068.9  5093.9  5121.3  5148.9  5166.7  5186.3  5204.7  5225.4  5243.9  5256.2
  562.69  562.61  562.62  562.31  561.88   561.5  561.17   560.8   560.7  560.51
  560.19  560.05  559.75  559.77  559.63  559.66  559.58  559.58  559.63   559.5
  559.46  559.54  559.73  559.74  559.66  559.59  559.59  559.67  559.69  559.73
  559.97  560.31  561.04  561.93  562.58  563.44  564.21  565.43  566.39  566.97
  529.01  529.01  529.01  529.01  529.01  529.01  529.01  529.01  529.01  529.01
  529.01  529.01  529.01  529.01  529.01  529.01  529.01   554.1  556.11   557.1
  557.19   557.3   557.1  557.04   556.1   554.2  529.01  529.01  529.01  529.01
  529.01  529.01  529.01  529.01  529.01  529.01  529.01  529.01  529.01  529.01
  4744.9  4771.9  4772.2    4780  4786.4  4795.7  4807.2  4829.9  4848.9  4864.2
  4881.9  4900.1  4923.8  4937.5  4958.4  4975.8  4988.6  4988.6  4991.8    4998
  4999.7  5001.8  5006.7    5007  5011.5  5015.6  5015.6  5019.4  5031.9  5049.9
  5068.9  5093.9  5121.3  5148.9  5166.7  5186.3  5204.7  5225.4  5243.9  5256.2
  562.69  562.61  562.62  562.31  561.88   561.5  561.17   560.8   560.7  560.51
  560.19  560.05  559.75  559.77  559.63  559.66  559.58  559.58  559.63   559.5
  559.46  559.54  559.73  559.74  559.66  559.59  559.59  559.67  559.69  559.73
  559.97  560.31  561.04  561.93  562.58  563.44  564.21  565.43  566.39  566.97
  529.01  529.01  529.01  529.01  529.01  529.01  529.01  529.01  529.01  529.01
  529.01  529.01  529.01  529.01  529.01  529.01  529.01   554.1  556.11   557.1
  557.19   557.3   557.1  557.04   556.1   554.2  529.01  529.01  529.01  529.01
  529.01  529.01  529.01  529.01  529.01  529.01  529.01  529.01  529.01  529.01
BR Coef= 1 , 1 , 0 ,, 0 ,,,0.8,0,1.2,0,
WSPro=,,,, 1 ,,,, 0 ,,,, 0 ,,,,-1 ,-1 ,-1 , 0 , 0 , 0 , 0 , 0
BC Design=,, 0 ,, 0 ,,,,,,
BC HTab HWMax=577.69
BC Use User HTab Curves=0
BC User HTab FreeFlow(D)= 0

Type RM Length L Ch R = 1 ,19125   ,79,74,72
BEGIN DESCRIPTION:
Meadow Creek Phillips Chapel Rd DS
END DESCRIPTION:
XS GIS Cut Line= 2
      1907340.38       817078.31      1907041.41       817612.43
#Sta/Elev= 30
  4724.4  562.29  4757.3  562.64  4801.5  560.08    4825  560.12  4845.9  558.04
  4873.5  558.08  4882.6  556.68  4899.2  557.88  4915.8  557.42  4934.4  555.72
  4966.6  555.93    4985  555.11  4989.2  554.12  4996.1  550.22  5001.7   549.5
  5003.9  549.85  5011.8  553.86    5023  555.16  5074.6  559.21  5162.2  561.58
  5182.2  563.32  5188.5  563.05  5198.3  564.62  5204.5   564.2  5216.8  565.28
  5230.7  565.19  5252.3  567.23  5290.6  568.95  5301.5  570.46  5336.5  572.64
#Mann= 4 ,-1 , 0
  4724.4     .08       0  4873.5     .12       0    4985    .045       0
    5023     .12       0
#XS Ineff= 2 , 0
       0  4975.6   556.9  5028.6       0   556.9
Permanent Ineff=
       F       F
Bank Sta=4985,5023
XS Rating Curve= 0 ,0
Exp/Cntr=0.5,0.3

Type RM Length L Ch R = 1 ,19051   ,217,213,202
BEGIN DESCRIPTION:
Meadow Creek 63.0 (A_MEC_04DSX)
Crossing profiles could not be resolved using generally accepted modeling practices.
END DESCRIPTION:
XS GIS Cut Line= 2
      1907296.65       816994.44      1907009.95       817536.37
#Sta/Elev= 30
  4670.4  562.41  4691.1  561.07  4736.6  559.09    4856  554.66  4868.4   554.5
  4909.4  554.55  4932.6  555.95  4984.5  554.05  4987.3  551.57  4995.5  549.89
  4996.7  548.52  4998.8  548.25  5002.6  548.69    5008  552.46  5011.2  553.52
    5019  555.16    5060  554.69  5101.5  556.28  5110.6  555.51  5120.2   555.7
  5129.7  556.47  5152.8  556.51  5169.7  557.43  5195.3  561.12  5199.1  562.29
  5216.7  562.68  5239.1  565.75  5246.9  567.53  5255.3  568.56  5283.5  570.68
#Mann= 4 ,-1 , 0
  4670.4     .08       0  4868.4     .12       0  4984.5    .045       0
  5011.2     .12       0
#XS Ineff= 2 , 0
       0  4938.6   556.6  5065.6       0   556.6
Permanent Ineff=
       F       F
Bank Sta=4984.5,5011.2
XS Rating Curve= 0 ,0
Exp/Cntr=0.3,0.1

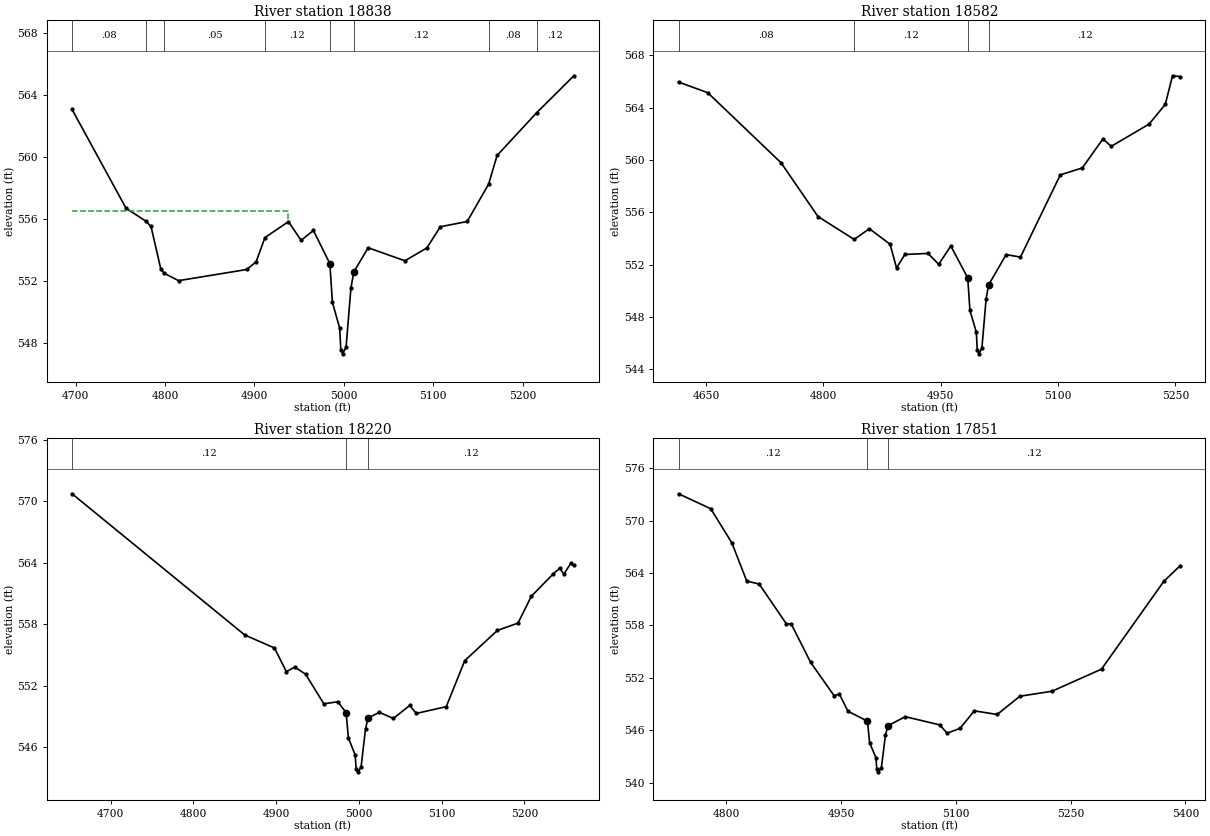
Type RM Length L Ch R = 1 ,18838   ,258,256,251
BEGIN DESCRIPTION:
Meadow Creek 62.0
END DESCRIPTION:
XS GIS Cut Line= 2
      1907129.71       816888.63      1906861.36       817381.63
#Sta/Elev= 30
  4696.1  563.05  4756.5  556.69  4778.4  555.87  4784.4  555.52  4795.5  552.75
  4799.4   552.5  4815.2  552.03  4891.6  552.75    4902  553.25  4911.8   554.8
  4938.1  555.83  4952.3  554.63  4966.1  555.26  4984.5  553.12  4987.3  550.64
  4995.5  548.96  4996.7  547.59  4998.8  547.32  5002.6  547.76    5008  551.53
  5011.2  552.59  5027.3  554.15  5068.4  553.31    5093  554.14    5108   555.5
  5138.1  555.84  5162.1  558.25  5171.5  560.09  5215.8  562.84  5257.4  565.22
#Mann= 8 ,-1 , 0
  4696.1     .08       0  4778.4     .12       0  4799.4     .05       0
  4911.8     .12       0  4984.5    .045       0  5011.2     .12       0
  5162.1     .08       0  5215.8     .12       0
#XS Ineff= 2 , 0
       0  4938.1   556.5               0
Permanent Ineff=
       F       F
Bank Sta=4984.5,5011.2
XS Rating Curve= 0 ,0
Exp/Cntr=0.3,0.1

Type RM Length L Ch R = 1 ,18582   ,363,362,358
BEGIN DESCRIPTION:
Meadow Creek 61.0
END DESCRIPTION:
XS GIS Cut Line= 3
      1907053.64        816725.2      1906823.75       816907.89
      1906691.77       817229.53
#Sta/Elev= 30
  4614.9  565.95  4652.2  565.14    4746  559.78  4793.1  555.68  4839.4  553.93
  4858.8  554.75  4885.3  553.56  4893.5  551.75  4904.1  552.78  4933.8  552.86
  4947.4  552.03  4962.9  553.43  4984.5  550.99  4987.3  548.51  4995.5  546.83
  4996.7  545.46  4998.8  545.19  5002.6  545.63    5008   549.4  5011.2  550.46
  5033.6  552.77  5051.9  552.58  5102.8  558.86  5130.9  559.39  5157.3  561.61
  5167.9  561.04  5216.3  562.74    5237  564.25  5246.2  566.43  5256.2  566.37
#Mann= 4 ,-1 , 0
  4614.9     .08       0  4839.4     .12       0  4984.5    .045       0
  5011.2     .12       0
Bank Sta=4984.5,5011.2
XS Rating Curve= 0 ,0
Exp/Cntr=0.3,0.1

Type RM Length L Ch R = 1 ,18220   ,345,369,346
BEGIN DESCRIPTION:
Meadow Creek 60.0
END DESCRIPTION:
XS GIS Cut Line= 3
      1906565.87       816595.86      1906394.55        817042.5
      1906407.67       817170.15
#Sta/Elev= 30
  4653.2  570.75  4862.1  556.94  4897.9  555.68  4912.3  553.36  4922.4  553.81
  4935.5  553.12  4957.6  550.22  4974.5  550.42  4984.5  549.37  4987.3  546.89
  4995.5  545.21  4996.7  543.84  4998.8  543.57  5002.6  544.01    5008  547.78
  5011.2  548.84  5024.7  549.38  5041.8  548.79  5061.4  550.06  5069.4  549.28
  5105.6  549.94    5128  554.44  5167.4  557.39  5192.4  558.11  5208.4  560.72
  5234.9  562.92  5242.8  563.46  5247.9  562.89    5256  563.94  5259.9  563.75
#Mann= 3 ,-1 , 0
  4653.2     .12       0  4984.5    .045       0  5011.2     .12       0
Bank Sta=4984.5,5011.2
XS Rating Curve= 0 ,0
Exp/Cntr=0.3,0.1

Type RM Length L Ch R = 1 ,17851   ,196,213,234
BEGIN DESCRIPTION:
Meadow Creek 59.0
END DESCRIPTION:
XS GIS Cut Line= 2
      1906264.29       816482.22      1905995.07       817080.11
#Sta/Elev= 30
  4737.6  573.06  4779.7  571.35  4807.2  567.46  4826.7  563.08    4843  562.73
  4878.6  558.17  4884.8  558.18  4910.1  553.79  4940.8  549.97  4947.8  550.14
    4959  548.18  4984.5  547.05  4987.3  544.57  4995.5  542.89  4996.7  541.52
  4998.8  541.25  5002.6  541.69    5008  545.46  5011.2  546.52  5033.9  547.56
    5079  546.62  5088.5  545.67  5105.4  546.22  5124.1  548.23    5154  547.81
  5183.6   549.9  5225.6  550.47  5290.3     553  5371.8  563.05  5393.3  564.85
#Mann= 3 ,-1 , 0
  4737.6     .12       0  4984.5    .045       0  5011.2     .12       0
Bank Sta=4984.5,5011.2
XS Rating Curve= 0 ,0
Exp/Cntr=0.3,0.1