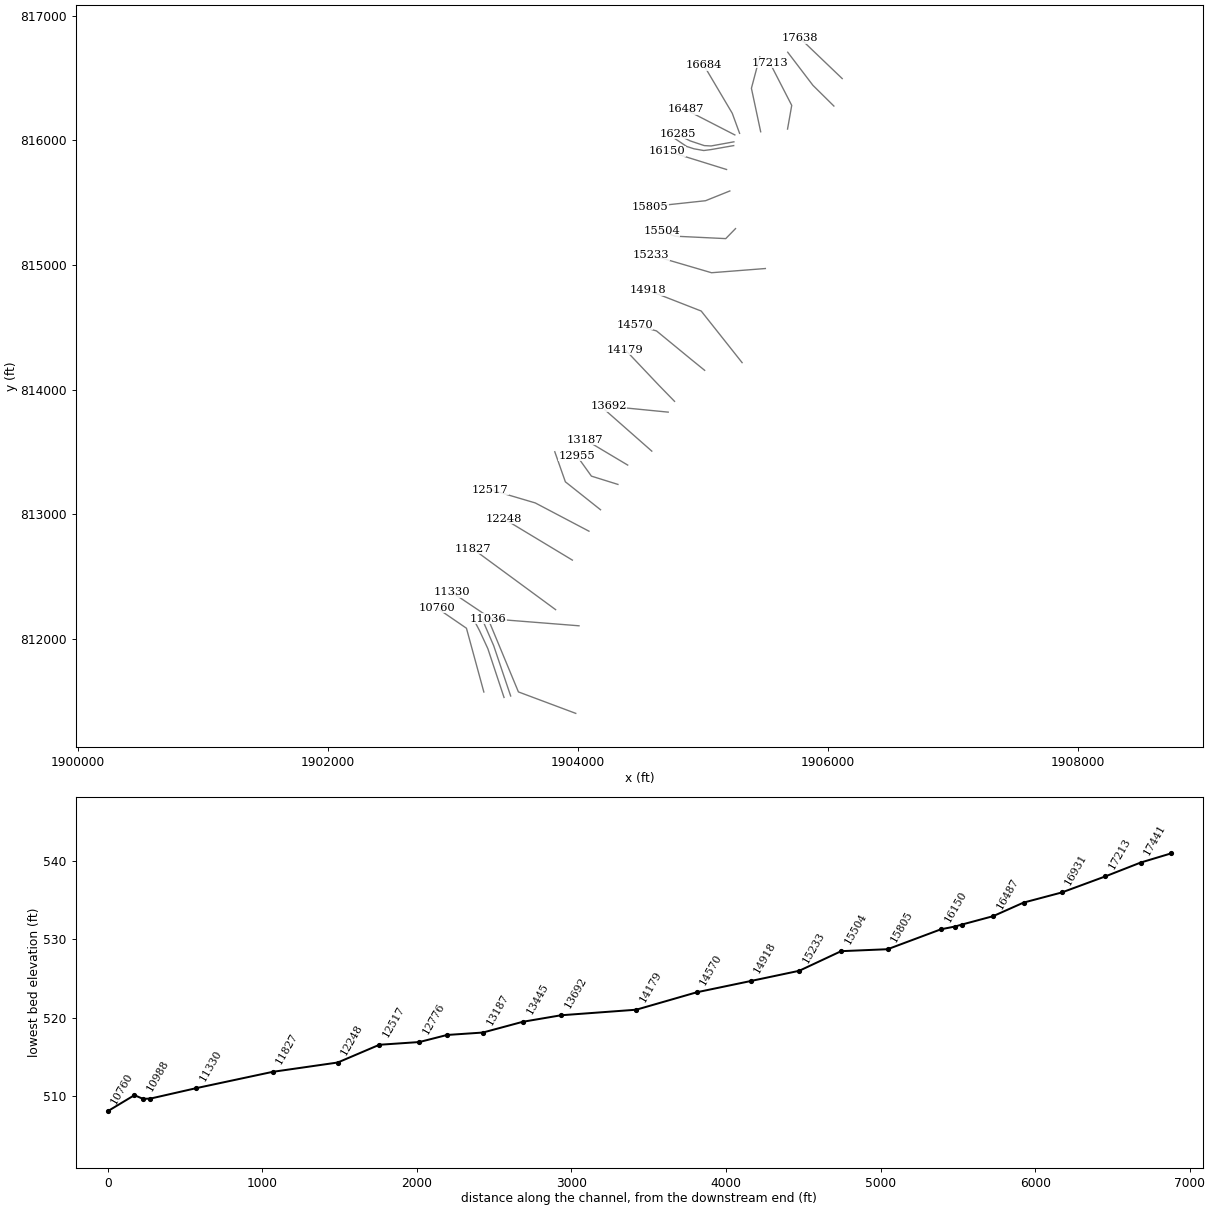
HEC-RAS study MeadowCreek.prj: MeadowCreek Detailed Study

--- MeadowCreek.g01 (geometry) --- (continued)

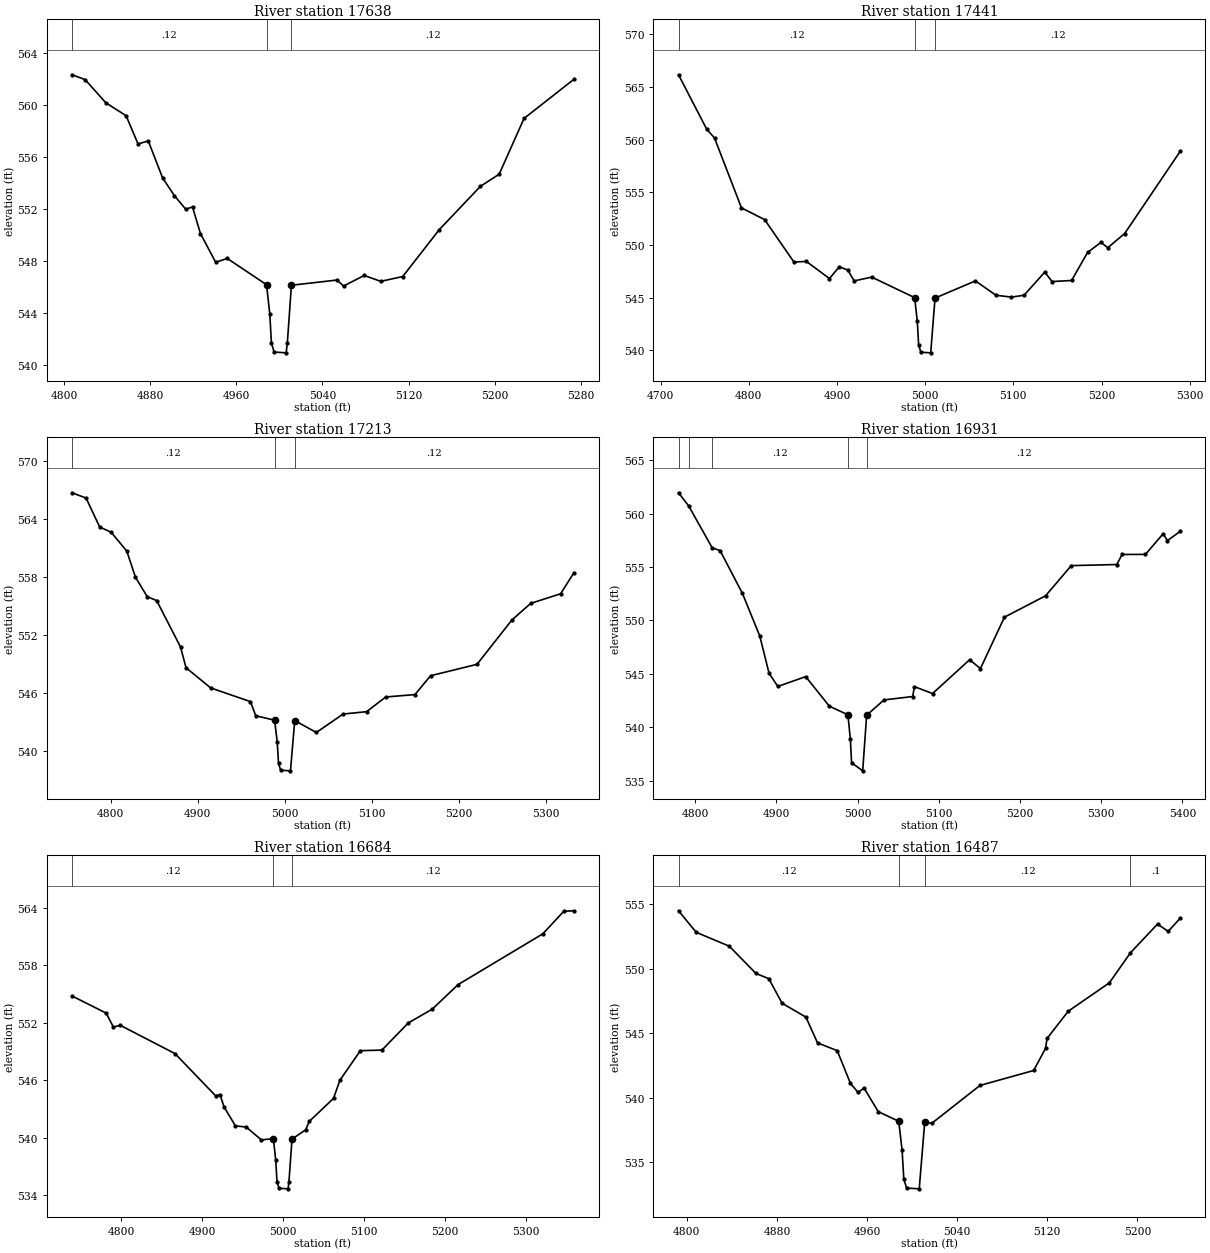
Type RM Length L Ch R = 1 ,17638   ,202,197,183
BEGIN DESCRIPTION:
Meadow Creek 58.0
END DESCRIPTION:
XS GIS Cut Line= 2
      1906115.71       816494.42      1905779.13       816817.01
#Sta/Elev= 30
  4807.4  562.31  4819.5  561.94  4838.7  560.16  4857.6  559.16  4868.7  556.99
  4878.2  557.22  4891.5  554.38  4902.5  553.01    4913  551.97  4919.3  552.14
  4926.7  550.09  4940.8  547.89  4951.6  548.18  4988.1  546.16  4991.1   543.9
  4992.6  541.68  4995.1  540.98  5006.3  540.92  5007.4  541.68  5011.2  546.12
  5053.6  546.52  5059.6  546.06  5078.8  546.87  5094.2  546.42  5114.6  546.79
  5148.6   550.4  5186.8  553.73  5204.2  554.66  5227.3  558.95  5273.6  561.96
#Mann= 3 ,-1 , 0
  4807.4     .12       0  4988.1     .05       0  5011.2     .12       0
Bank Sta=4988.1,5011.2
XS Rating Curve= 0 ,0
Exp/Cntr=0.3,0.1

Type RM Length L Ch R = 1 ,17441   ,228,228,210
BEGIN DESCRIPTION:
Meadow Creek 57.0
END DESCRIPTION:
XS GIS Cut Line= 3
      1906049.06       816274.29      1905881.45       816440.24
      1905679.81       816705.55
#Sta/Elev= 30
  4720.3  566.15  4752.4  560.96  4761.1  560.15  4791.7  553.51  4817.9   552.4
  4851.2  548.37  4865.3  548.43  4891.5   546.8  4902.5  547.92  4912.2  547.62
  4919.5  546.58  4939.4  546.94  4988.1  544.99  4991.1  542.73  4992.6  540.51
  4995.1  539.81  5006.3  539.75  5011.2  544.95    5057  546.58  5080.3  545.22
  5097.9  545.04  5112.2  545.22  5135.6  547.41    5144  546.52  5166.1  546.62
  5184.2  549.28  5199.4  550.24  5207.1  549.73  5226.3  551.08  5289.4   558.9
#Mann= 3 ,-1 , 0
  4720.3     .12       0  4988.1     .05       0  5011.2     .12       0
Bank Sta=4988.1,5011.2
XS Rating Curve= 0 ,0
Exp/Cntr=0.3,0.1

Type RM Length L Ch R = 1 ,17213   ,281,282,255
BEGIN DESCRIPTION:
Meadow Creek 56.0
END DESCRIPTION:
XS GIS Cut Line= 3
      1905678.35       816089.67      1905711.86       816279.39
      1905536.96       816620.52
#Sta/Elev= 30
  4755.6  566.76  4771.7  566.21  4787.3  563.22  4800.5  562.67  4818.4  560.73
  4828.4  558.02  4841.9  556.01  4852.7  555.61  4880.1   550.8  4886.4  548.66
  4914.7  546.57  4960.4  545.15  4966.4  543.69  4988.1  543.23  4991.1  540.97
  4992.6  538.75  4995.1  538.05  5006.3  537.99  5011.2  543.19    5036  541.96
  5066.8  543.87  5093.7  544.11  5115.6  545.63  5149.2  545.88  5167.1  547.83
  5220.4  549.01  5260.4  553.59  5282.1  555.32  5316.4  556.31  5331.6  558.48
#Mann= 3 ,-1 , 0
  4755.6     .12       0  4988.1     .05       0  5011.2     .12       0
Bank Sta=4988.1,5011.2
XS Rating Curve= 0 ,0
Exp/Cntr=0.3,0.1

Type RM Length L Ch R = 1 ,16931   ,205,247,235
BEGIN DESCRIPTION:
Meadow Creek 55.0
END DESCRIPTION:
XS GIS Cut Line= 3
      1905463.42       816067.97       1905389.3       816416.63
      1905456.19       816669.49
#Sta/Elev= 30
  4779.5  561.94    4792  560.71  4820.9   556.8  4830.7  556.53  4858.2  552.53
  4879.6  548.54    4891  545.06  4901.8  543.83  4936.1  544.75  4965.2  541.99
  4988.1  541.18  4991.1  538.92  4992.6   536.7  5006.3  535.94  5011.2  541.14
  5032.5  542.57  5067.9  542.89    5070  543.81  5092.4  543.17    5138  546.33
  5151.3   545.5  5180.9  550.31  5231.6  552.31  5263.2  555.13  5319.2  555.23
  5325.8  556.17  5354.6  556.18  5376.2   558.1  5381.7  557.47  5397.5  558.34
#Mann= 5 ,-1 , 0
  4779.5      .2       0    4792     .08       0  4820.9     .12       0
  4988.1     .05       0  5011.2     .12       0
Bank Sta=4988.1,5011.2
XS Rating Curve= 0 ,0
Exp/Cntr=0.3,0.1

Type RM Length L Ch R = 1 ,16684   ,176,197,211
BEGIN DESCRIPTION:
Meadow Creek 54.0
END DESCRIPTION:
XS GIS Cut Line= 3
      1905294.62       816055.64      1905236.03       816216.23
      1905007.58       816603.19
#Sta/Elev= 30
  4739.3  554.79  4781.5     553  4790.4  551.54  4798.9  551.73  4866.6  548.77
  4916.7  544.37  4922.2  544.48  4927.2   543.2  4941.2  541.23  4954.7   541.1
  4973.3  539.76  4988.1  539.89  4991.1  537.63  4992.6  535.41  4995.1  534.71
  5006.3  534.65  5007.4  535.41  5011.2  539.85    5028  540.81  5032.6   541.7
  5062.5   544.1  5070.4  545.99  5095.7  549.08  5122.3  549.14    5155  551.98
  5184.6  553.42  5216.5  555.98  5321.2  561.28  5347.2  563.64  5359.6  563.69
#Mann= 3 ,-1 , 0
  4739.3     .12       0  4988.1     .05       0  5011.2     .12       0
Bank Sta=4988.1,5011.2
XS Rating Curve= 0 ,0
Exp/Cntr=0.3,0.1

Type RM Length L Ch R = 1 ,16487   ,177,202,200
BEGIN DESCRIPTION:
Meadow Creek 53.0
END DESCRIPTION:
XS GIS Cut Line= 2
      1905256.63       816042.62      1904860.58       816246.61
#Sta/Elev= 30
  4792.6  554.49  4808.3  552.82  4837.7  551.74  4861.3  549.63  4872.8  549.22
  4884.5  547.32  4905.7  546.24    4916  544.24  4933.5  543.64  4945.2   541.1
    4952   540.4  4957.3  540.74  4969.9  538.91  4988.1  538.16  4991.1   535.9
  4992.6  533.68  4995.1  532.98  5006.3  532.92  5011.2  538.12  5017.4     538
  5060.2  540.94  5107.9   542.1  5118.4  543.81  5119.8  544.59  5138.6   546.7
  5175.1   548.9  5193.8  551.23  5217.9  553.46  5227.3  552.89  5238.1  553.92
#Mann= 4 ,-1 , 0
  4792.6     .12       0  4988.1     .05       0  5011.2     .12       0
  5193.8      .1       0
Bank Sta=4988.1,5011.2
XS Rating Curve= 0 ,0
Exp/Cntr=0.5,0.3

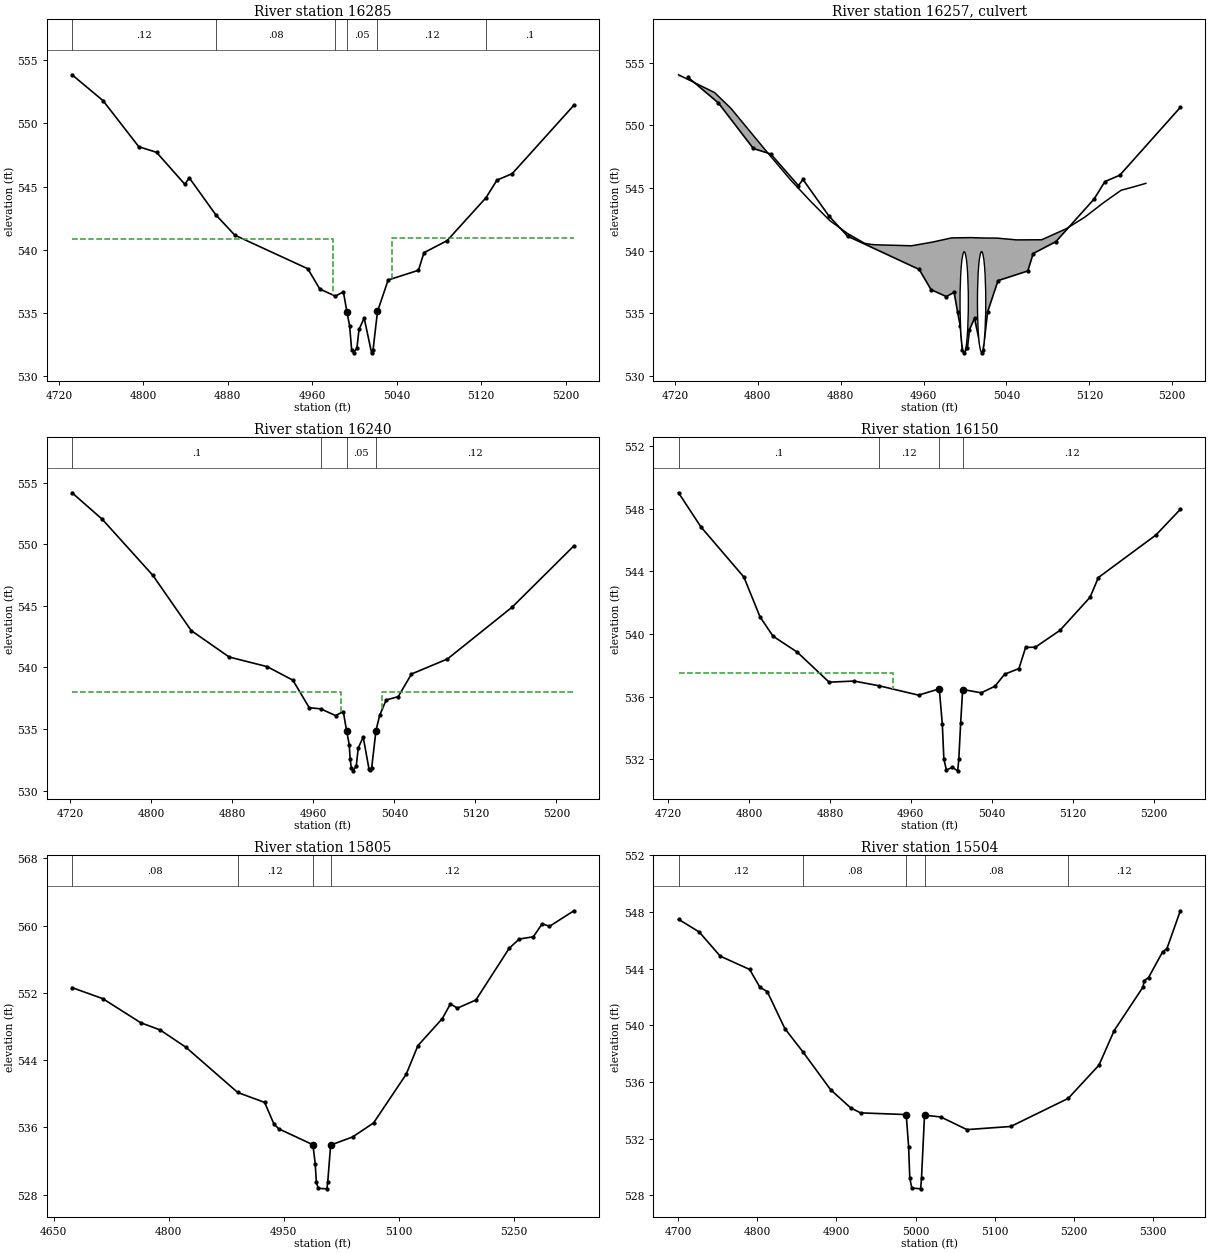
Type RM Length L Ch R = 1 ,16285   ,33,45,47
BEGIN DESCRIPTION:
Meadow Creek Preacher Davis Rd US
END DESCRIPTION:
XS GIS Cut Line= 6
      1905249.23       815987.43      1905066.86       815954.27
      1905011.97       815957.13      1904899.33       815994.87
      1904830.72       816029.17      1904799.28       816052.61
#Sta/Elev= 30
  4732.5  553.84  4761.9  551.79  4795.7  548.15  4812.5  547.71  4839.2  545.19
  4843.6  545.68  4868.6  542.77  4886.6  541.16  4955.8   538.5  4967.2  536.89
  4981.9  536.34  4989.5  536.67  4992.8  535.11  4995.4  533.98  4997.3  532.11
  4999.1  531.85  5002.3  532.22  5004.3   533.7  5009.2   534.6  5016.2  531.85
  5017.6  532.09  5021.8  535.12  5031.9  537.61  5060.6  538.38  5065.8  539.77
  5087.7  540.72  5124.6  544.12    5135  545.51  5149.4  546.02  5207.8  551.43
#Mann= 6 ,-1 , 0
  4732.5     .12       0  4868.6     .08       0  4981.9     .12       0
  4992.8     .05       0  5021.8     .12       0  5124.6      .1       0
#XS Ineff= 2 , 0
       0  4979.2  540.88    5036       0  540.96
Permanent Ineff=
       F       F
Bank Sta=4992.8,5021.8
XS Rating Curve= 0 ,0
Exp/Cntr=0.5,0.3

Type RM Length L Ch R = 2 ,16257   ,,,
BEGIN DESCRIPTION:
Preacher Davis Road (SR 2233) - MEC_03 - Survey Date: 10/22/10
END DESCRIPTION:
Bridge Culvert--1,0,-1,-1, 0
Deck Dist Width WeirC Skew NumUp NumDn MinLoCord MaxHiCord MaxSubmerge Is_Ogee
20,16,3,0, 26, 26, 540.39, , 0.95, 0, 1,1,,
  4723.5  4758.3  4774.1  4788.5  4808.2  4831.7  4851.6  4869.5  4886.6    4903
  4909.8  4917.7  4948.4  4968.3  4987.1  5005.8  5018.3    5031  5049.8    5074
  5097.7  5115.7  5133.9  5150.7    5165  5174.5
  554.03  552.61  551.35  549.91  547.94  545.64  543.88   542.4  541.37  540.59
  540.49  540.46  540.39  540.68  541.02  541.04  541.01     541  540.86  540.87
  541.75  542.68  543.84  544.82  545.14  545.37
  511.85  511.85  511.85  511.85  511.85  511.85  511.85  511.85  511.85  511.85
  511.85  511.85  511.85  511.85  511.85  511.85  511.85  511.85  511.85  511.85
  511.85  511.85  511.85  511.85  511.85  511.85
  4723.5  4758.3  4774.1  4788.5  4808.2  4831.7  4851.6  4869.5  4886.6    4903
  4909.8  4917.7  4948.4  4968.3  4987.1  5005.8  5018.3    5031  5049.8    5074
  5097.7  5115.7  5133.9  5150.7    5165  5174.5
  554.03  552.61  551.35  549.91  547.94  545.64  543.88   542.4  541.37  540.59
  540.49  540.46  540.39  540.68  541.02  541.04  541.01     541  540.86  540.87
  541.75  542.68  543.84  544.82  545.14  545.37
   511.6   511.6   511.6   511.6   511.6   511.6   511.6   511.6   511.6   511.6
   511.6   511.6   511.6   511.6   511.6   511.6   511.6   511.6   511.6   511.6
   511.6   511.6   511.6   511.6   511.6   511.6
BR Coef=-1 , 0 , 0 ,, 0 ,,,0.8,-1,,0,
WSPro=,,,, 1 ,,,, 0 ,,,, 0 ,,,,-1 ,-1 ,-1 , 0 , 0 , 0 , 0 , 0
Culvert=1,8,,24,0.024,0.9,1,2,3,531.91,4999.2,531.68,4999.2,Culvert #1  , 0 ,18
Culvert Bottom n=0.024
Culvert=1,8,,24,0.024,0.9,1,2,3,531.92,5016,531.72,5016,Culvert #2  , 0 ,17
Culvert Bottom n=0.024
BC Design=,, 0 ,, 0 ,,,,,,
BC HTab HWMax=553.84
BC Use User HTab Curves=0
BC User HTab FreeFlow(D)= 0

Type RM Length L Ch R = 1 ,16240   ,108,90,82
BEGIN DESCRIPTION:
Meadow Creek Preacher Davis Rd DS
END DESCRIPTION:
XS GIS Cut Line= 6
      1905247.49       815957.12      1905065.14       815925.11
      1905007.97       815917.68      1904930.21        815931.4
      1904871.32       815950.27      1904778.13       816012.59
#Sta/Elev= 30
  4721.6   554.2  4751.5  552.04  4801.4  547.49  4839.3     543  4876.8  540.85
  4914.3  540.07  4939.7  538.97  4955.9  536.73  4967.2  536.64  4981.9  536.09
  4989.5  536.42  4992.8  534.86  4995.4  533.73  4996.3  532.57  4997.4  531.86
  4999.1   531.6  5002.3  531.97  5004.3  533.45  5009.2  534.35  5014.9  531.76
  5016.2  531.63  5017.6  531.86  5021.8  534.87  5025.5  536.12  5031.9  537.36
  5043.8  537.63  5056.9  539.47  5092.4  540.69  5156.4  544.91  5217.3  549.88
#Mann= 4 ,-1 , 0
  4721.6      .1       0  4967.2     .12       0  4992.8     .05       0
  5021.8     .12       0
#XS Ineff= 2 , 0
       0  4987.2     538    5028       0     538
Permanent Ineff=
       F       F
Bank Sta=4992.8,5021.8
XS Rating Curve= 0 ,0
Exp/Cntr=0.5,0.3

Type RM Length L Ch R = 1 ,16150   ,315,345,360
BEGIN DESCRIPTION:
Meadow Creek 52.0 (A_MEC_03DSX)
END DESCRIPTION:
XS GIS Cut Line= 2
      1905190.38       815765.58      1904716.93       815913.11
#Sta/Elev= 30
  4730.4  549.03  4752.5  546.85    4795  543.64  4810.9   541.1  4823.8  539.86
  4847.7  538.84  4879.2  536.92  4903.9  536.99  4928.5  536.69  4967.6  536.09
  4988.1  536.49  4991.1  534.23  4992.6  532.01  4995.1  531.31  5001.1  531.47
  5006.3  531.25  5007.4  532.01  5009.2   534.3  5011.2  536.45  5029.6  536.24
  5043.1  536.66  5052.7  537.43  5066.8  537.79  5073.4  539.14  5083.1  539.16
  5107.3  540.23  5137.1  542.35  5145.3  543.61  5202.2  546.33  5226.3  547.97
#Mann= 4 ,-1 , 0
  4730.4      .1       0  4928.5     .12       0  4988.1     .05       0
  5011.2     .12       0
#XS Ineff= 2 , 0
       0  4942.2   537.5               0
Permanent Ineff=
       F       F
Bank Sta=4988.1,5011.2
XS Rating Curve= 0 ,0
Exp/Cntr=0.3,0.1

Type RM Length L Ch R = 1 ,15805   ,301,301,276
BEGIN DESCRIPTION:
Meadow Creek 51.0
END DESCRIPTION:
XS GIS Cut Line= 3
       1905216.5        815593.4      1905022.27       815515.27
      1904579.59       815467.53
#Sta/Elev= 30
  4673.9  552.62  4713.9  551.31  4763.4  548.45  4788.8  547.59  4822.3  545.54
    4890  540.16  4925.1  538.98  4937.4  536.38  4943.8  535.83  4988.1  533.95
  4991.1  531.69  4992.6  529.47  4995.1  528.77  5006.3  528.71  5007.4  529.47
  5011.2  533.91  5039.8  534.87  5067.2  536.54  5109.8  542.33  5125.1  545.73
  5156.9  548.94  5167.5  550.69  5176.6  550.18  5200.7  551.15  5244.2   557.3
  5257.2  558.39  5275.6  558.66  5287.2  560.21  5296.7   559.9  5328.5  561.75
#Mann= 4 ,-1 , 0
  4673.9     .08       0    4890     .12       0  4988.1     .05       0
  5011.2     .12       0
Bank Sta=4988.1,5011.2
XS Rating Curve= 0 ,0
Exp/Cntr=0.3,0.1

Type RM Length L Ch R = 1 ,15504   ,271,271,242
BEGIN DESCRIPTION:
meadow Creek 50.0
END DESCRIPTION:
XS GIS Cut Line= 4
      1905262.09       815291.77      1905183.94       815211.45
      1904779.21       815230.98      1904669.63       815270.04
#Sta/Elev= 30
  4700.6  547.48  4726.8  546.58  4753.2  544.88  4790.4  543.94  4803.3  542.69
  4812.7  542.37  4834.9  539.76  4857.6  538.13  4892.7  535.45    4918  534.17
  4930.5  533.82  4988.1   533.7  4991.1  531.44  4992.6  529.22  4995.1  528.52
  5006.3  528.46  5007.4  529.22  5011.2  533.66  5031.8  533.53  5064.7  532.64
  5120.1  532.86  5192.6  534.84  5231.5  537.19  5250.7  539.63  5287.2  542.71
  5288.3  543.14  5294.1  543.37    5312   545.2  5317.2   545.4  5334.2  548.08
#Mann= 5 ,-1 , 0
  4700.6     .12       0  4857.6     .08       0  4988.1     .05       0
  5011.2     .08       0  5192.6     .12       0
Bank Sta=4988.1,5011.2
XS Rating Curve= 0 ,0
Exp/Cntr=0.3,0.1

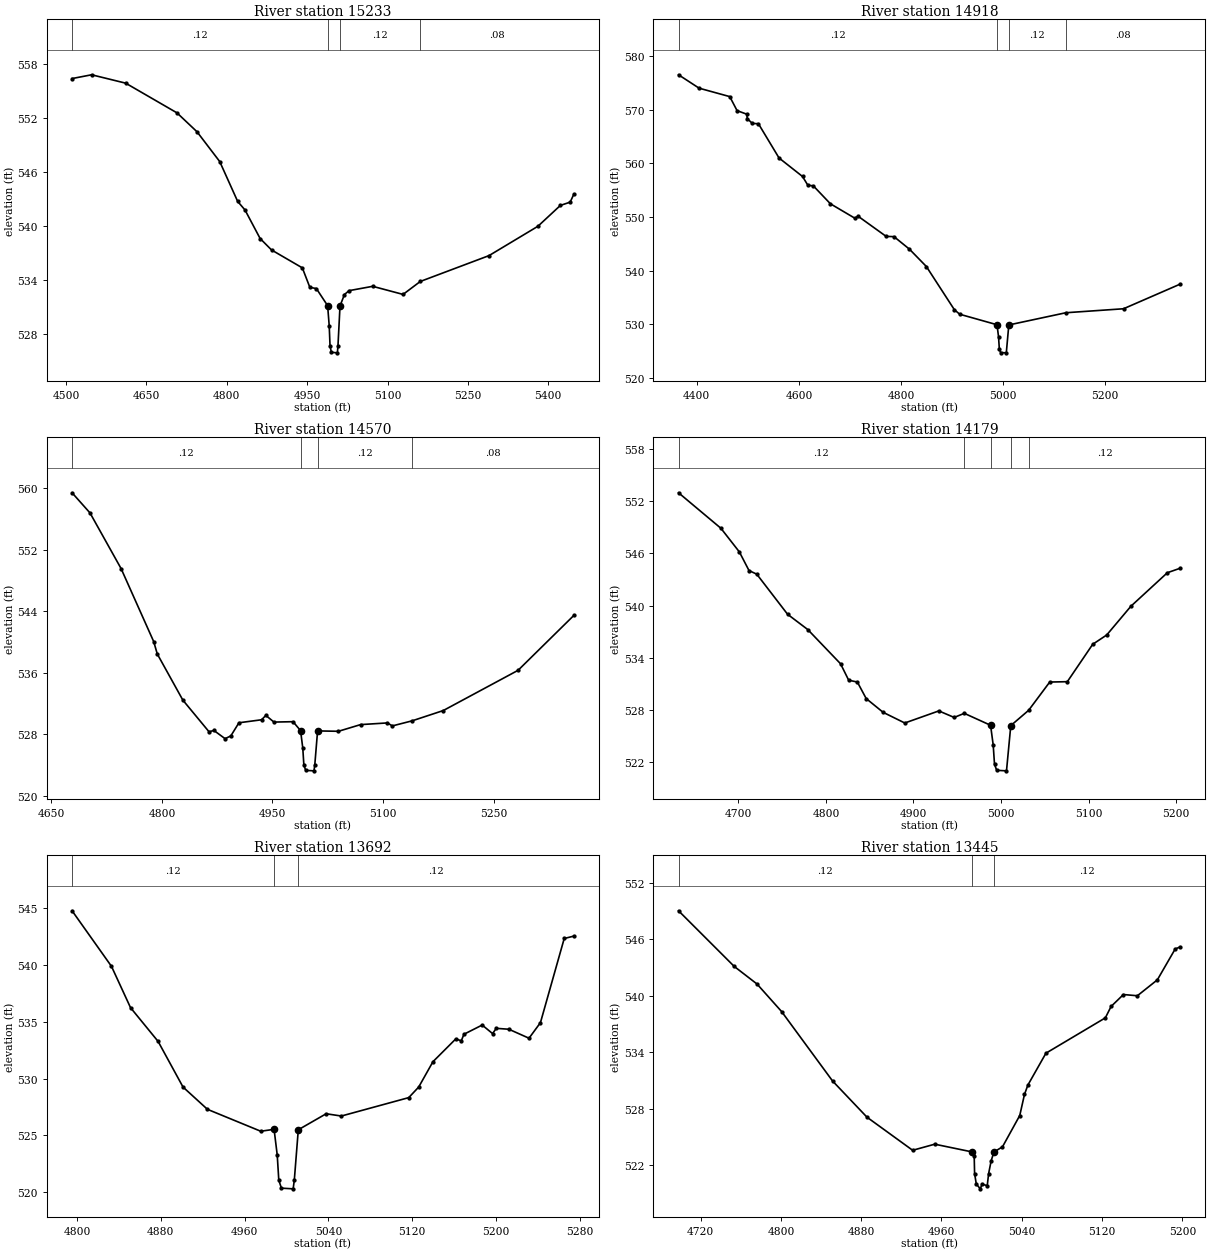
Type RM Length L Ch R = 1 ,15233   ,315,315,303
BEGIN DESCRIPTION:
Meadow Creek 49.0
END DESCRIPTION:
XS GIS Cut Line= 3
      1905500.88       814971.72      1905070.01       814938.01
      1904586.04       815080.17
#Sta/Elev= 30
  4511.1  556.43  4547.6  556.85  4611.1  555.92  4706.9  552.62  4744.3  550.52
  4786.7  547.21  4820.2  542.78  4833.9  541.83  4862.1  538.66  4883.4  537.39
  4940.9   535.4  4954.9  533.24  4967.1   533.1  4988.1   531.2  4991.1  528.94
  4992.6  526.72  4995.1  526.02  5006.3  525.96  5007.4  526.72  5011.2  531.16
  5019.5  532.44  5028.2  532.87  5072.2  533.35  5128.9  532.45  5161.1  533.89
  5289.3  536.76  5380.6  540.02  5422.6  542.34  5440.8   542.7  5447.7  543.59
#Mann= 4 ,-1 , 0
  4511.1     .12       0  4988.1     .05       0  5011.2     .12       0
  5161.1     .08       0
Bank Sta=4988.1,5011.2
XS Rating Curve= 0 ,0
Exp/Cntr=0.3,0.1

Type RM Length L Ch R = 1 ,14918   ,353,348,303
BEGIN DESCRIPTION:
Meadow Creek 48.0
END DESCRIPTION:
XS GIS Cut Line= 3
      1905314.84        814217.3      1904987.55       814630.94
      1904563.33       814796.94
#Sta/Elev= 30
  4364.2  576.51  4404.5  574.01  4464.5  572.44  4478.9  569.82  4497.9  569.16
  4498.9  568.33  4508.7  567.44  4520.7  567.38  4561.1  560.99  4607.1  557.54
  4617.7  555.88  4628.1  555.81  4661.7  552.45  4709.6  549.76  4715.8  550.14
  4770.9  546.37  4786.3  546.32  4816.6  543.98  4849.7  540.75  4904.5   532.7
    4915  531.85  4988.1  529.89  4991.1  527.63  4992.6  525.41  4995.1  524.71
  5006.3  524.65  5011.2  529.85  5123.1  532.13  5235.9  532.87  5347.2  537.48
#Mann= 4 ,-1 , 0
  4364.2     .12       0  4988.1     .05       0  5011.2     .12       0
  5123.1     .08       0
Bank Sta=4988.1,5011.2
XS Rating Curve= 0 ,0
Exp/Cntr=0.3,0.1

Type RM Length L Ch R = 1 ,14570   ,316,391,298
BEGIN DESCRIPTION:
Meadow Creek 47.0
END DESCRIPTION:
XS GIS Cut Line= 4
      1905015.17       814155.64      1904910.97       814240.29
      1904629.91       814471.54      1904454.16       814521.01
#Sta/Elev= 30
  4678.1  559.43  4702.4  556.81  4744.6  549.56  4788.9  540.04  4793.7  538.44
  4828.4  532.43  4863.9  528.31  4870.5  528.48  4885.7  527.41  4893.5  527.77
  4904.5  529.48  4935.2  529.87    4941  530.44    4952  529.57  4977.9  529.62
  4988.1  528.46  4991.1   526.2  4992.6  523.98  4995.1  523.28  5006.3  523.22
  5007.4  523.98  5011.2  528.42  5039.5  528.37  5069.5  529.24    5106  529.46
  5112.6  529.07  5139.4  529.73  5181.7  531.07  5283.2  536.31  5358.9  543.46
#Mann= 4 ,-1 , 0
  4678.1     .12       0  4988.1     .05       0  5011.2     .12       0
  5139.4     .08       0
Bank Sta=4988.1,5011.2
XS Rating Curve= 0 ,0
Exp/Cntr=0.3,0.1

Type RM Length L Ch R = 1 ,14179   ,260,487,426
BEGIN DESCRIPTION:
Meadow Creek 46.0
END DESCRIPTION:
XS GIS Cut Line= 3
      1904774.25       813906.98      1904649.11       814035.67
      1904378.57       814321.83
#Sta/Elev= 30
  4631.6  552.97    4680  548.89  4701.1  546.17  4712.1  544.03    4721  543.61
  4756.2     539  4779.3  537.24  4816.7  533.31    4826  531.42  4835.9  531.21
    4846  529.31  4865.3  527.73  4890.1   526.5    4929  527.89  4946.5  527.14
  4958.1  527.61  4988.1  526.24  4991.1  523.98  4992.6  521.76  4995.1  521.06
  5006.3     521  5011.2   526.2  5031.6  527.96  5055.7  531.21  5075.8  531.25
  5104.8  535.55  5120.8  536.62  5148.4  539.92  5190.1  543.78  5204.9   544.3
#Mann= 5 ,-1 , 0
  4631.6     .12       0  4958.1     .11       0  4988.1     .05       0
  5011.2     .11       0  5031.6     .12       0
Bank Sta=4988.1,5011.2
XS Rating Curve= 0 ,0
Exp/Cntr=0.3,0.1

Type RM Length L Ch R = 1 ,13692   ,237,247,168
BEGIN DESCRIPTION:
Meadow Creek 45.0
END DESCRIPTION:
XS GIS Cut Line= 2
      1904723.65        813820.5      1904247.05       813867.38
#Sta/Elev= 30
  4795.3  544.77  4832.9  539.88  4851.1  536.24  4877.4  533.27  4901.2  529.25
  4924.5  527.29  4975.4  525.36  4988.1  525.53  4991.1  523.27  4992.6  521.05
  4995.1  520.35  5006.3  520.29  5007.4  521.05  5011.2  525.49  5037.8   526.9
  5052.3   526.7  5116.6  528.32  5126.1  529.25  5139.7  531.48  5161.4  533.48
  5166.8  533.33  5169.3   533.9  5186.7  534.71  5196.6  533.96  5200.2  534.42
  5212.2  534.34  5231.4  533.55  5242.3  534.92    5265  542.33  5274.2  542.54
#Mann= 3 ,-1 , 0
  4795.3     .12       0  4988.1     .05       0  5011.2     .12       0
Bank Sta=4988.1,5011.2
XS Rating Curve= 0 ,0
Exp/Cntr=0.3,0.1

Type RM Length L Ch R = 1 ,13445   ,246,258,257
BEGIN DESCRIPTION:
Meadow Creek 44.0
END DESCRIPTION:
XS GIS Cut Line= 2
      1904592.17       813507.98      1904217.17       813838.71
#Sta/Elev= 30
    4698  549.04  4753.5  543.12  4776.2  541.25  4800.7  538.32  4851.5  530.93
  4885.8  527.08  4931.3  523.56  4953.3  524.21  4990.4  523.39  4992.6  522.99
    4993  521.09  4994.7  519.97  4998.7  519.46  5000.4  519.96  5005.6   519.8
    5007  521.09  5009.5  522.44  5012.3  523.38  5020.8  523.93    5038  527.26
  5042.7   529.5  5046.1   530.5  5064.1  533.89  5123.3  537.65    5129  538.86
  5141.3  540.13  5155.2     540  5175.1  541.69  5192.9  544.98    5198   545.2
#Mann= 3 ,-1 , 0
    4698     .12       0  4990.4     .06       0  5012.3     .12       0
Bank Sta=4990.4,5012.3
XS Rating Curve= 0 ,0
Exp/Cntr=0.3,0.1

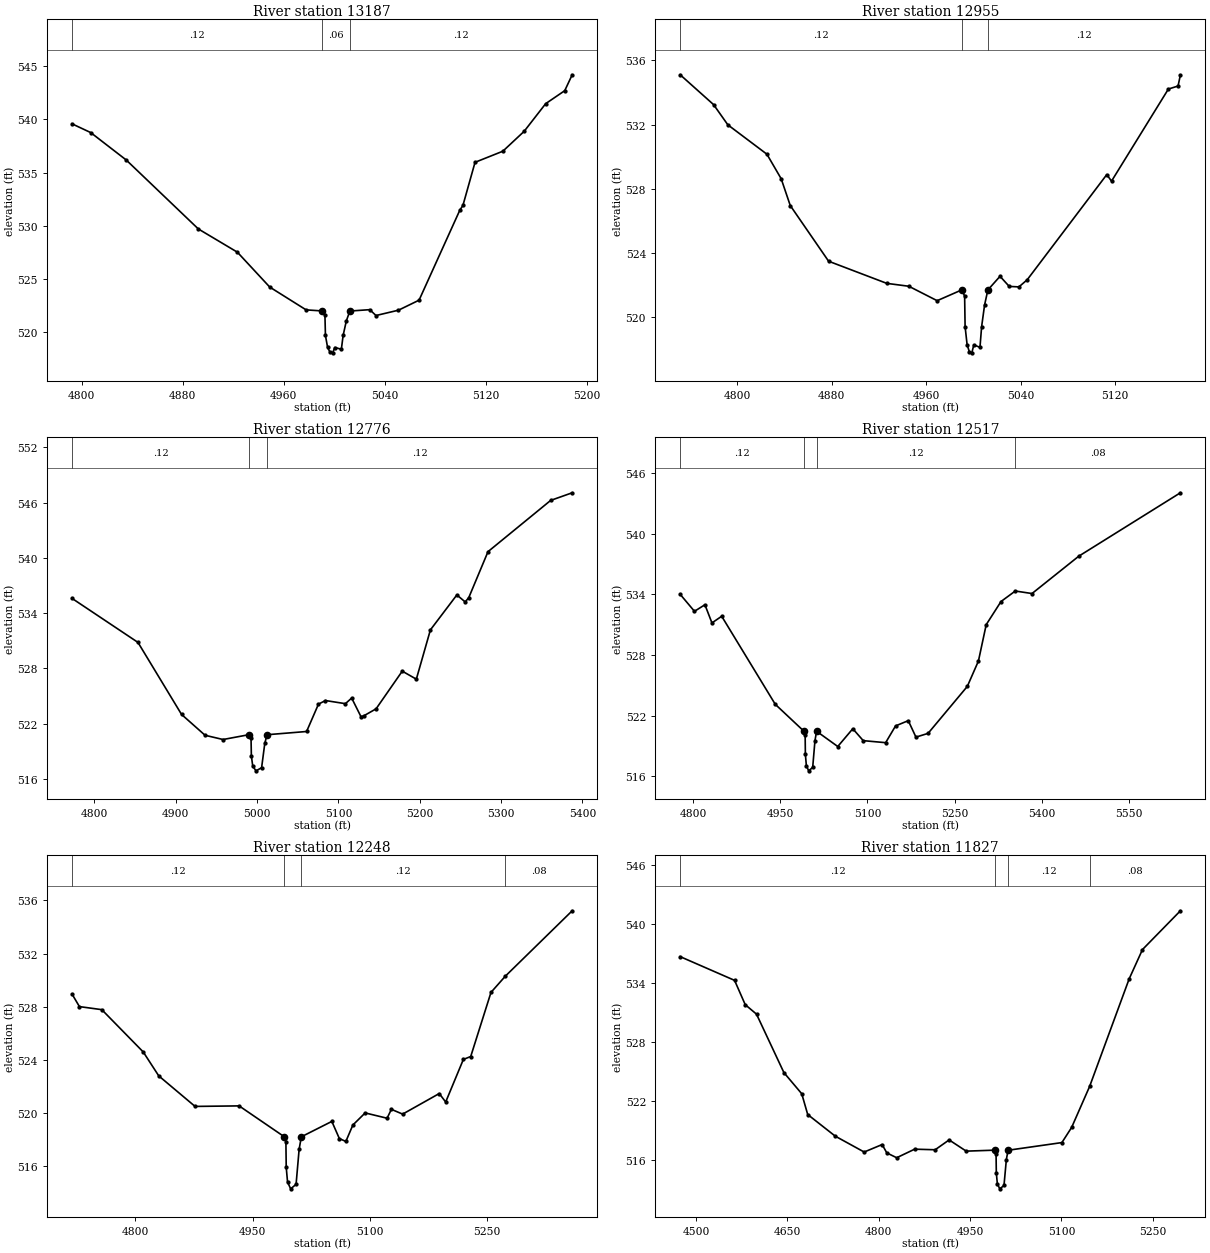
Type RM Length L Ch R = 1 ,13187   ,215,232,204
BEGIN DESCRIPTION:
Meadow Creek 43.0
END DESCRIPTION:
XS GIS Cut Line= 2
      1904399.44       813396.02      1904059.62       813599.13
#Sta/Elev= 30
  4792.4  539.57  4807.2  538.75  4835.3  536.18  4892.4  529.71  4923.3  527.53
  4948.9  524.26  4977.7  522.12  4990.4  522.02  4992.6  521.62    4993  519.72
  4994.7   518.6  4996.7  518.13  4998.7  518.09  5000.4  518.59  5005.6  518.43
    5007  519.72  5009.5  521.07  5012.3  522.01  5028.1  522.14    5033  521.59
  5050.8  522.09  5067.1  523.03  5099.4  531.48  5101.8  531.91  5111.4  535.96
  5133.4     537  5150.3  538.87  5167.3  541.46  5182.4  542.68  5188.3  544.17
#Mann= 3 ,-1 , 0
  4792.4     .12       0  4990.4     .06       0  5012.3     .12       0
Bank Sta=4990.4,5012.3
XS Rating Curve= 0 ,0
Exp/Cntr=0.3,0.1

Type RM Length L Ch R = 1 ,12955   ,181,179,180
BEGIN DESCRIPTION:
Meadow Creek 42.0
END DESCRIPTION:
XS GIS Cut Line= 3
       1904321.3       813241.08      1904109.07       813307.48
      1903991.88       813471.56
#Sta/Elev= 30
  4751.5  535.11  4779.8  533.25  4791.9  531.99    4825  530.16  4837.1  528.63
  4844.8  526.96  4877.3  523.49  4926.6  522.11  4945.3  521.93  4969.3  521.03
  4990.4  521.71  4992.6  521.31    4993  519.41  4994.7  518.29  4996.7  517.82
  4998.7  517.78  5000.4  518.28  5005.6  518.12    5007  519.41  5009.5  520.76
  5012.3   521.7  5022.6  522.55  5030.4  521.92  5038.6  521.89  5045.6  522.33
  5113.1  528.89  5117.1  528.48  5165.3  534.22  5173.5  534.41  5175.5   535.1
#Mann= 3 ,-1 , 0
  4751.5     .12       0  4990.4     .06       0  5012.3     .12       0
Bank Sta=4990.4,5012.3
XS Rating Curve= 0 ,0
Exp/Cntr=0.3,0.1

Type RM Length L Ch R = 1 ,12776   ,230,259,250
BEGIN DESCRIPTION:
Meadow Creek 41.0
END DESCRIPTION:
XS GIS Cut Line= 3
      1904182.02       813037.93      1903900.74       813261.91
       1903816.1       813502.81
#Sta/Elev= 30
  4772.5   535.6  4853.6  530.82  4907.2     523  4936.1  520.74  4958.2  520.28
  4990.4  520.81  4992.6  520.41    4993  518.51  4994.7  517.39  4998.7  516.88
  5005.6  517.22  5009.5  519.86  5012.3   520.8  5060.9  521.15  5075.5  524.12
  5084.1  524.51  5108.6  524.17  5116.3  524.78  5127.8  522.75  5131.2  522.85
  5146.3  523.61  5178.5   527.7  5195.8  526.83  5213.1  532.18  5245.6  535.97
  5255.9  535.21  5260.3  535.69  5283.9  540.67  5360.9  546.23  5387.4  547.06
#Mann= 3 ,-1 , 0
  4772.5     .12       0  4990.4     .06       0  5012.3     .12       0
Bank Sta=4990.4,5012.3
XS Rating Curve= 0 ,0
Exp/Cntr=0.3,0.1

Type RM Length L Ch R = 1 ,12517   ,256,269,254
BEGIN DESCRIPTION:
Meadow Creek 40.0
END DESCRIPTION:
XS GIS Cut Line= 3
      1904089.57       812866.06      1903659.86       813092.64
      1903299.22       813199.39
#Sta/Elev= 30
  4777.3  534.01  4801.9  532.33  4819.9  532.98    4832  531.18  4848.8  531.84
  4941.1  523.12  4990.4  520.46  4992.6  520.06    4993  518.16  4994.7  517.04
  4998.7  516.53  5005.6  516.87  5009.5  519.51  5012.3  520.45  5048.8  518.94
  5074.7   520.7  5092.7  519.52  5131.3  519.32  5148.4  520.98  5170.3   521.5
  5183.5  519.87  5204.4  520.24    5272  524.89  5291.2  527.41  5304.6  531.01
  5330.1   533.3  5354.7  534.34  5383.5  534.09  5464.1  537.79  5639.2  544.07
#Mann= 4 ,-1 , 0
  4777.3     .12       0  4990.4     .06       0  5012.3     .12       0
  5354.7     .08       0
Bank Sta=4990.4,5012.3
XS Rating Curve= 0 ,0
Exp/Cntr=0.3,0.1

Type RM Length L Ch R = 1 ,12248   ,389,421,371
BEGIN DESCRIPTION:
meadow Creek 39.0
END DESCRIPTION:
XS GIS Cut Line= 2
      1903956.72       812634.31      1903409.56       812964.94
#Sta/Elev= 30
  4719.2  528.95  4728.7     528  4757.3  527.77  4810.3  524.58  4830.1  522.78
  4876.5  520.48  4932.8  520.52  4990.4   518.2  4992.6   517.8    4993   515.9
  4994.7  514.78  4998.7  514.27  5005.6  514.61  5009.5  517.25  5012.3  518.19
  5051.3  519.35  5060.9  518.06  5069.2  517.84  5078.2  519.08  5093.9  519.99
  5121.9  519.59  5127.4  520.26  5141.8   519.9  5188.6  521.45  5196.8  520.81
  5219.4  524.02  5228.8  524.24  5254.7  529.07    5273  530.29  5358.5  535.22
#Mann= 4 ,-1 , 0
  4719.2     .12       0  4990.4     .06       0  5012.3     .12       0
    5273     .08       0
Bank Sta=4990.4,5012.3
XS Rating Curve= 0 ,0
Exp/Cntr=0.3,0.1

Type RM Length L Ch R = 1 ,11827   ,273,497,389
BEGIN DESCRIPTION:
Meadow Creek 38.0
END DESCRIPTION:
XS GIS Cut Line= 2
      1903822.65       812237.14      1903161.18       812724.13
#Sta/Elev= 30
  4473.9  536.67  4563.2  534.26  4580.7  531.79  4599.2  530.83  4644.2  524.89
  4673.5  522.74  4683.3  520.63  4728.6  518.43    4776  516.82  4805.5  517.58
  4813.2  516.73  4829.4  516.24  4858.9  517.11  4892.6  517.05  4915.5  518.05
  4943.6  516.91  4990.4  517.01  4992.6  516.61    4993  514.71  4994.7  513.59
  4998.7  513.08  5005.6  513.42  5009.5  516.06  5012.3     517  5100.7  517.78
  5116.7  519.32  5146.2  523.48  5211.2  534.42    5233  537.39  5295.3  541.33
#Mann= 4 ,-1 , 0
  4473.9     .12       0  4990.4     .06       0  5012.3     .12       0
  5146.2     .08       0
Bank Sta=4990.4,5012.3
XS Rating Curve= 0 ,0
Exp/Cntr=0.3,0.1

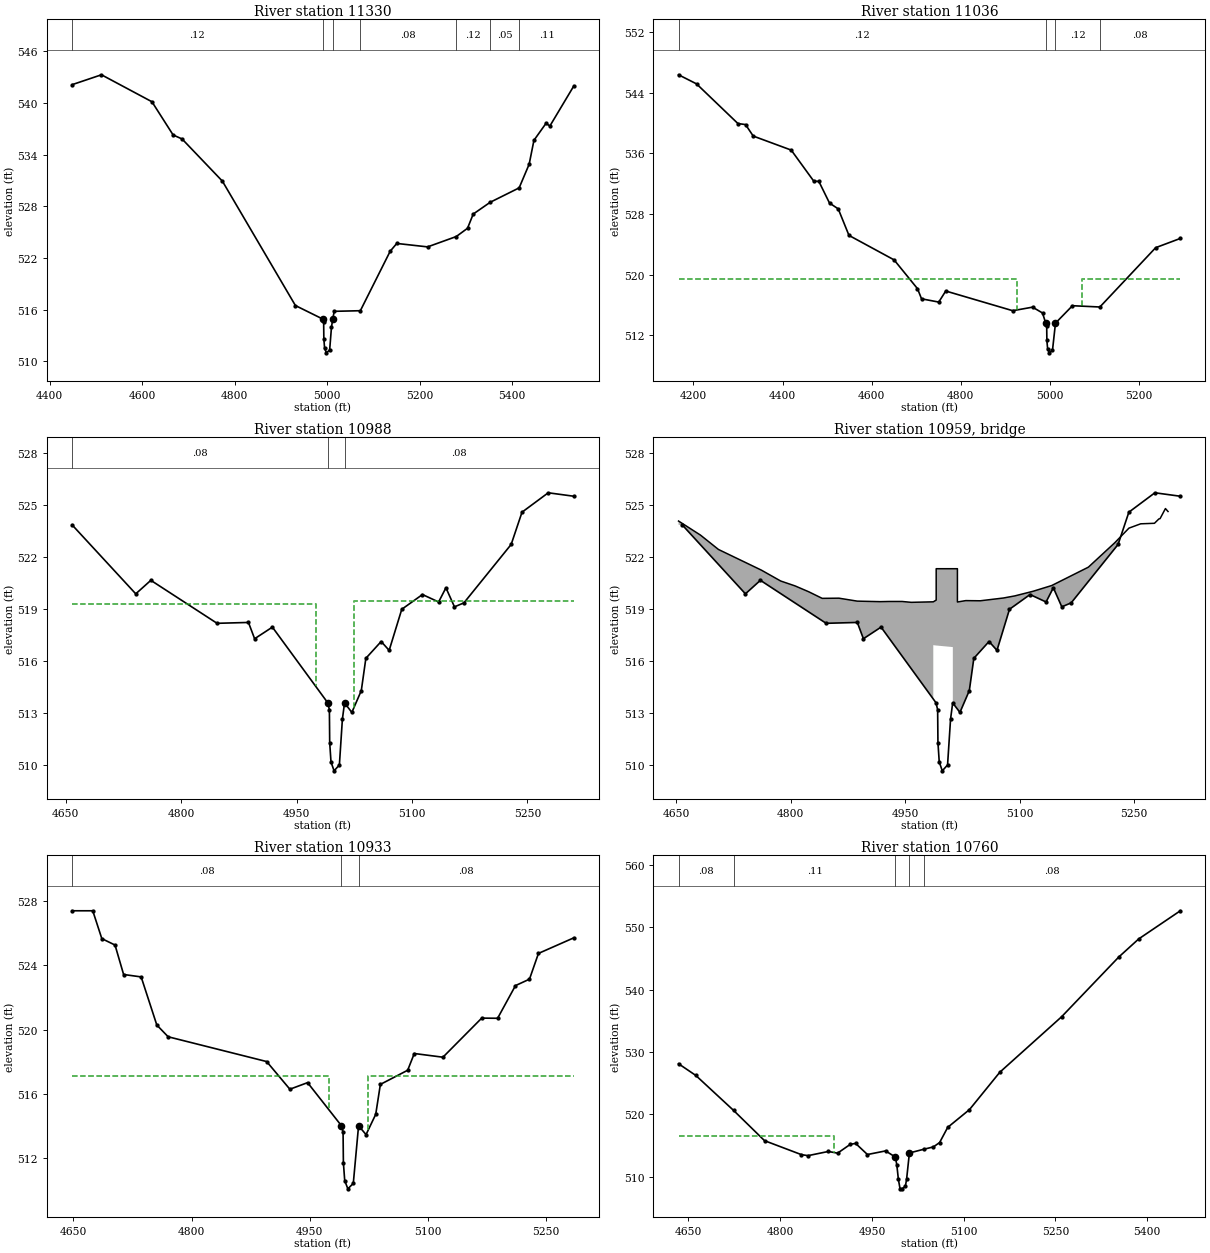
Type RM Length L Ch R = 1 ,11330   ,317,294,217
BEGIN DESCRIPTION:
Meadow Creek 37.0
END DESCRIPTION:
XS GIS Cut Line= 3
      1904009.98       812107.71      1903309.59       812163.33
      1902991.55       812377.09
#Sta/Elev= 30
  4448.2  542.12  4511.8  543.27    4621  540.14  4666.9  536.28  4686.2  535.82
  4773.5  530.92  4931.5  516.48  4990.4  514.92  4992.6  514.52    4993  512.62
  4994.7   511.5  4998.7  510.99  5005.6  511.33  5009.5  513.97  5012.3  514.91
  5015.4  515.81    5072  515.88  5136.5  522.78  5150.8  523.69  5217.5  523.29
  5279.5  524.49  5303.9  525.45  5316.2   527.1    5353  528.47  5415.6  530.14
  5437.3  532.89  5447.6  535.66  5473.6  537.62  5482.2  537.33    5534  541.98
#Mann= 7 ,-1 , 0
  4448.2     .12       0  4990.4     .05       0  5012.3     .12       0
    5072     .08       0  5279.5     .12       0    5353     .05       0
  5415.6     .11       0
Bank Sta=4990.4,5012.3
XS Rating Curve= 0 ,0
Exp/Cntr=0.3,0.1

Type RM Length L Ch R = 1 ,11036   ,49,48,48
BEGIN DESCRIPTION:
Meadow Creek 36.5
END DESCRIPTION:
XS GIS Cut Line= 3
      1903983.89       811405.63      1903525.08       811577.68
      1903281.78       812165.08
#Sta/Elev= 30
  4166.6  546.37    4207  545.17  4299.9  539.93  4316.9   539.8  4334.2  538.28
  4419.4  536.43    4470  532.33  4481.4   532.3  4505.3  529.44  4524.9  528.67
    4549  525.17  4650.2  521.94  4702.7  518.14  4711.8   516.8  4750.4  516.37
  4766.1  517.83  4916.4  515.23  4960.9   515.7  4983.2  514.93  4990.4   513.6
  4992.6   513.2    4993   511.3  4994.7  510.18  4998.7  509.67  5005.6  510.01
  5012.3  513.59  5050.4  515.89  5111.9  515.72  5237.1  523.55  5292.4  524.77
#Mann= 4 ,-1 , 0
  4166.6     .12       0  4990.4     .05       0  5012.3     .12       0
  5111.9     .08       0
#XS Ineff= 2 , 0
       0  4926.9   519.4  5072.5       0   519.4
Permanent Ineff=
       F       F
Bank Sta=4990.4,5012.3
XS Rating Curve= 0 ,0
Exp/Cntr=0.5,0.3

Type RM Length L Ch R = 1 ,10988   ,52,55,59
BEGIN DESCRIPTION:
Meadow Creek Swepsonville-Saxapahaw Rd US
END DESCRIPTION:
XS GIS Cut Line= 3
      1903463.06       811544.99      1903327.29       811947.98
      1903237.32       812156.45
#Sta/Elev= 30
  4658.1  523.83  4740.9  519.85  4760.5  520.63  4846.6  518.15  4887.4   518.2
  4895.4  517.26  4918.5  517.93  4990.4  513.57  4992.6  513.17    4993  511.27
  4994.7  510.15  4998.7  509.64  5005.6  509.98  5009.5  512.62  5012.3  513.56
  5021.8  513.01  5034.1  514.27    5040  516.13  5059.9   517.1  5070.3  516.59
  5086.7  518.96  5113.6  519.81  5134.6  519.38  5144.1   520.2  5155.2   519.1
  5167.5  519.33  5228.9   522.7    5243  524.56  5277.1  525.68  5310.4  525.48
#Mann= 3 ,-1 , 0
  4658.1     .08       0  4990.4    .055       0  5012.3     .08       0
#XS Ineff= 2 , 0
       0  4974.9  519.25  5024.5       0  519.45
Permanent Ineff=
       F       F
Bank Sta=4990.4,5012.3
XS Rating Curve= 0 ,0
Exp/Cntr=0.5,0.3

Type RM Length L Ch R = 3 ,10959   ,,,
BEGIN DESCRIPTION:
Swepsonville-Saxapahaw Road (SR 2158) - MEC_02 - Survey Date: 10/14/10
Drawdown could not be resolved using generally accepted modeling practices.
END DESCRIPTION:
Bridge Culvert--1,0,-1,-1, 0
Deck Dist Width WeirC Skew NumUp NumDn MinLoCord MaxHiCord MaxSubmerge Is_Ogee
12,28,3,0, 37, 37, 519.36, , 0.95, 0, 1,1,,
  4653.3    4682  4705.6  4761.7  4787.1  4805.8  4823.8  4841.4  4863.4  4887.3
  4917.1  4929.2  4946.1  4958.1  4986.9  4986.9  4990.7  4990.7  5012.5  5012.5
  5018.5  5018.5  5029.4  5048.4  5078.7  5093.5  5117.7    5142    5190  5224.6
  5243.1  5258.5  5276.5  5282.3  5283.9  5290.9  5294.3
  524.05  523.24  522.41  521.22  520.59  520.31  519.97  519.59   519.6  519.43
   519.4  519.41  519.41  519.36  519.39  519.39  519.49   521.3   521.3   521.3
   521.3  519.38  519.46  519.45  519.61  519.73     520  520.33  521.39   522.8
  523.64  523.89  523.92  524.17  524.19  524.77   524.6
  489.64  489.64  489.64  489.64  489.64  489.64  489.64  489.64  489.64  489.64
  489.64  489.64  489.64  489.64  489.64  516.89  516.87  516.87  516.78  489.64
  489.64  489.64  489.64  489.64  489.64  489.64  489.64  489.64  489.64  489.64
  489.64  489.64  489.64  489.64  489.64  489.64  489.64
  4653.3    4682  4705.6  4761.7  4787.1  4805.8  4823.8  4841.4  4863.4  4887.3
  4917.1  4929.2  4946.1  4958.1  4986.9  4986.9  4990.7  4990.7  5012.5  5012.5
  5018.5  5018.5  5029.4  5048.4  5078.7  5093.5  5117.7    5142    5190  5224.6
  5243.1  5258.5  5276.5  5282.3  5283.9  5290.9  5294.3
  524.05  523.24  522.41  521.22  520.59  520.31  519.97  519.59   519.6  519.43
   519.4  519.41  519.41  519.36  519.39  519.39  519.49   521.3   521.3   521.3
   521.3  519.38  519.46  519.45  519.61  519.73     520  520.33  521.39   522.8
  523.64  523.89  523.92  524.17  524.19  524.77   524.6
  489.64  489.64  489.64  489.64  489.64  489.64  489.64  489.64  489.64  489.64
  489.64  489.64  489.64  489.64  489.64  516.89  516.87  516.87  516.78  489.64
  489.64  489.64  489.64  489.64  489.64  489.64  489.64  489.64  489.64  489.64
  489.64  489.64  489.64  489.64  489.64  489.64  489.64
BR Coef= 1 , 1 , 0 ,, 0 ,,,0.8,0,1.2,0,
WSPro=,,,, 1 ,,,, 0 ,,,, 0 ,,,,-1 ,-1 ,-1 , 0 , 0 , 0 , 0 , 0
BC Design=,, 0 ,, 0 ,,,,,,
BC HTab HWMax=525.73
BC Use User HTab Curves=0
BC User HTab FreeFlow(D)= 0

Type RM Length L Ch R = 1 ,10933   ,130,173,144
BEGIN DESCRIPTION:
Meadow Creek Swepsonville-Saxapahaw Rd DS
END DESCRIPTION:
XS GIS Cut Line= 4
      1903409.95       811533.22      1903280.48       811924.57
      1903214.65        812067.2      1903183.18       812127.94
#Sta/Elev= 30
  4648.2  527.39  4674.5  527.39    4686  525.66  4702.8  525.26  4713.7  523.43
    4736  523.28  4755.9  520.29  4770.3  519.56  4895.5  518.02    4925   516.3
  4947.5  516.71  4990.4  514.04  4992.6  513.64    4993  511.74  4994.7  510.62
  4998.7  510.11  5005.6  510.45  5012.3  514.03  5021.8  513.48  5034.1  514.74
    5040   516.6  5074.7  517.48  5083.1  518.52  5119.5  518.29  5168.8  520.72
    5189  520.71  5211.7  522.74  5229.5  523.14  5240.9  524.74  5285.9  525.71
#Mann= 3 ,-1 , 0
  4648.2     .08       0  4990.4    .055       0  5012.3     .08       0
#XS Ineff= 2 , 0
       0  4974.9   517.1  5024.5       0   517.1
Permanent Ineff=
       F       F
Bank Sta=4990.4,5012.3
XS Rating Curve= 0 ,0
Exp/Cntr=0.5,0.3

Type RM Length L Ch R = 1 ,10760   ,275,427,395
BEGIN DESCRIPTION:
Meadow Creek 36.0 (A_MEC_02DSX)
END DESCRIPTION:
XS GIS Cut Line= 3
      1903248.41       811576.97      1903109.22       812088.18
      1902869.79       812252.66
#Sta/Elev= 30
  4633.9  528.11  4662.1  526.24    4724  520.62  4774.5  515.78  4834.8  513.54
  4845.6  513.38  4878.8  514.05  4893.9  513.78  4914.8   515.2  4923.4  515.34
  4942.7  513.56  4972.4  514.14  4988.4  513.15  4990.8  511.85  4993.3  509.57
    4996  508.09  4999.3  508.06  5004.7  508.47  5006.7  509.57  5011.3  513.81
  5034.6   514.4  5050.5  514.78  5060.7  515.48  5073.9  517.91  5109.5  520.76
  5159.1  526.75  5260.1  535.64  5353.6  545.22  5386.2  548.12  5454.2  552.63
#Mann= 5 ,-1 , 0
  4633.9     .08       0    4724     .11       0  4988.4     .06       0
  5011.3     .11       0  5034.6     .08       0
#XS Ineff= 2 , 0
       0  4888.4   516.5               0
Permanent Ineff=
       F       F
Bank Sta=4988.4,5011.3
XS Rating Curve= 0 ,0
Exp/Cntr=0.3,0.1