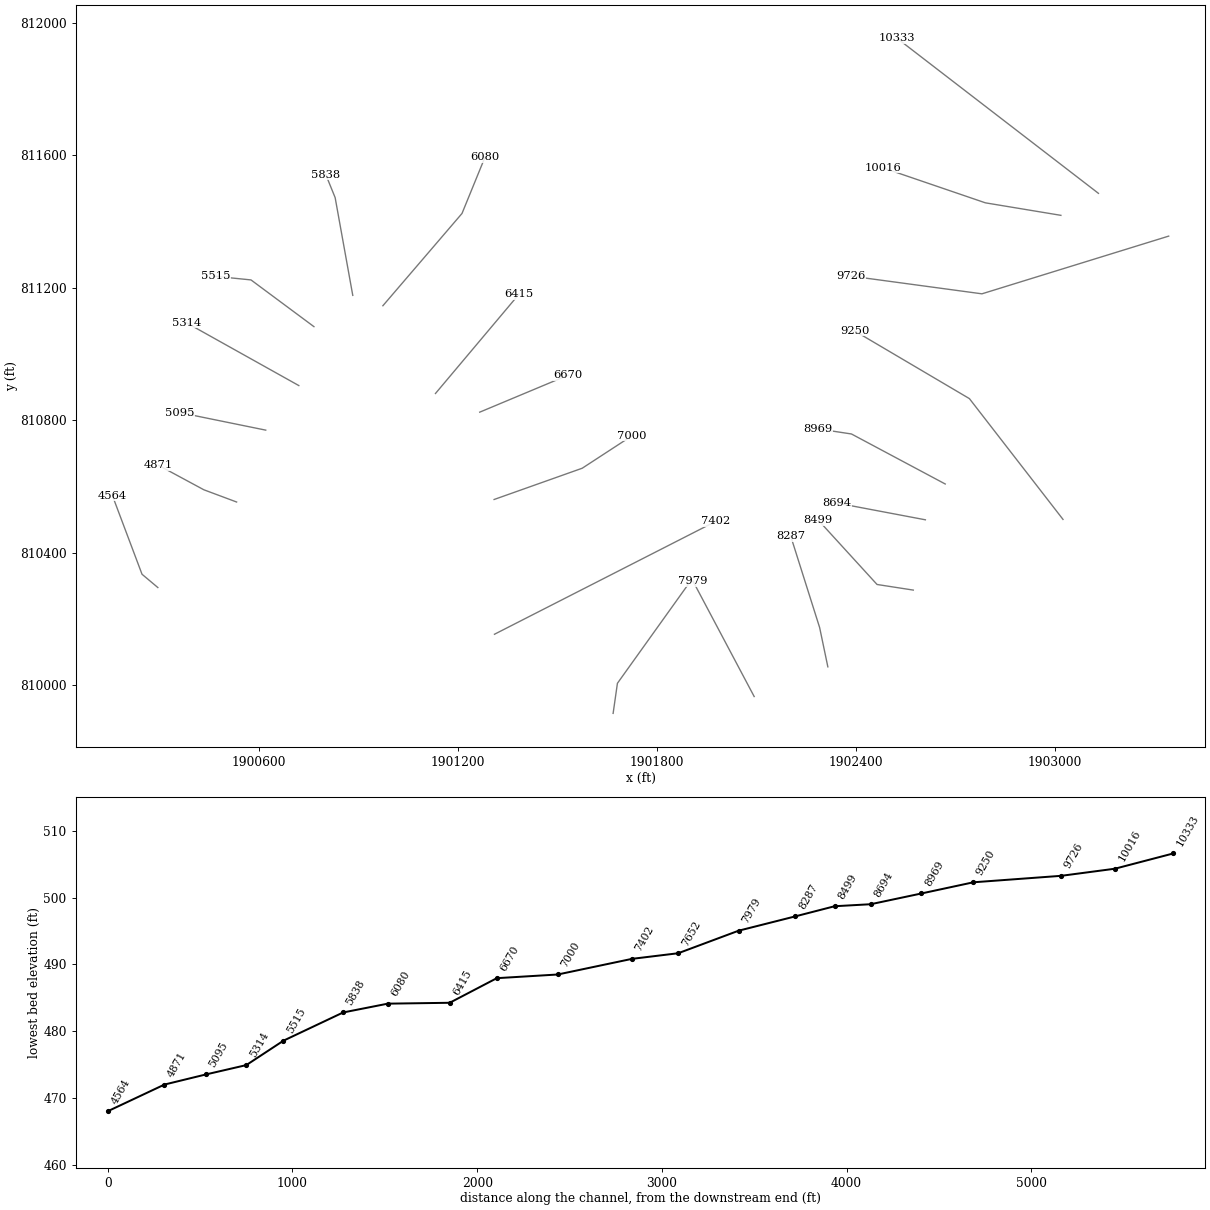
HEC-RAS study MeadowCreek.prj: MeadowCreek Detailed Study

--- MeadowCreek.g01 (geometry) --- (continued)

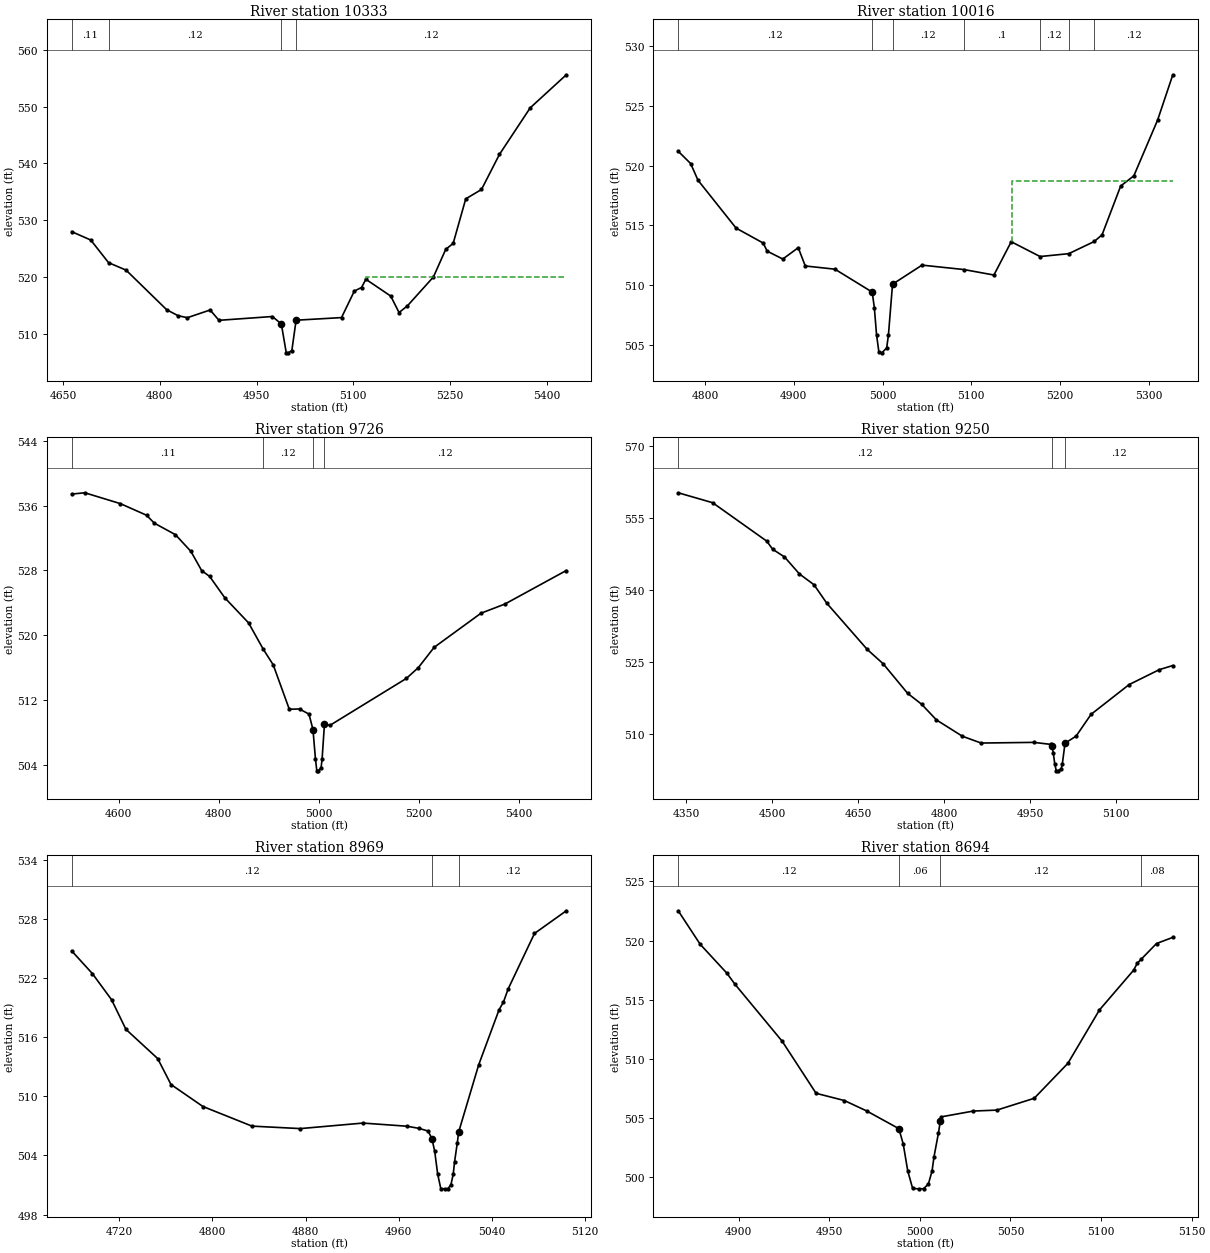
Type RM Length L Ch R = 1 ,10333   ,194,317,289
BEGIN DESCRIPTION:
Meadow Creek 35.0
END DESCRIPTION:
XS GIS Cut Line= 2
       1903132.5       811484.57       1902525.1       811952.58
#Sta/Elev= 30
  4663.4  527.95    4693  526.47  4720.5  522.49  4747.7  521.17  4810.7  514.19
    4828  513.16  4842.6  512.79    4878  514.15  4891.7  512.33  4974.5     513
  4988.4  511.69    4996  506.63  4999.3   506.6  5004.7  507.01  5011.3  512.35
  5081.7  512.81  5101.6  517.49  5112.7  518.11  5119.5  519.56    5158   516.6
  5170.9   513.7  5183.8  514.87  5224.2  519.97  5243.3  524.84  5254.8  525.88
  5274.3  533.73  5298.7  535.38  5326.6  541.57  5374.3  549.77  5430.2  555.59
#Mann= 4 ,-1 , 0
  4663.4     .11       0  4720.5     .12       0  4988.4     .06       0
  5011.3     .12       0
#XS Ineff= 2 , 0
       0                  5119.5       0     520
Permanent Ineff=
       F       F
Bank Sta=4988.4,5011.3
XS Rating Curve= 0 ,0
Exp/Cntr=0.3,0.1

Type RM Length L Ch R = 1 ,10016   ,220,290,312
BEGIN DESCRIPTION:
Meadow Creek 34.0
END DESCRIPTION:
XS GIS Cut Line= 3
      1903019.27       811418.15      1902791.37       811455.92
       1902482.8       811561.38
#Sta/Elev= 30
  4769.9   521.2  4783.9  520.17  4792.2  518.77  4835.1  514.76  4865.6  513.51
  4870.1  512.83  4887.7  512.17  4905.1  513.12    4913  511.59  4946.4  511.32
  4988.4   509.4  4990.8   508.1  4993.3  505.82    4996  504.34  4999.3  504.31
  5004.7  504.72  5006.7  505.82  5011.3  510.06  5044.5  511.66  5091.6  511.29
  5125.5  510.83    5145  513.62  5177.5  512.38  5209.8  512.62  5238.5  513.64
  5247.3   514.2  5268.3  518.29  5283.1  519.14  5309.9  523.82    5327  527.61
#Mann= 7 ,-1 , 0
  4769.9     .12       0  4988.4     .06       0  5011.3     .12       0
  5091.6      .1       0  5177.5     .12       0  5209.8      .1       0
  5238.5     .12       0
#XS Ineff= 2 , 0
                         5145.57          518.72
Permanent Ineff=
       F       F
Bank Sta=4988.4,5011.3
XS Rating Curve= 0 ,0
Exp/Cntr=0.3,0.1

Type RM Length L Ch R = 1 ,9726    ,427,476,329
BEGIN DESCRIPTION:
Meadow Creek 33.0
END DESCRIPTION:
XS GIS Cut Line= 3
      1903344.43       811355.42      1902780.95       811181.18
      1902386.45       811234.56
#Sta/Elev= 30
  4506.5  537.43  4532.7  537.59  4603.7  536.25  4655.9  534.82  4671.5  533.84
  4713.8  532.41  4744.6  530.35  4766.1  527.98    4782  527.26  4812.3  524.62
  4859.8  521.52  4889.2  518.26    4909  516.34  4941.1  510.86  4961.5  510.89
  4980.5  510.25  4988.4  508.34  4993.3  504.76    4996  503.28  4999.3  503.25
  5004.7  503.66  5006.7  504.76  5011.3     509  5022.1  508.86  5174.9  514.66
  5198.9     516  5230.4   518.5  5324.1  522.72  5371.5  523.84  5494.4  527.99
#Mann= 4 ,-1 , 0
  4506.5     .11       0  4889.2     .12       0  4988.4     .06       0
  5011.3     .12       0
Bank Sta=4988.4,5011.3
XS Rating Curve= 0 ,0
Exp/Cntr=0.3,0.1

Type RM Length L Ch R = 1 ,9250    ,272,281,287
BEGIN DESCRIPTION:
Meadow Creek 32.0
END DESCRIPTION:
XS GIS Cut Line= 3
       1903025.6       810500.04      1902743.19       810864.77
      1902396.81       811069.22
#Sta/Elev= 30
    4336  560.21  4396.1  558.14  4490.5  550.14    4501  548.43  4521.5  546.85
  4547.7  543.29    4573  541.06  4595.5  537.18  4666.1  527.56  4693.7   524.6
  4736.5  518.43  4760.9  516.16  4786.8  512.89  4832.1  509.49  4864.8  508.07
  4956.8  508.21  4986.6  507.79  4988.4  507.37  4990.8  506.07  4993.3  503.79
    4996  502.31  4999.3  502.28  5004.7  502.69  5006.7  503.79  5011.3  508.03
  5030.7  509.52  5056.8  514.05  5123.2  520.25  5175.9  523.36  5199.5  524.22
#Mann= 3 ,-1 , 0
    4336     .12       0  4988.4     .06       0  5011.3     .12       0
Bank Sta=4988.4,5011.3
XS Rating Curve= 0 ,0
Exp/Cntr=0.3,0.1

Type RM Length L Ch R = 1 ,8969    ,162,275,243
BEGIN DESCRIPTION:
Meadow Creek 31.0
END DESCRIPTION:
XS GIS Cut Line= 3
      1902670.24       810606.98      1902387.33       810758.02
      1902284.82       810773.63
#Sta/Elev= 30
  4679.3  524.74  4697.1  522.43  4713.5  519.79  4725.8  516.79  4753.1  513.82
  4764.5  511.19  4791.9  508.96    4834  506.97  4875.5  506.72  4929.2  507.28
  4967.1  506.96  4977.4  506.74  4985.1  506.47  4988.4   505.7  4990.8   504.4
  4993.3  502.12    4996  500.64  4999.3  500.61    5002  500.62  5004.7  501.02
  5006.7  502.12  5007.8  503.33  5010.2   505.3  5011.3  506.36  5028.5  513.18
    5046  518.77  5049.8  519.56  5053.8  520.88  5076.4  526.51  5103.7  528.81
#Mann= 3 ,-1 , 0
  4679.3     .12       0  4988.4     .06       0  5011.3     .12       0
Bank Sta=4988.4,5011.3
XS Rating Curve= 0 ,0
Exp/Cntr=0.3,0.1

Type RM Length L Ch R = 1 ,8694    ,206,195,153
BEGIN DESCRIPTION:
Meadow Creek 30.0
END DESCRIPTION:
XS GIS Cut Line= 2
      1902610.37       810498.89      1902342.13       810549.67
#Sta/Elev= 30
  4866.6  522.52  4878.7  519.69  4893.4  517.25  4897.9  516.31    4924  511.48
  4942.7  507.08  4958.3  506.47  4970.6  505.59  4988.4  504.09  4990.8  502.79
  4993.3  500.51    4996  499.03  4999.3     499    5002  499.01  5004.7  499.41
  5006.7  500.51  5007.8  501.72  5010.2  503.69  5011.3  504.75  5011.8  505.09
  5029.5  505.58  5042.5  505.66  5063.1  506.66  5081.7  509.62  5099.1  514.13
    5118   517.5    5120  518.09  5122.2  518.43  5130.6  519.75  5139.6  520.27
#Mann= 4 ,-1 , 0
  4866.6     .12       0  4988.4     .06       0  5011.3     .12       0
  5122.2     .08       0
Bank Sta=4988.4,5011.3
XS Rating Curve= 0 ,0
Exp/Cntr=0.3,0.1

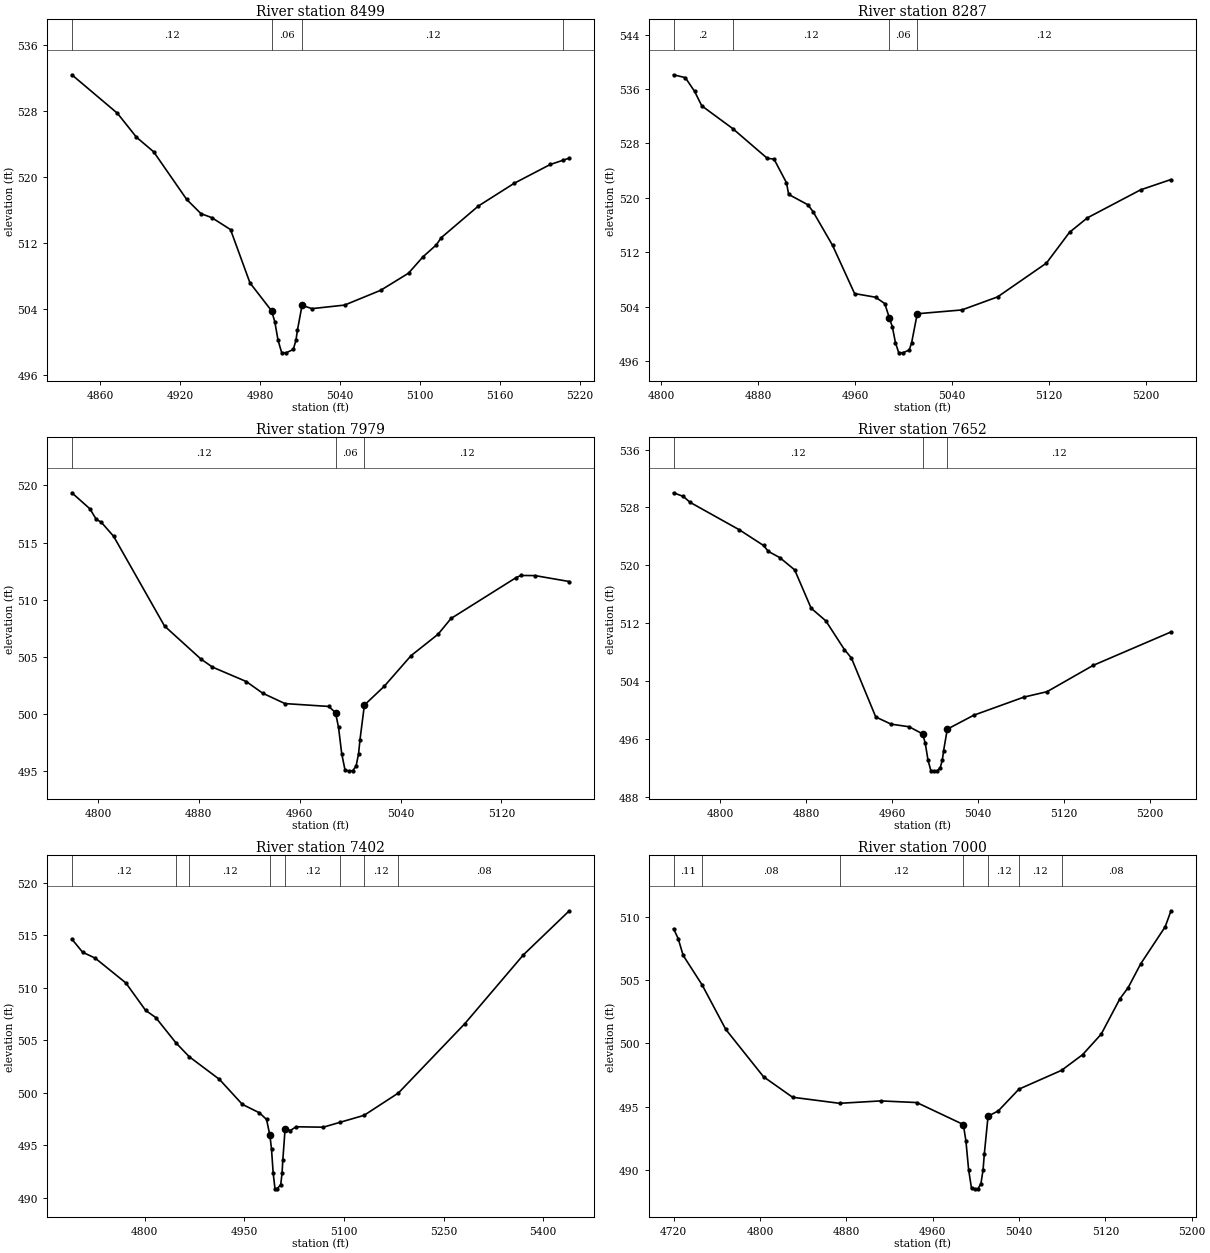
Type RM Length L Ch R = 1 ,8499    ,221,212,162
BEGIN DESCRIPTION:
Meadow Creek 29.0
END DESCRIPTION:
XS GIS Cut Line= 3
      1902573.93       810286.64      1902464.54       810303.57
      1902287.43       810497.61
#Sta/Elev= 30
  4838.5  532.36  4872.7   527.7    4887   524.8  4899.9  523.04  4924.7  517.27
  4935.4  515.55  4943.5  515.07  4957.6  513.62  4972.2  507.17  4988.4  503.79
  4990.8  502.49  4993.3  500.21    4996  498.73  4999.3   498.7  5004.7  499.11
  5006.7  500.21  5007.8  501.42  5011.3  504.45  5018.7  504.05  5043.2  504.48
  5070.3  506.27  5091.2  508.34  5102.1  510.33  5112.1  511.77  5115.7  512.63
  5143.7  516.48  5170.7  519.24  5197.6   521.5  5207.5  522.03  5211.9  522.27
#Mann= 4 ,-1 , 0
  4838.5     .12       0  4988.4     .06       0  5011.3     .12       0
  5207.5     .08       0
Bank Sta=4988.4,5011.3
XS Rating Curve= 0 ,0
Exp/Cntr=0.3,0.1

Type RM Length L Ch R = 1 ,8287    ,281,308,302
BEGIN DESCRIPTION:
Meadow Creek 28.0
END DESCRIPTION:
XS GIS Cut Line= 3
       1902316.1        810054.9      1902291.37       810173.36
      1902204.13       810449.39
#Sta/Elev= 30
  4810.2   538.1  4819.9  537.68  4827.5  535.68  4833.5  533.53    4859  530.19
  4887.6   525.8  4893.1   525.7  4903.4  522.21  4905.2   520.5  4921.1  518.97
  4925.4  517.94  4941.4  513.01  4959.6  505.91    4977  505.37  4984.5  504.43
  4988.4  502.28  4990.8  500.98  4993.3   498.7    4996  497.22  4999.3  497.19
  5004.7   497.6  5006.7   498.7  5011.3  502.94  5048.1   503.5  5077.6  505.42
  5117.9  510.39    5137  514.93  5151.7  517.05  5195.6  521.17  5220.7  522.69
#Mann= 4 ,-1 , 0
  4810.2      .2       0    4859     .12       0  4988.4     .06       0
  5011.3     .12       0
Bank Sta=4988.4,5011.3
XS Rating Curve= 0 ,0
Exp/Cntr=0.3,0.1

Type RM Length L Ch R = 1 ,7979    ,338,327,203
BEGIN DESCRIPTION:
Meadow Creek 27.0
END DESCRIPTION:
XS GIS Cut Line= 2
      1902093.83       809965.22      1901909.12       810313.81
#Sta/Elev= 30
  4779.3  519.35  4793.6  517.95  4798.7  517.02  4802.5  516.79  4812.4  515.55
  4852.8   507.7  4881.6  504.82  4890.8  504.11  4917.6  502.85  4930.6  501.83
  4948.3  500.92    4983  500.67  4988.4  500.13  4990.8  498.83  4993.3  496.55
    4996  495.07  4999.3  495.04    5002  495.05  5004.7  495.45  5006.7  496.55
  5007.8  497.76  5011.3  500.79  5027.1  502.44  5048.3  505.11  5069.7  506.98
    5080  508.36  5131.7  511.94  5135.5  512.12  5146.6  512.11  5173.8  511.59
#Mann= 3 ,-1 , 0
  4779.3     .12       0  4988.4     .06       0  5011.3     .12       0
Bank Sta=4988.4,5011.3
XS Rating Curve= 0 ,0
Exp/Cntr=0.3,0.1

Type RM Length L Ch R = 1 ,7652    ,265,250,207
BEGIN DESCRIPTION:
Meadow Creek 26.0
END DESCRIPTION:
XS GIS Cut Line= 3
      1901668.24       809914.41      1901681.22       810005.25
      1901897.27       810307.38
#Sta/Elev= 30
  4756.4  530.03  4765.6  529.52  4771.6  528.73  4817.8  524.91  4840.2  522.76
  4844.7  521.94  4855.4  521.08  4869.2  519.39  4884.5  514.11  4898.2  512.36
  4915.5   508.4    4922  507.24  4944.7   499.1    4959  498.11  4975.8  497.75
  4988.4  496.76  4990.8  495.46  4993.3  493.18    4996   491.7  4999.3  491.67
    5002  491.68  5004.7  492.08  5006.7  493.18  5007.8  494.39  5011.3  497.42
  5035.9  499.34  5082.6  501.84  5104.2  502.59    5147  506.21  5219.6  510.83
#Mann= 3 ,-1 , 0
  4756.4     .12       0  4988.4     .06       0  5011.3     .12       0
Bank Sta=4988.4,5011.3
XS Rating Curve= 0 ,0
Exp/Cntr=0.3,0.1

Type RM Length L Ch R = 1 ,7402    ,351,402,348
BEGIN DESCRIPTION:
Meadow Creek 25.0
END DESCRIPTION:
XS GIS Cut Line= 2
      1901310.26        810153.3      1901977.52       810493.98
#Sta/Elev= 30
  4690.1  514.65  4706.3   513.4  4725.3  512.83  4771.4  510.47  4801.2  507.85
  4816.4  507.17  4846.8  504.76  4866.9  503.43  4912.4  501.27  4946.8  498.89
  4972.6  498.08  4983.3  497.45  4988.4  495.92  4990.8  494.62  4993.3  492.34
    4996  490.86  4999.3  490.83  5004.7  491.24  5006.7  492.34  5007.8  493.55
  5011.3  496.58  5019.2  496.39  5027.7  496.75  5068.9  496.71  5094.2  497.18
  5130.2  497.84  5181.9  499.97  5281.6  506.56  5370.2  513.15  5439.3  517.35
#Mann= 8 ,-1 , 0
  4690.1     .12       0  4846.8     .08       0  4866.9     .12       0
  4988.4     .06       0  5011.3     .12       0  5094.2     .11       0
  5130.2     .12       0  5181.9     .08       0
Bank Sta=4988.4,5011.3
XS Rating Curve= 0 ,0
Exp/Cntr=0.3,0.1

Type RM Length L Ch R = 1 ,7000    ,269,330,275
BEGIN DESCRIPTION:
Meadow Creek 24.0
END DESCRIPTION:
XS GIS Cut Line= 3
      1901309.17        810560.2        1901575.       810654.59
      1901724.77       810752.27
#Sta/Elev= 30
  4719.9  509.08  4724.2   508.3  4728.8  506.97  4746.4  504.63  4768.3  501.11
  4803.3  497.36  4830.2  495.74  4873.7  495.26  4911.9  495.45  4945.3  495.32
  4988.4  493.58  4990.8  492.28  4993.3     490    4996  488.52  4999.3  488.49
    5002   488.5  5004.7   488.9  5006.7     490  5007.8  491.21  5011.3  494.24
  5020.8  494.66  5039.9  496.38  5079.4  497.87  5098.9  499.11  5116.1  500.73
  5133.5  503.54    5141   504.4  5152.8  506.31  5175.4  509.23  5180.8   510.5
#Mann= 7 ,-1 , 0
  4719.9     .11       0  4746.4     .08       0  4873.7     .12       0
  4988.4     .06       0  5011.3     .12       0  5039.9     .12       0
  5079.4     .08       0
Bank Sta=4988.4,5011.3
XS Rating Curve= 0 ,0
Exp/Cntr=0.3,0.1

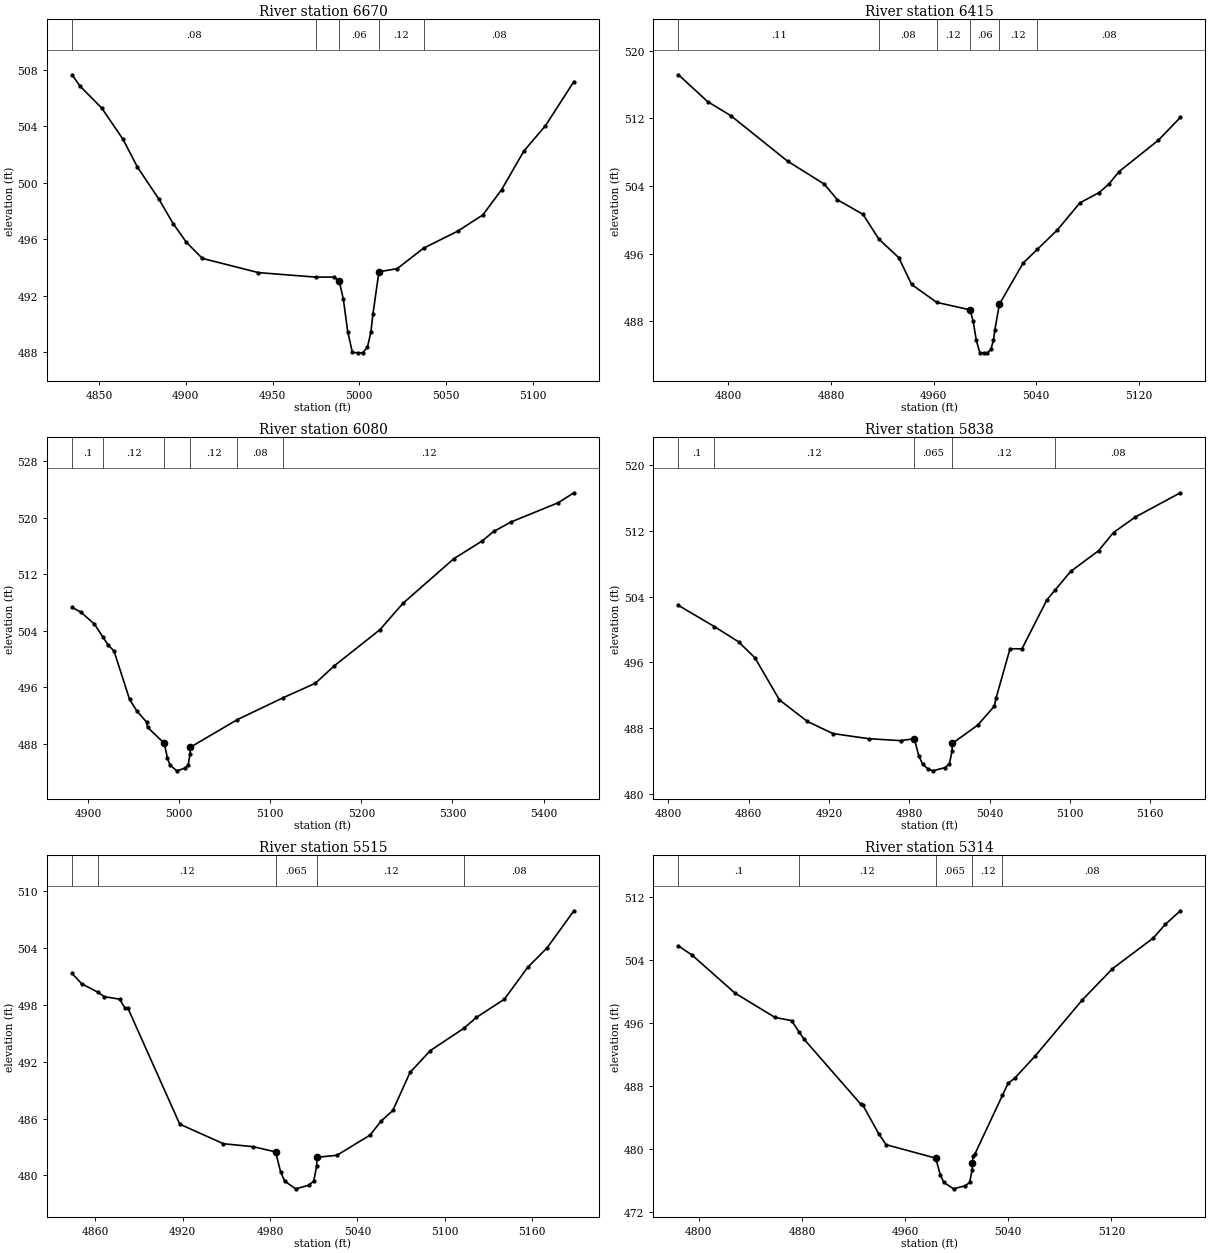
Type RM Length L Ch R = 1 ,6670    ,195,255,246
BEGIN DESCRIPTION:
Meadow Creek 23.0
END DESCRIPTION:
XS GIS Cut Line= 2
      1901265.79       810823.88      1901532.64       810935.61
#Sta/Elev= 30
  4834.4  507.66  4839.1  506.84  4851.5   505.3  4863.8  503.08    4872  501.13
  4884.5  498.83  4892.7   497.1  4900.3  495.78  4909.5  494.64  4941.8  493.63
    4975  493.31  4985.5  493.31  4988.4  493.03  4990.8  491.73  4993.3  489.45
    4996  487.97  4999.3  487.94    5002  487.95  5004.7  488.35  5006.7  489.45
  5007.8  490.66  5011.3  493.69  5021.8  493.91    5037  495.36  5056.7  496.57
  5071.2  497.72    5082  499.51  5094.9  502.26  5107.3  504.05  5123.7  507.18
#Mann= 5 ,-1 , 0
  4834.4     .08       0    4975     .12       0  4988.4     .06       0
  5011.3     .12       0    5037     .08       0
Bank Sta=4988.4,5011.3
XS Rating Curve= 0 ,0
Exp/Cntr=0.3,0.1

Type RM Length L Ch R = 1 ,6415    ,291,335,293
BEGIN DESCRIPTION:
Meadow Creek 22.0
END DESCRIPTION:
XS GIS Cut Line= 2
      1901132.27       810880.26      1901384.05       811179.79
#Sta/Elev= 30
  4761.1  517.17  4783.8     514  4802.1  512.31  4846.2  506.94  4874.8  504.23
  4884.9  502.39    4905  500.65  4917.3  497.73  4932.9  495.52  4942.9  492.35
  4962.5  490.23  4988.4  489.35  4990.8  488.05  4993.3  485.77    4996  484.29
  4999.3  484.26    5002  484.27  5004.7  484.67  5006.7  485.77  5007.8  486.98
  5011.3  490.01  5029.8  494.88  5040.9  496.51  5056.6  498.82  5074.1  502.01
  5089.1  503.23  5096.6  504.22  5104.6  505.71  5135.1   509.4  5152.4  512.12
#Mann= 6 ,-1 , 0
  4761.1     .11       0  4917.3     .08       0  4962.5     .12       0
  4988.4     .06       0  5011.3     .12       0  5040.9     .08       0
Bank Sta=4988.4,5011.3
XS Rating Curve= 0 ,0
Exp/Cntr=0.3,0.1

Type RM Length L Ch R = 1 ,6080    ,200,242,269
BEGIN DESCRIPTION:
Meadow Creek 21.0
END DESCRIPTION:
XS GIS Cut Line= 3
      1900973.61        811145.2      1901212.32       811423.83
      1901281.77         811594.
#Sta/Elev= 30
  4882.6  507.28  4891.9  506.64  4907.1  504.93  4916.3  503.11  4922.1  501.97
  4928.6  501.11  4945.7  494.25  4953.7  492.61  4964.4  491.03  4965.4  490.31
  4983.8  488.03  4987.2  485.95    4990  484.95  4997.6  484.13  5006.7  484.52
    5010  484.95    5012  486.52  5012.2  487.46  5063.9  491.38  5114.3  494.49
  5149.6  496.54  5170.5  499.02  5220.4  504.12  5245.6  507.85  5301.6  514.19
  5332.7   516.7  5345.2  518.04  5364.6   519.4  5416.1  522.11  5433.3  523.52
#Mann= 6 ,-1 , 0
  4882.6      .1       0  4916.3     .12       0  4983.8    .065       0
  5012.2     .12       0  5063.9     .08       0  5114.3     .12       0
Bank Sta=4983.8,5012.2
XS Rating Curve= 0 ,0
Exp/Cntr=0.3,0.1

Type RM Length L Ch R = 1 ,5838    ,233,323,314
BEGIN DESCRIPTION:
Meadow Creek 20.0
END DESCRIPTION:
XS GIS Cut Line= 3
      1900882.73       811176.51      1900829.56       811471.65
      1900801.36       811541.05
#Sta/Elev= 30
  4807.7  502.92  4834.6  500.34  4852.6  498.49  4864.8  496.55  4883.1  491.43
    4904  488.81  4923.1  487.34  4949.7  486.72  4973.6  486.48  4983.8  486.71
  4987.2  484.63    4990  483.63  4993.9  483.06  4997.6  482.81  5006.7   483.2
    5010  483.63    5012   485.2  5012.2  486.14  5031.2  488.37  5043.6  490.67
  5044.9  491.66  5055.3  497.65  5064.2  497.64  5082.9   503.6  5089.2  504.83
  5100.6  507.05  5121.4  509.56  5132.6  511.78    5149  513.67  5182.5  516.61
#Mann= 5 ,-1 , 0
  4807.7      .1       0  4834.6     .12       0  4983.8    .065       0
  5012.2     .12       0  5089.2     .08       0
Bank Sta=4983.8,5012.2
XS Rating Curve= 0 ,0
Exp/Cntr=0.3,0.1

Type RM Length L Ch R = 1 ,5515    ,193,201,202
BEGIN DESCRIPTION:
Meadow Creek 19.0
END DESCRIPTION:
XS GIS Cut Line= 3
      1900765.56       811082.09      1900575.65       811223.17
      1900468.27       811234.02
#Sta/Elev= 30
  4844.1  501.32  4850.8  500.22  4861.7  499.36  4866.2  498.88  4876.7  498.61
  4880.4  497.68  4882.3   497.7    4918  485.42    4948  483.35  4968.4  483.04
  4983.8  482.49  4987.2  480.41    4990  479.41  4997.6  478.59  5006.7  478.98
    5010  479.41    5012  480.98  5012.2  481.92  5025.9  482.13  5048.6  484.26
  5056.3  485.75  5064.3  486.86  5076.1  490.88  5090.1  493.19  5113.2  495.55
  5121.6  496.68  5140.9  498.61  5156.8  501.96  5170.2  504.03  5188.6  507.94
#Mann= 5 ,-1 , 0
  4844.1      .1       0  4861.7     .12       0  4983.8    .065       0
  5012.2     .12       0  5113.2     .08       0
Bank Sta=4983.8,5012.2
XS Rating Curve= 0 ,0
Exp/Cntr=0.3,0.1

Type RM Length L Ch R = 1 ,5314    ,204,219,223
BEGIN DESCRIPTION:
Meadow Creek 18.0
END DESCRIPTION:
XS GIS Cut Line= 2
      1900719.97       810904.16      1900380.35       811094.04
#Sta/Elev= 30
  4784.3  505.81  4794.9  504.64  4828.1  499.82  4859.2  496.72    4872  496.32
  4877.6  494.92  4881.8  493.93  4925.7  485.69  4927.1  485.62  4939.6  481.93
  4945.3  480.55  4983.8  478.84  4987.2  476.76    4990  475.76  4997.6  474.94
  5006.7  475.33    5010  475.76    5012  477.33  5012.2  478.27  5012.7  479.07
  5014.2  479.39  5035.5  486.83  5039.8  488.33  5045.1  489.02  5060.8  491.81
  5097.5  498.97  5120.8  502.92  5152.4  506.81  5161.9  508.58  5173.4  510.28
#Mann= 5 ,-1 , 0
  4784.3      .1       0  4877.6     .12       0  4983.8    .065       0
  5012.2     .12       0  5035.5     .08       0
Bank Sta=4983.8,5012.2
XS Rating Curve= 0 ,0
Exp/Cntr=0.3,0.1

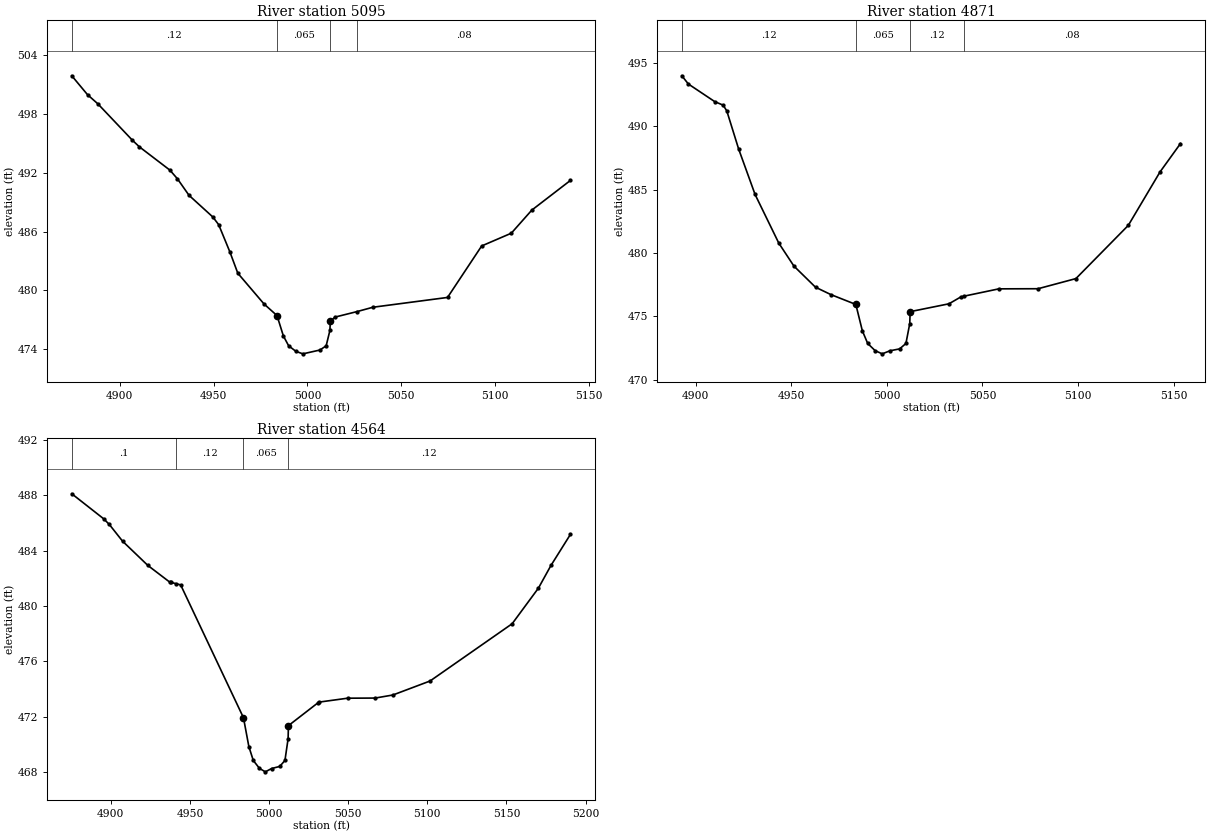
Type RM Length L Ch R = 1 ,5095    ,219,224,200
BEGIN DESCRIPTION:
Meadow Creek 17.0
END DESCRIPTION:
XS GIS Cut Line= 2
      1900620.14       810769.61      1900359.71       810822.78
#Sta/Elev= 30
  4874.4  501.89  4882.8  499.96  4888.3  499.03  4906.7  495.32  4910.4  494.65
  4926.7  492.27  4930.7  491.39  4936.9   489.7  4949.6  487.49  4952.7  486.71
  4958.7  483.92  4962.9  481.76  4976.9  478.62  4983.8  477.44  4987.2  475.36
    4990  474.36  4993.9  473.79  4997.6  473.54  5006.7  473.93    5010  474.36
    5012  475.93  5012.2  476.87  5014.8  477.29  5026.5  477.85  5034.9  478.29
  5074.7  479.29  5092.9  484.54  5108.7  485.84  5119.6  488.19  5140.2  491.22
#Mann= 4 ,-1 , 0
  4874.4     .12       0  4983.8    .065       0  5012.2     .12       0
  5026.5     .08       0
Bank Sta=4983.8,5012.2
XS Rating Curve= 0 ,0
Exp/Cntr=0.3,0.1

Type RM Length L Ch R = 1 ,4871    ,321,307,254
BEGIN DESCRIPTION:
Meadow Creek 16.0
END DESCRIPTION:
XS GIS Cut Line= 3
      1900532.26       810552.59      1900433.51       810589.49
      1900296.77       810663.28
#Sta/Elev= 30
  4892.8  493.98  4896.2  493.33    4910  491.94  4914.4  491.66  4916.3  491.21
  4922.5   488.2  4931.1  484.61  4943.5  480.77  4951.4  478.96  4962.7  477.29
  4970.7  476.71  4983.8  475.93  4987.2  473.85    4990  472.85  4993.9  472.28
  4997.6  472.03  5001.6  472.27  5006.7  472.42    5010  472.85    5012  474.42
  5012.2  475.36  5032.5  475.98  5038.8  476.53  5040.3  476.58  5058.6  477.16
  5079.1  477.17  5098.9  477.97  5126.3  482.17  5142.9  486.39  5153.6  488.63
#Mann= 4 ,-1 , 0
  4892.8     .12       0  4983.8    .065       0  5012.2     .12       0
  5040.3     .08       0
Bank Sta=4983.8,5012.2
XS Rating Curve= 0 ,0
Exp/Cntr=0.3,0.1

Type RM Length L Ch R = 1 ,4564    ,183,199,216
BEGIN DESCRIPTION:
Meadow Creek 15.0
END DESCRIPTION:
XS GIS Cut Line= 3
      1900294.61       810294.36      1900246.88        810334.5
       1900157.9       810571.05
#Sta/Elev= 29
  4875.3  488.09  4895.4  486.29    4899  485.88  4907.4  484.67  4923.4  482.92
  4937.2  481.72  4937.7  481.71  4941.4   481.6  4944.1  481.52  4983.8  471.94
  4987.2  469.86    4990  468.86  4993.9  468.29  4997.6  468.04  5001.6  468.28
  5006.7  468.43    5010  468.86    5012  470.43  5012.2  471.37    5031  473.03
  5031.7  473.07  5049.6  473.35    5067  473.36  5078.2  473.58  5101.7  474.59
  5153.6  478.72  5170.2  481.29  5178.1  482.92  5190.4  485.16
#Mann= 4 ,-1 , 0
  4875.3      .1       0  4941.4     .12       0  4983.8    .065       0
  5012.2     .12       0
Bank Sta=4983.8,5012.2
XS Rating Curve= 0 ,0
Exp/Cntr=0.3,0.1