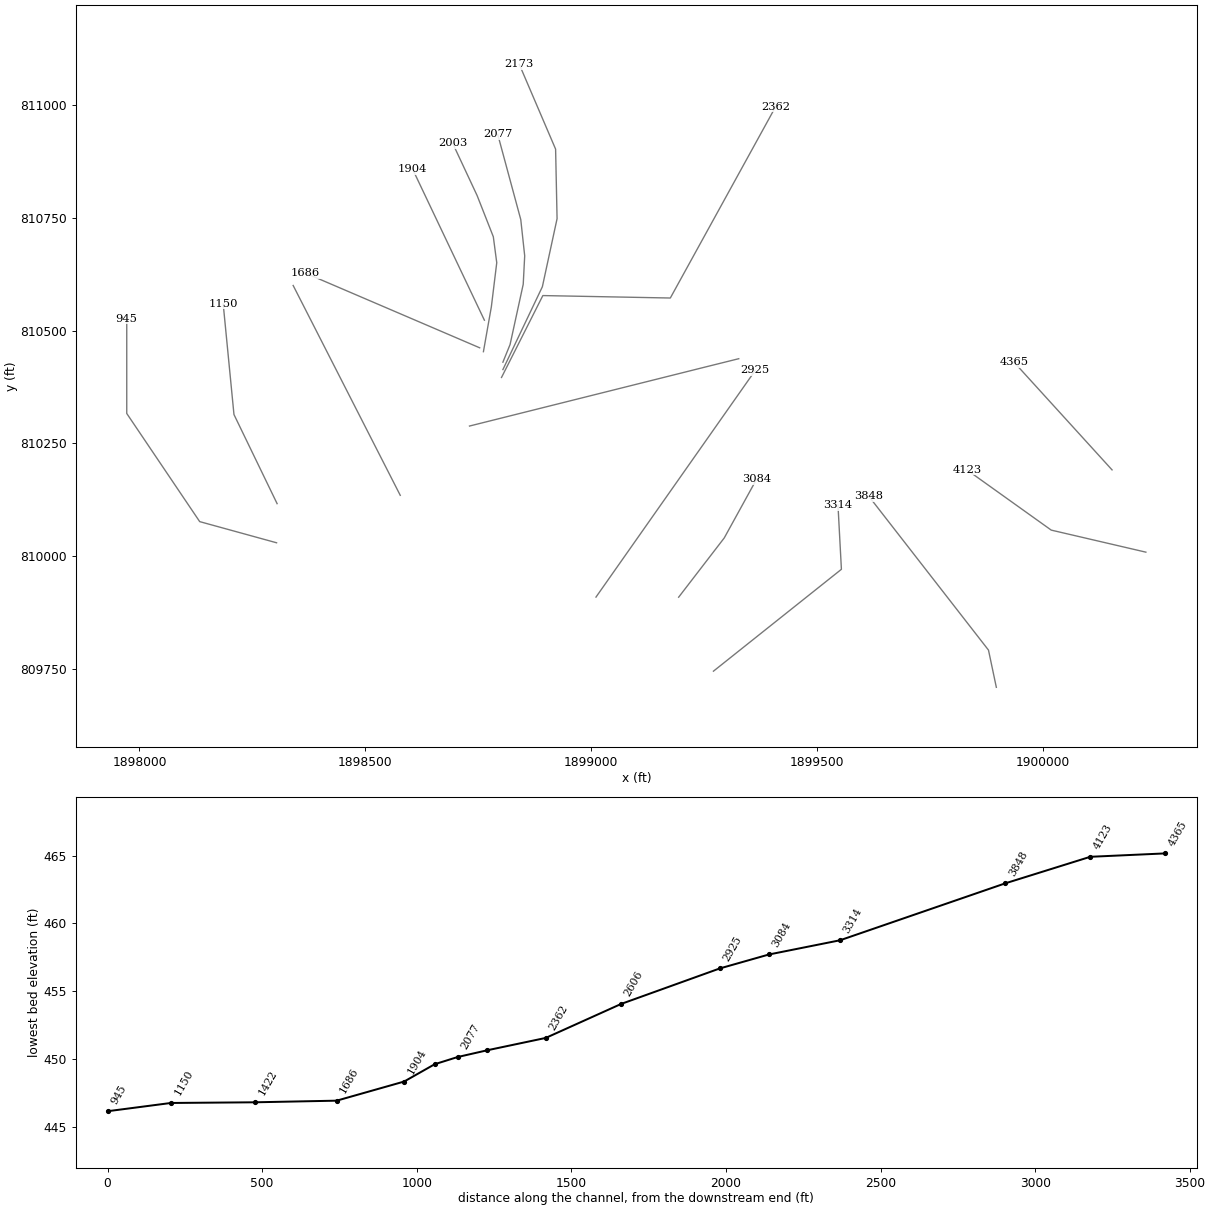
HEC-RAS study MeadowCreek.prj: MeadowCreek Detailed Study

--- MeadowCreek.g01 (geometry) --- (continued)

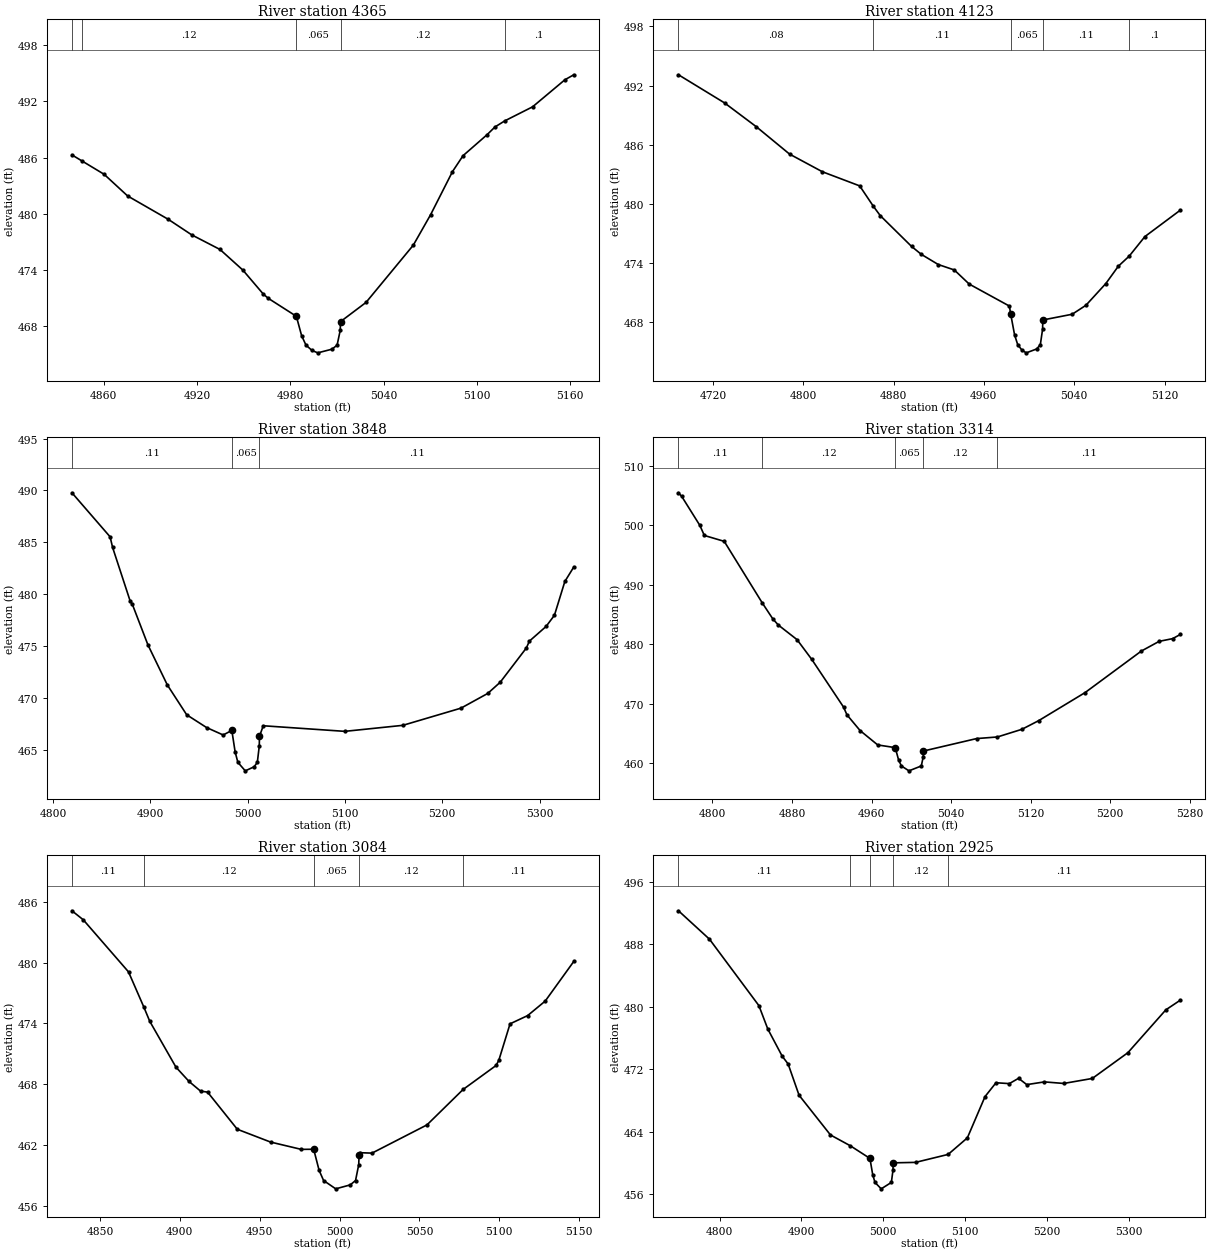
Type RM Length L Ch R = 1 ,4365    ,213,242,229
BEGIN DESCRIPTION:
Meadow Creek 14.0
END DESCRIPTION:
XS GIS Cut Line= 2
      1900152.51       810191.23      1899935.44       810430.01
#Sta/Elev= 30
  4839.5  486.28  4845.8  485.65  4860.2  484.21  4875.3   481.9  4901.4  479.41
  4916.5  477.75  4934.7  476.19  4949.4  473.99  4962.6  471.42  4965.8  470.97
  4983.8  469.06  4987.2  466.98    4990  465.98  4993.9  465.41  4997.6  465.16
  5006.7  465.55    5010  465.98    5012  467.55  5012.2  468.49  5028.6  470.54
    5059  476.65  5070.1  479.89  5084.2   484.5    5091   486.2  5106.4  488.43
  5111.5  489.26  5117.8  489.91  5135.7  491.41  5156.5   494.3  5162.2  494.83
#Mann= 5 ,-1 , 0
  4839.5      .2       0  4845.8     .12       0  4983.8    .065       0
  5012.2     .12       0  5117.8      .1       0
Bank Sta=4983.8,5012.2
XS Rating Curve= 0 ,0
Exp/Cntr=0.3,0.1

Type RM Length L Ch R = 1 ,4123    ,290,275,249
BEGIN DESCRIPTION:
Meadow Creek 13.0
END DESCRIPTION:
XS GIS Cut Line= 3
      1900227.37       810008.97      1900017.93        810057.8
      1899831.29       810191.27
#Sta/Elev= 30
  4689.5  493.09  4730.3  490.24  4758.5  487.82  4787.9  485.05    4817  483.26
    4850  481.83  4862.2  479.75  4868.2  478.82  4895.9   475.7  4904.6  474.89
  4919.6  473.86  4933.8  473.31    4947  471.88  4982.6  469.65  4983.8  468.81
  4987.2  466.73    4990  465.73  4993.9  465.16  4997.6  464.91  5006.7   465.3
    5010  465.73    5012   467.3  5012.2  468.24  5038.2  468.82  5050.4  469.73
    5068  471.93  5079.1  473.69  5088.7  474.71  5102.6  476.69    5134  479.37
#Mann= 5 ,-1 , 0
  4689.5     .08       0  4862.2     .11       0  4983.8    .065       0
  5012.2     .11       0  5088.7      .1       0
Bank Sta=4983.8,5012.2
XS Rating Curve= 0 ,0
Exp/Cntr=0.3,0.1

Type RM Length L Ch R = 1 ,3848    ,550,534,256
BEGIN DESCRIPTION:
Meadow Creek 12.0
END DESCRIPTION:
XS GIS Cut Line= 3
       1899896.4       809709.52      1899879.04       809791.96
       1899614.3       810132.65
#Sta/Elev= 30
  4819.5  489.78  4858.7  485.53  4861.3   484.5  4879.3  479.34  4881.6  479.01
  4897.6   475.1  4917.5  471.24  4937.4  468.36  4957.8  467.13  4974.9  466.41
  4983.8  466.85  4987.2  464.77    4990  463.77  4997.6  462.95  5006.7  463.34
    5010  463.77    5012  465.34  5012.2  466.28  5016.1   467.3  5099.9  466.76
  5159.5  467.34  5219.3     469  5246.8  470.42  5259.6   471.5  5286.5  474.81
  5289.5  475.46  5306.7  476.88  5315.3  477.96    5326  481.22  5335.2  482.62
#Mann= 3 ,-1 , 0
  4819.5     .11       0  4983.8    .065       0  5012.2     .11       0
Bank Sta=4983.8,5012.2
XS Rating Curve= 0 ,0
Exp/Cntr=0.3,0.1

Type RM Length L Ch R = 1 ,3314    ,210,230,245
BEGIN DESCRIPTION:
Meadow Creek 11.0
END DESCRIPTION:
XS GIS Cut Line= 3
      1899270.31        809745.3      1899553.52         809971.
      1899545.92       810113.16
#Sta/Elev= 30
  4765.9  505.46  4769.2  504.84  4787.4  499.98  4791.9  498.29  4811.9   497.3
  4850.2  486.94  4860.8  484.26  4866.3  483.24  4885.1  480.79  4899.9  477.47
  4931.8  469.47  4935.3  468.15  4948.5  465.51  4966.2   463.1  4983.8  462.65
  4987.2  460.57    4990  459.57  4997.6  458.75    5010  459.57    5012  461.14
  5012.2  462.08  5065.6  464.17  5086.5  464.44  5111.2  465.73    5128  467.18
  5174.7   471.9  5231.2  478.87  5249.1   480.5  5262.7  480.96  5270.4  481.66
#Mann= 5 ,-1 , 0
  4765.9     .11       0  4850.2     .12       0  4983.8    .065       0
  5012.2     .12       0  5086.5     .11       0
Bank Sta=4983.8,5012.2
XS Rating Curve= 0 ,0
Exp/Cntr=0.3,0.1

Type RM Length L Ch R = 1 ,3084    ,156,159,153
BEGIN DESCRIPTION:
Meadow Creek 10.0
END DESCRIPTION:
XS GIS Cut Line= 3
       1899193.3       809909.19      1899294.19       810040.44
      1899365.78       810170.61
#Sta/Elev= 30
  4832.5   485.1  4839.6  484.21  4867.9  479.08  4877.5  475.61  4881.2  474.21
  4897.6  469.69  4905.8  468.28    4913  467.33  4917.4  467.23    4936  463.57
  4956.8  462.31    4976  461.59  4983.8   461.6  4987.2  459.52    4990  458.52
  4997.6   457.7  5006.7  458.09    5010  458.52    5012  460.09  5012.2  461.03
  5012.8  461.26  5020.3  461.22  5054.7     464  5077.3  467.49    5098  469.86
  5099.7  470.38  5106.7  473.96  5117.7  474.77  5128.7   476.2  5146.6  480.11
#Mann= 5 ,-1 , 0
  4832.5     .11       0  4877.5     .12       0  4983.8    .065       0
  5012.2     .12       0  5077.3     .11       0
Bank Sta=4983.8,5012.2
XS Rating Curve= 0 ,0
Exp/Cntr=0.3,0.1

Type RM Length L Ch R = 1 ,2925    ,360,319,252
BEGIN DESCRIPTION:
Meadow Creek 9.0
END DESCRIPTION:
XS GIS Cut Line= 2
      1899010.35       809909.44      1899362.77       810411.49
#Sta/Elev= 30
  4749.8  492.29  4787.7  488.65  4848.1  480.14    4859  477.14  4876.6  473.66
  4883.8  472.67  4897.2  468.66  4935.6  463.57  4959.8  462.19  4983.8  460.57
  4987.2  458.49    4990  457.49  4997.6  456.67    5010  457.49    5012  459.06
  5012.2     460  5039.6  460.06  5079.4  461.08  5102.9   463.2  5124.5  468.49
  5137.9  470.26  5154.2  470.15  5165.5  470.83  5175.5  470.02  5197.1  470.37
  5220.7  470.17  5255.6  470.81  5299.1  474.11  5345.5   479.6  5363.2  480.84
#Mann= 5 ,-1 , 0
  4749.8     .11       0  4959.8     .12       0  4983.8    .065       0
  5012.2     .12       0  5079.4     .11       0
Bank Sta=4983.8,5012.2
XS Rating Curve= 0 ,0
Exp/Cntr=0.3,0.1

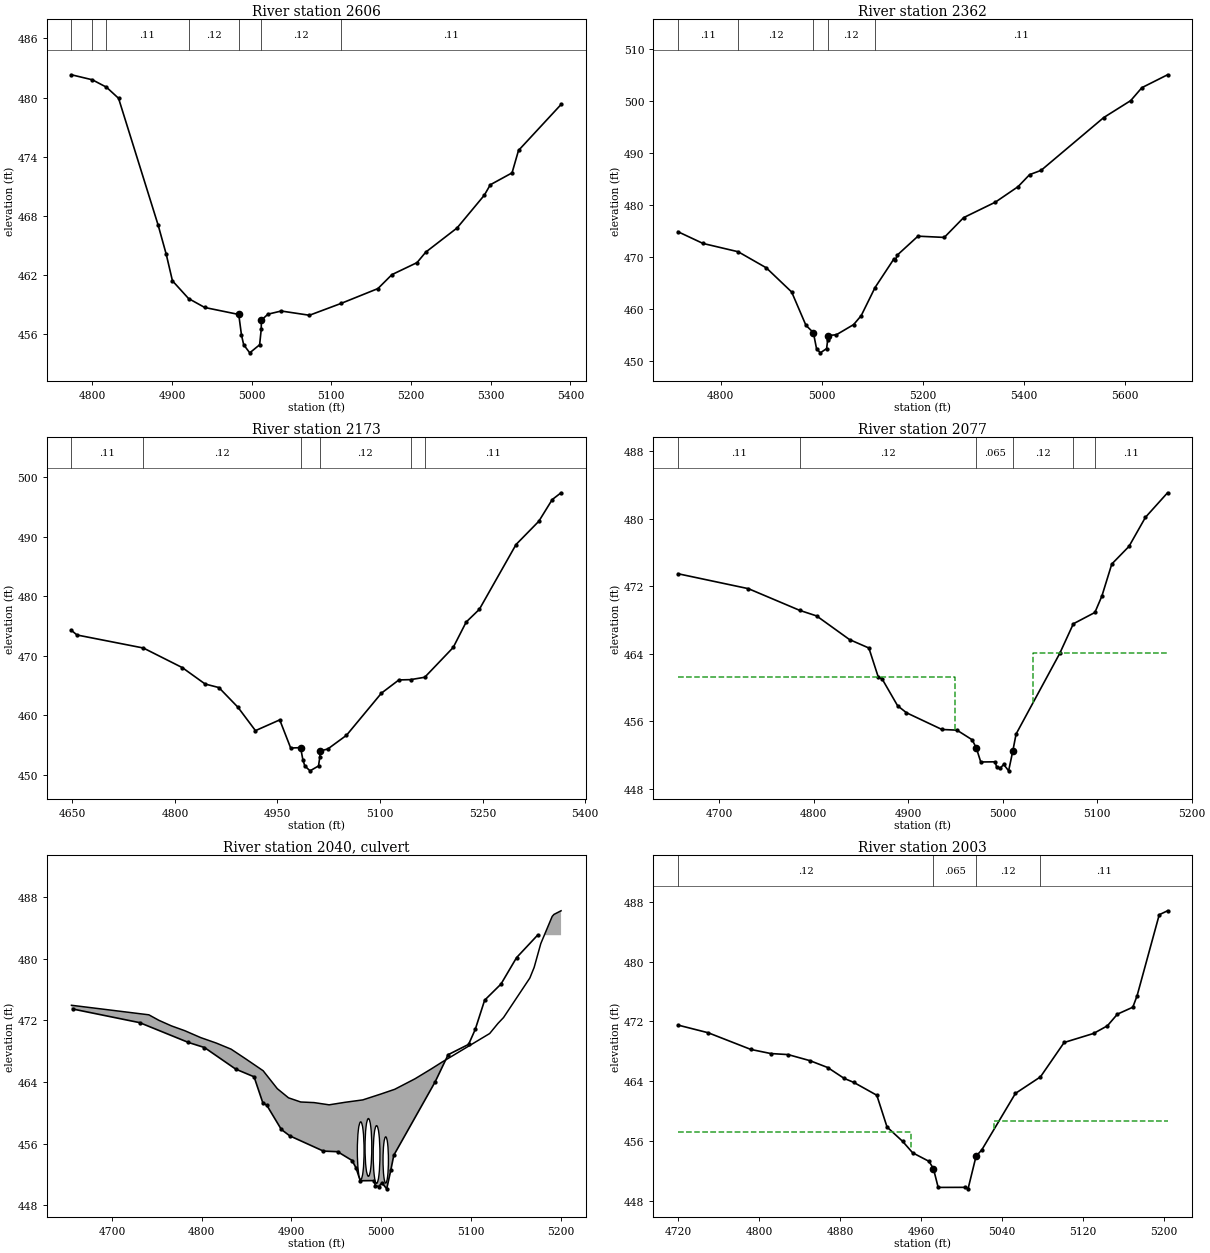
Type RM Length L Ch R = 1 ,2606    ,248,244,207
BEGIN DESCRIPTION:
Meadow Creek 8.0
END DESCRIPTION:
XS GIS Cut Line= 3
      1898730.41       810288.37       1899253.2       810419.37
      1899326.31       810437.56
#Sta/Elev= 30
  4773.9  482.31  4800.1   481.8  4817.8  481.05    4833  479.92  4882.7  467.02
  4892.8  464.07  4900.6  461.37  4920.8  459.57  4941.1  458.66  4983.8  457.95
  4987.2  455.87    4990  454.87  4997.6  454.05    5010  454.87    5012  456.44
  5012.2  457.38  5020.5  457.98  5037.1   458.3  5072.5  457.87  5112.1  459.07
  5158.4  460.58    5176     462  5207.5  463.22  5218.5  464.29  5257.7  466.74
  5291.9  470.07  5299.4  471.13  5326.7  472.34  5334.8  474.62  5388.2  479.29
#Mann= 7 ,-1 , 0
  4773.9     .12       0  4800.1     .05       0  4817.8     .11       0
  4920.8     .12       0  4983.8    .065       0  5012.2     .12       0
  5112.1     .11       0
Bank Sta=4983.8,5012.2
XS Rating Curve= 0 ,0
Exp/Cntr=0.3,0.1

Type RM Length L Ch R = 1 ,2362    ,72,189,265
BEGIN DESCRIPTION:
Meadow Creek 7.0
END DESCRIPTION:
XS GIS Cut Line= 4
      1898801.25         810396.      1898892.75       810577.44
      1899174.87       810572.01      1899408.14       810996.23
#Sta/Elev= 30
  4715.6  474.86  4765.2   472.6  4834.9     471  4890.5  467.91  4940.8  463.25
  4969.1  456.83  4983.8  455.44    4990  452.36  4997.6  451.54    5010  452.36
    5012  453.93  5012.2  454.87  5029.3  455.02  5063.5  456.98  5078.5   458.7
  5105.9  464.11  5143.2  469.61  5146.4  469.43  5150.1  470.37  5190.9     474
    5243  473.76  5281.3  477.57    5344  480.54  5389.1  483.53  5411.9  485.84
  5434.7  486.67  5558.8  496.84  5612.2   500.1  5634.3  502.59  5685.1  505.07
#Mann= 5 ,-1 , 0
  4715.6     .11       0  4834.9     .12       0  4983.8    .065       0
  5012.2     .12       0  5105.9     .11       0
Bank Sta=4983.8,5012.2
XS Rating Curve= 0 ,0
Exp/Cntr=0.3,0.1

Type RM Length L Ch R = 1 ,2173    ,56,96,94
BEGIN DESCRIPTION:
Meadow Creek 6.0
END DESCRIPTION:
XS GIS Cut Line= 5
      1898804.35       810413.48      1898891.67       810596.97
      1898924.22       810747.79      1898920.96       810901.87
      1898840.66        811089.6
#Sta/Elev= 30
  4648.8  474.25  4656.9  473.48  4753.9  471.29  4810.9  467.99  4844.3  465.23
  4864.3  464.64  4892.1  461.34  4917.8  457.39  4953.3   459.2  4969.3  454.47
  4983.8  454.53  4987.2  452.45    4990  451.45  4997.6  450.63    5010  451.45
    5012  453.02  5012.2  453.96  5023.6  454.31  5050.9  456.61    5102   463.7
  5127.5  465.92  5144.6  465.97  5165.3  466.37  5206.9  471.38  5225.9  475.66
  5245.1  477.79  5298.8   488.7  5332.1  492.61  5351.7  496.26  5364.6   497.4
#Mann= 6 ,-1 , 0
  4648.8     .11       0  4753.9     .12       0  4983.8    .065       0
  5012.2     .12       0  5144.6     .05       0  5165.3     .11       0
Bank Sta=4983.8,5012.2
XS Rating Curve= 0 ,0
Exp/Cntr=0.5,0.3

Type RM Length L Ch R = 1 ,2077    ,66,74,75
BEGIN DESCRIPTION:
Meadow Creek Private Drive US
END DESCRIPTION:
XS GIS Cut Line= 6
      1898804.33       810429.88      1898820.21       810469.01
      1898849.31       810602.51      1898852.56       810665.44
      1898843.88       810745.74      1898792.89       810934.53
#Sta/Elev= 30
  4656.2  473.48  4730.8  471.71  4785.1  469.14    4803  468.48  4837.8  465.68
  4858.3  464.68  4868.2  461.25  4872.4     461  4888.7  457.84  4898.1  457.01
  4935.6  455.03  4951.5  454.95  4967.6  453.81    4972  452.84  4976.7  451.18
    4992   451.2  4993.6  450.53  4997.1  450.42    5001  450.89  5006.2  450.13
  5010.7  452.52  5014.1  454.49  5060.3  464.04  5074.7  467.55  5097.5  468.89
  5104.9  470.83  5115.4  474.63  5133.6  476.72    5151  480.16  5174.4  483.07
#Mann= 6 ,-1 , 0
  4656.2     .11       0  4785.1     .12       0    4972    .065       0
  5010.7     .12       0  5074.7     .05       0  5097.5     .11       0
#XS Ineff= 2 , 0
       0 4949.45  461.21  5032.1       0  464.08
Permanent Ineff=
       F       F
Bank Sta=4972,5010.7
XS Rating Curve= 0 ,0
Exp/Cntr=0.5,0.3

Type RM Length L Ch R = 2 ,2040    ,,,
BEGIN DESCRIPTION:
Private Drive - MEC_01 - Survey Date: 10/22/10
Because of poor headwall condition, the entrance loss coefficient was raised to 0.9, and the scale was changed to pipe projecting from fill.
END DESCRIPTION:
Bridge Culvert--1,0,-1,-1, 0
Deck Dist Width WeirC Skew NumUp NumDn MinLoCord MaxHiCord MaxSubmerge Is_Ogee
27,18,3,0, 31, 30, 461.04, , 0.95, 0, 1,1,,
  4654.7    4741  4752.1  4766.2    4781  4798.8  4816.2  4832.7  4849.1  4868.4
  4884.2  4896.7  4910.3  4925.2    4942  4959.8  4979.5  4999.6  5015.2  5037.7
  5056.1  5067.9    5121  5130.3  5136.5  5165.8  5170.6    5178  5190.7  5192.7
  5200.6
  473.97  472.73  472.02  471.29  470.67  469.77  469.06  468.27     467  465.47
  463.14  461.95  461.41  461.33  461.04  461.37  461.68  462.44  463.06  464.42
  465.72  466.59   470.3  471.62  472.38  477.51  478.89  481.98  485.51  485.77
  486.24
  430.13  430.13  430.13  430.13  430.13  430.13  430.13  430.13  430.13  430.13
  430.13  430.13  430.13  430.13  430.13  430.13  430.13  430.13  430.13  430.13
  430.13  430.13  430.13  430.13  430.13  430.13  430.13  430.13  430.13  430.13
  430.13
  4719.7  4766.2    4781  4798.8  4816.2  4832.7  4849.1  4868.4  4884.2  4896.7
  4910.3  4925.2    4942  4959.8  4979.5  4999.6  5015.2  5037.7  5056.1  5067.9
  5078.9  5104.2  5130.3  5136.5  5165.8  5170.6    5178  5190.7  5192.7  5200.6
  471.51  471.29  470.67  469.77  469.06  468.27     467  465.47  463.14  461.95
  461.41  461.33  461.04  461.37  461.68  462.44  463.06  464.42  465.72  466.59
  467.82  469.41  471.62  472.38  477.51  478.89  481.98  485.51  485.77  486.24
   429.6   429.6   429.6   429.6   429.6   429.6   429.6   429.6   429.6   429.6
   429.6   429.6   429.6   429.6   429.6   429.6   429.6   429.6   429.6   429.6
   429.6   429.6   429.6   429.6   429.6   429.6   429.6   429.6   429.6   429.6
Culvert=1,7.5,,28,0.024,0.9,1,2,3,451.33,4977.2,450.17,4977.2,Culvert #1  , 0 ,21
Culvert Bottom n=0.024
Culvert=1,7.5,,28,0.024,0.9,1,2,3,451.76,4985.8,450.03,4985.8,Culvert #2  , 0 ,21
Culvert Bottom n=0.024
Culvert=1,7.5,,28,0.024,0.9,1,2,3,450.84,4994.9,450.2,4994.9,Culvert #3  , 0 ,21
Culvert Bottom n=0.024
Culvert=1,6,,28,0.024,0.9,1,2,3,450.88,5005.1,450.84,5005.1,Culvert #4  , 0 ,21
Culvert Bottom n=0.024
BC Design=,, 0 ,, 0 ,,,,,,
BC HTab HWMax=483.07
BC Use User HTab Curves=0
BC User HTab FreeFlow(D)= 0

Type RM Length L Ch R = 1 ,2003    ,90,99,101
BEGIN DESCRIPTION:
Meadow Creek Private Drive DS
END DESCRIPTION:
XS GIS Cut Line= 6
      1898761.21        810453.1      1898778.78        810552.6
      1898790.71       810650.25      1898783.12       810707.76
      1898747.31       810798.91      1898693.06       810915.01
#Sta/Elev= 30
  4719.7  471.51  4749.6  470.48  4791.7  468.25  4811.4   467.7  4828.5  467.56
    4850  466.75  4867.6  465.83  4883.8  464.38  4893.5  463.83  4916.1  462.12
  4926.2  457.87  4941.6  455.95  4951.5  454.42  4967.6  453.28    4972  452.31
  4976.7  449.79  5003.5   449.8  5006.2   449.6  5014.1  453.96  5019.8  454.82
    5053  462.37  5077.7  464.58  5101.1  469.18  5130.2  470.39  5143.8  471.41
  5153.7  472.97  5168.9   473.9  5173.1  475.42    5195  486.27  5203.2   486.8
#Mann= 4 ,-1 , 0
  4719.7     .12       0    4972    .065       0  5014.1     .12       0
  5077.7     .11       0
#XS Ineff= 2 , 0
       0 4949.45  457.25  5032.1       0   458.7
Permanent Ineff=
       F       F
Bank Sta=4972,5014.1
XS Rating Curve= 0 ,0
Exp/Cntr=0.5,0.3

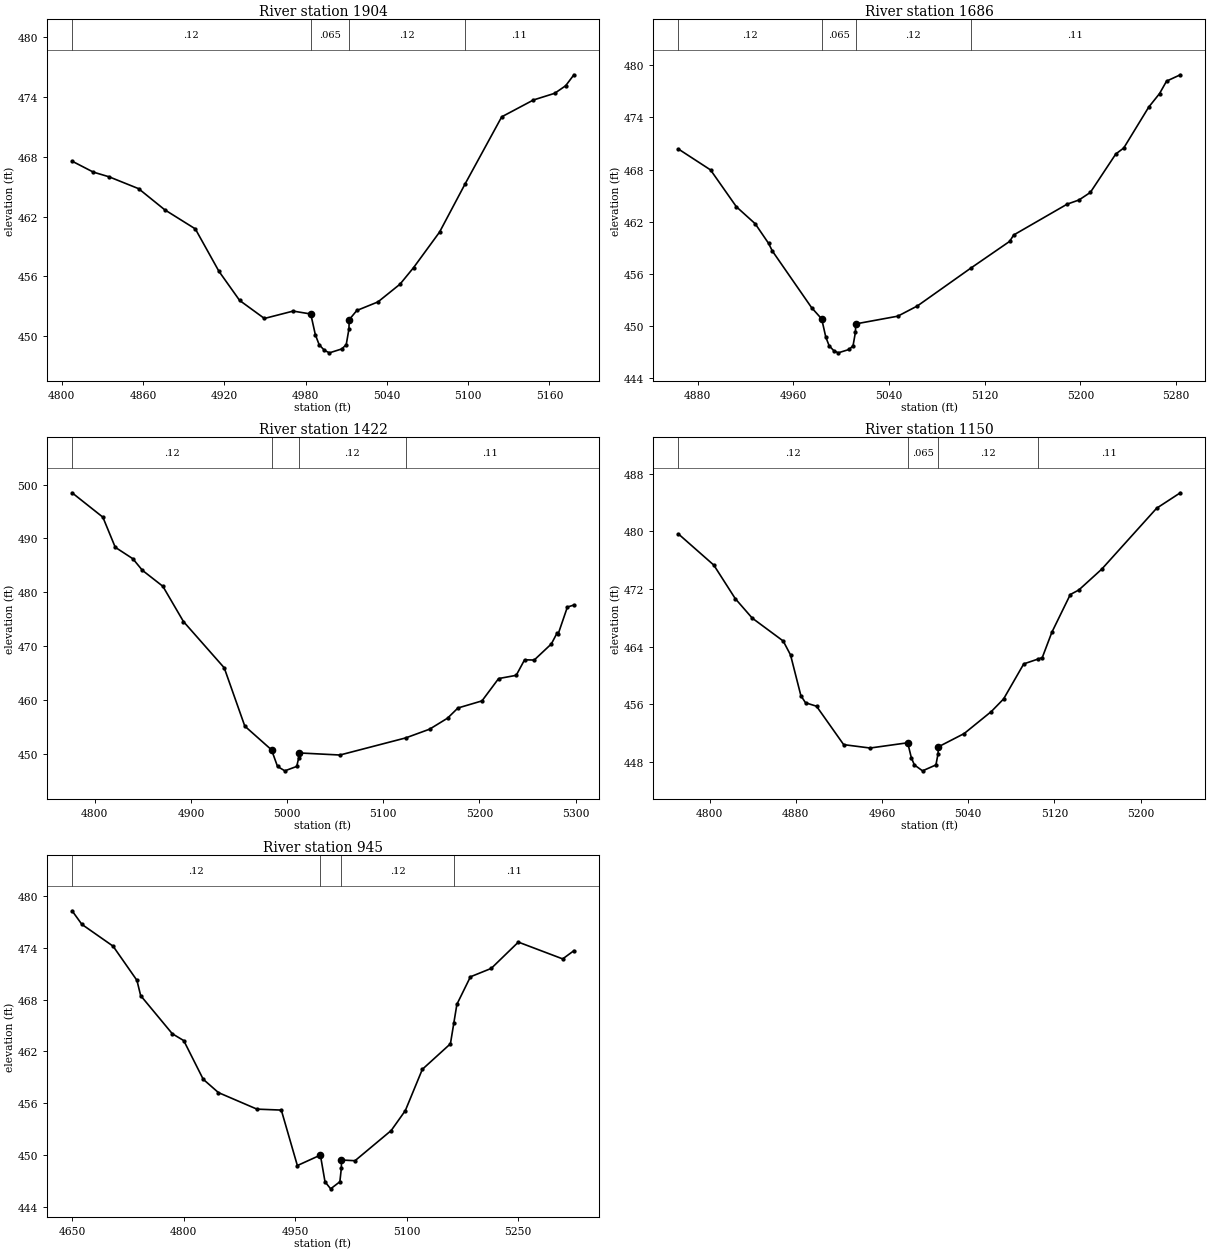
Type RM Length L Ch R = 1 ,1904    ,152,218,223
BEGIN DESCRIPTION:
Meadow Creek 5.0 (A_MEC_01DSX)
END DESCRIPTION:
XS GIS Cut Line= 2
      1898763.35       810522.88      1898604.46       810857.59
#Sta/Elev= 30
  4807.6  467.56  4823.3  466.46  4834.9  465.99  4856.7   464.8    4876  462.68
  4898.6  460.76    4916  456.51  4931.3  453.58  4949.6  451.77  4970.8  452.51
  4983.8  452.22  4987.2  450.14    4990  449.14  4993.9  448.57  4997.6  448.32
  5006.7  448.71    5010  449.14    5012  450.71  5012.2  451.65  5017.8  452.57
  5033.4  453.43  5049.7  455.21  5059.7  456.87  5078.9  460.44  5097.7  465.26
  5124.8  472.01  5148.2   473.7  5163.9  474.37    5172  475.13  5178.1  476.23
#Mann= 4 ,-1 , 0
  4807.6     .12       0  4983.8    .065       0  5012.2     .12       0
  5097.7     .11       0
Bank Sta=4983.8,5012.2
XS Rating Curve= 0 ,0
Exp/Cntr=0.3,0.1

Type RM Length L Ch R = 1 ,1686    ,275,264,188
BEGIN DESCRIPTION:
Meadow Creek 4.0
END DESCRIPTION:
XS GIS Cut Line= 2
      1898752.91       810461.72      1898367.48       810627.09
#Sta/Elev= 30
  4864.1  470.36  4890.9  467.96  4912.5  463.72  4928.2  461.77  4939.4  459.51
  4942.5  458.64  4975.3  452.12  4983.8  450.81  4987.2  448.73    4990  447.73
  4993.9  447.16  4997.6  446.91  5006.7   447.3    5010  447.73    5012   449.3
  5012.2  450.24  5047.4  451.13  5063.8  452.31  5108.2  456.64  5140.9  459.74
  5144.2  460.47  5188.9  464.02  5198.8   464.5  5208.3  465.37  5229.6   469.8
  5236.2  470.48  5257.1  475.19  5266.1  476.74    5272  478.18  5283.5  478.91
#Mann= 4 ,-1 , 0
  4864.1     .12       0  4983.8    .065       0  5012.2     .12       0
  5108.2     .11       0
Bank Sta=4983.8,5012.2
XS Rating Curve= 0 ,0
Exp/Cntr=0.3,0.1

Type RM Length L Ch R = 1 ,1422    ,260,272,243
BEGIN DESCRIPTION:
Meadow Creek 3.0
END DESCRIPTION:
XS GIS Cut Line= 2
      1898577.14       810134.89      1898340.14       810599.77
#Sta/Elev= 30
  4776.4  498.47  4808.4  493.94  4821.3  488.34  4839.6  486.21  4849.5  484.06
  4870.8  481.09  4892.2  474.54  4934.6  465.94    4956   455.1  4983.8  450.69
    4990  447.61  4997.6  446.79    5010  447.61    5012  449.18  5012.2  450.12
  5054.9  449.73  5123.3  452.91  5148.1  454.53  5166.8  456.58  5177.6  458.47
  5202.6  459.79  5219.9  463.94  5238.2  464.54  5246.9  467.43  5256.9  467.38
  5274.7  470.37  5280.5  472.34    5282  472.31  5291.4  477.23  5298.2  477.61
#Mann= 4 ,-1 , 0
  4776.4     .12       0  4983.8    .065       0  5012.2     .12       0
  5123.3     .11       0
Bank Sta=4983.8,5012.2
XS Rating Curve= 0 ,0
Exp/Cntr=0.3,0.1

Type RM Length L Ch R = 1 ,1150    ,190,205,213
BEGIN DESCRIPTION:
Meadow Creek 2.0
END DESCRIPTION:
XS GIS Cut Line= 3
      1898304.59       810116.43      1898209.12       810313.88
      1898185.25       810559.11
#Sta/Elev= 30
  4771.1  479.65  4803.9  475.33  4823.8  470.67  4839.5  467.97  4868.3  464.78
  4875.1  462.84  4884.7  457.18    4889   456.2  4899.2  455.72  4924.4  450.38
  4948.9  449.91  4983.8  450.64  4987.2  448.56    4990  447.56  4997.6  446.74
    5010  447.56    5012  449.13  5012.2  450.07  5036.2  451.92  5061.4  454.98
  5072.8  456.73  5091.5   461.6  5104.3  462.25  5108.7  462.48  5117.6     466
  5134.7  471.24  5142.6  471.87  5163.9  474.77  5214.8  483.23  5236.8  485.38
#Mann= 4 ,-1 , 0
  4771.1     .12       0  4983.8    .065       0  5012.2     .12       0
  5104.3     .11       0
Bank Sta=4983.8,5012.2
XS Rating Curve= 0 ,0
Exp/Cntr=0.3,0.1

Type RM Length L Ch R = 1 ,945     ,0,0,0
BEGIN DESCRIPTION:
Meadow Creek 1.0
END DESCRIPTION:
XS GIS Cut Line= 4
       1898303.4       810029.76      1898133.28       810076.62
      1897971.82       810316.21      1897971.82       810526.24
#Sta/Elev= 30
  4649.6  478.26  4662.8  476.69  4704.8  474.17  4736.9  470.22  4741.9  468.46
  4784.5  464.05  4799.9  463.26  4826.1  458.79  4846.6  457.25  4898.4  455.34
  4931.2  455.23  4952.8  448.82  4983.8  450.03    4990  446.95  4997.6  446.13
    5010  446.95    5012  448.52  5012.2  449.46  5030.4  449.38  5079.1  452.87
  5098.1  455.17    5121  459.94  5158.8  462.89  5163.4   465.3  5167.5  467.45
  5185.7  470.63  5213.7   471.6  5250.2  474.64  5309.9   472.7    5325  473.65
#Mann= 4 ,-1 , 0
  4649.6     .12       0  4983.8    .065       0  5012.2     .12       0
  5163.4     .11       0
Bank Sta=4983.8,5012.2
XS Rating Curve= 0 ,0
Exp/Cntr=0.3,0.1

Chan Stop Cuts=-1
Use User Specified Reach Order=0
Composite Channel Slope=5