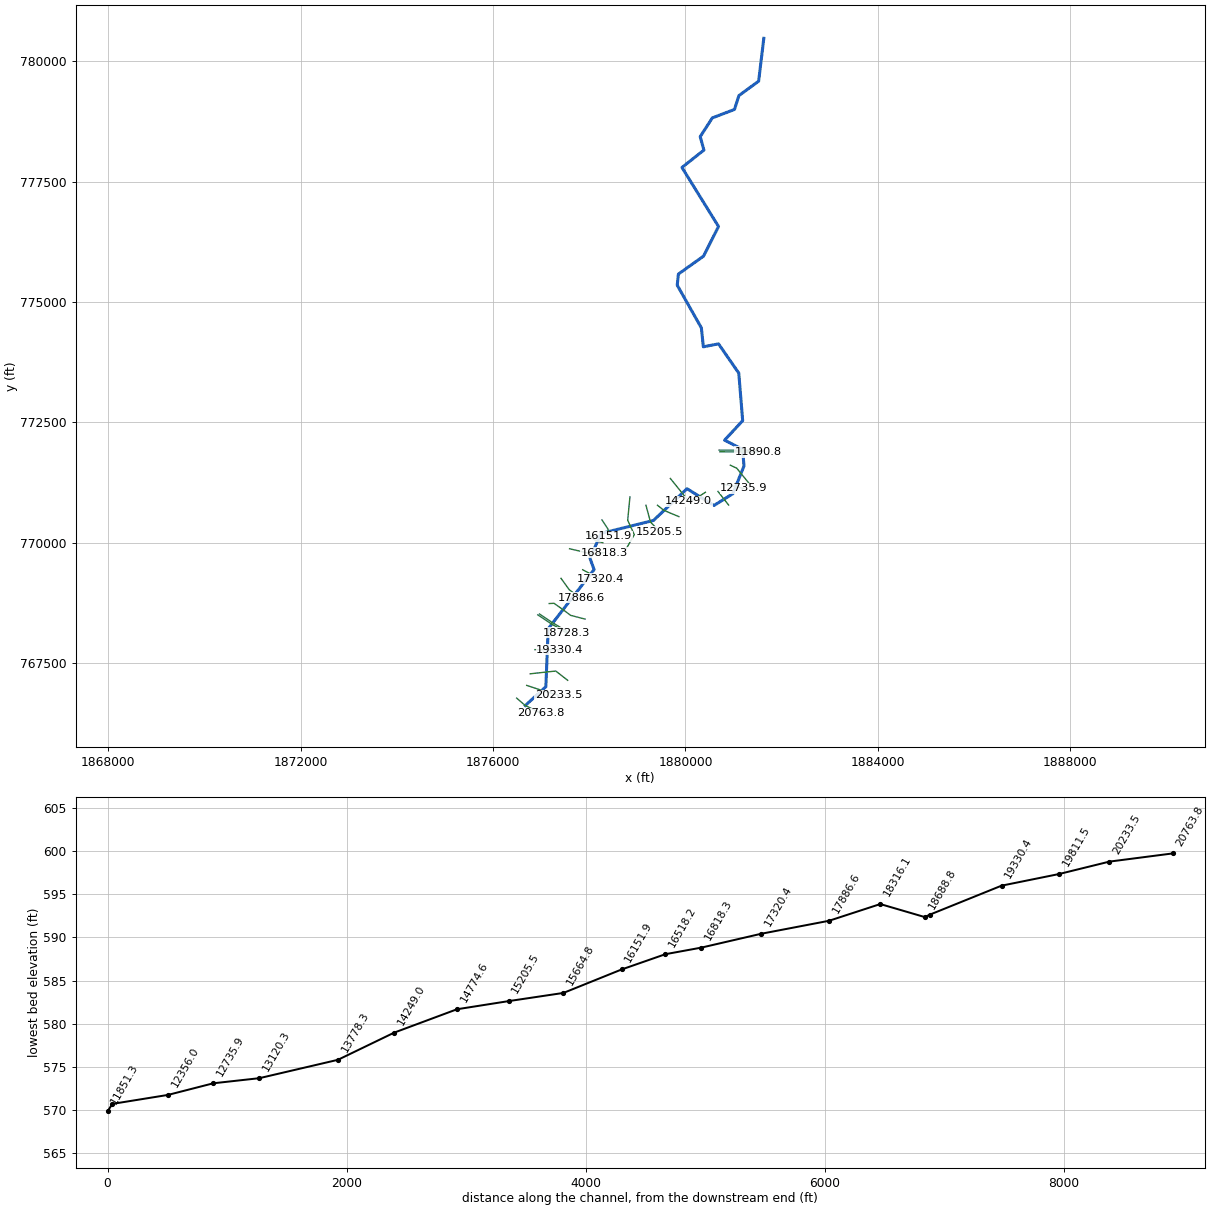
--- REEDY BRANCH.PRJ (project) ---

Proj Title=Reedy Branch
Current Plan=p01
Default Exp/Contr=0.3,0.1
English Units
Geom File=g01
Flow File=f01
Plan File=p01
Y Axis Title=Elevation
X Axis Title(PF)=Main Channel Distance
X Axis Title(XS)=Station
BEGIN DESCRIPTION:
REEDY BRANCH
NCFPM
Limited Detail Floodway Model
1% Event
Filename:  N:\NC_flood\60273\Approximates\Eng\Haw-Big_Alamance\Eng\Reedy Branch\Reedy Branch.prj
END DESCRIPTION:
DSS Export Rating Curves= 0
DSS Export Rating Curve Sorted= 0
DSS Export Volume Flow Curves= 0
DXF OffsetX= 0
DXF OffsetY= 0
DXF ScaleX= 1
DXF ScaleY= 10

--- REEDY BRANCH.p01 (plan) ---

Plan Title=100-Year-Single
Program Version=3.10
Short Identifier=Plan01
Geom File=g01
Flow File=f01
Subcritical Flow
K Sum by GR= 0
Std Step Tol= 0.01
Critical Tol= 0.01
Num of Std Step Trials= 20
Max Error Tol= 0.3
Flow Tol Ratio= 0.001
Split Flow NTrial= 30
Split Flow Tol= 0.02
Split Flow Ratio= 0.02
Log Output Level= 0
Friction Slope Method= 1
Unsteady Friction Slope Method= 2
Parabolic Critical Depth
Global Vel Dist= 0 , 0 , 0
Global Log Level= 0
CheckData=True
Encroach Param=-1 ,0,0, 2
Encroach River=Reedy Branch
Encroach Reach=Reach - 1
Encroach Node=20763.8
       1    4970    5060
Encroach Node=20233.5
       1 4879.21 5081.94
Encroach Node=19811.5
       1 4967.08 5076.97
Encroach Node=19330.4
       1 4915.88    5075
Encroach Node=18728.3
       1    4976    5025
Encroach Node=18708.5
       1 4980.04 5014.87
Encroach Node=18688.8
       1 4980.04 5014.87
Encroach Node=18316.1
       1    4830    5075
Encroach Node=17886.6
       1    4820    5075
Encroach Node=17320.4
       1 4980.23 5056.28
Encroach Node=16818.3
       1 4963.66 5069.94
Encroach Node=16518.2
       1 4959.07 5033.86
Encroach Node=16151.9
       1 4943.58 5025.15
Encroach Node=15664.8
       1 4917.96 5036.82
Encroach Node=15205.5
       1  4909.6 5041.88
Encroach Node=14774.6
       1 4928.28 5016.22
Encroach Node=14249.0
       1 4926.82 5066.85
Encroach Node=13778.3
       1 4958.41 5027.56
Encroach Node=13120.3
       1 4941.51 5031.32
Encroach Node=12735.9
       1 4947.35 5025.52
Encroach Node=12356.0
       1 4950.84 5058.72
Encroach Node=11890.8
       1    4955  5011.5
Encroach Node=11871.0
       1    4955  5011.5
Encroach Node=11851.3
       1    4955  5011.5
Encroach Node=11422.6
       1 4964.41 5036.36
Encroach Node=10877.6
       1 4964.42 5041.41
Encroach Node=10395.2
       1 4961.11 5027.14
Encroach Node=9948.7
       1  4976.8 5033.02
Encroach Node=9597.4
       1  4949.9 5040.29
Encroach Node=9058.2
       1 4979.68 5032.91
Encroach Node=8494.1
       1  4966.2 5036.61
Encroach Node=8172.3
       1 4979.55 5026.64
Encroach Node=7531.1
       1 4957.02 5027.34
Encroach Node=6996.6
       1 4985.86 5059.72
Encroach Node=6604.3
       1 4960.27 5039.32
Encroach Node=6140.3
       1 4944.62 5033.72
Encroach Node=5694.3
       1 4927.77 5040.18
Encroach Node=5094.3
       1  4995.8 5069.52
Encroach Node=4549.9
       1  4984.5  5015.5
Encroach Node=4507.9
       4      .7
Encroach Node=4465.9
       1  4984.5  5015.5
Encroach Node=4253.3
       1 4954.41 5036.29
Encroach Node=3699.0
       1 4974.36 5028.44
Encroach Node=3101.3
       1 4946.41 5044.99
Encroach Node=2780.3
       1 4948.51  5033.9
Encroach Node=2460.3
       1    4950    5070
Encroach Node=2210.8
       1    4935    5010
Encroach Node=1943.6
       1    4950    5023
Encroach Node=1923.8
       1    4950    5023
Encroach Node=1904.1
       1    4950    5023
Encroach Node=1505.2
       1 4987.55    5040
Encroach Node=872.5
       1    4900 5016.77
Encroach Node=532.5
       1 4993.44 5083.63
Encroach Node=167.0
       1 4992.33 5064.66
Computation Interval=1HOUR
Output Interval=1HOUR
Run HTab= 0
Run UNet= 0
Run PostProcess= 0
UNET Theta= 1
UNET Theta Warmup= 1
UNET ZTol= 0.02
UNET ZSATol= 0.05
UNET MxIter= 20
UNET MaxInSteps= 1
UNET DtIC= 0
UNET DtMin= 0
UNET MaxCRTS= 20
UNET WFStab= 2
UNET SFStab= 1
UNET WFX= 1
UNET SFX= 1
UNET DSS MLevel= 4
UNET Convert EG Bridges=-1
UNET Use Existing IB Tables=-1
UNET Froude Reduction=False
UNET Froude Limit= 1
UNET Froude Power= 10
Instantaneous Interval=1HOUR
Write IC File= 0
Echo Input=False
Echo Output=False
Write Detailed= 0

--- REEDY BRANCH.f01 (steady flow) ---

Flow Title= 100-Year-Single
Program Version=3.10
Number of Profiles= 2
Profile Names=100-Year,AFW
River Rch & RM=Reedy Branch,Reach - 1       ,20763.8
     944     944
River Rch & RM=Reedy Branch,Reach - 1       ,19330.4
    1350    1350
River Rch & RM=Reedy Branch,Reach - 1       ,7531.1
    1700    1700
River Rch & RM=Reedy Branch,Reach - 1       ,872.5
    1860    1860
Boundary for River Rch & Prof#=Reedy Branch,Reach - 1       , 1
Up Type= 0
Dn Type= 3
Dn Slope=0.0067
DSS Import GetInterval= 0
DSS Import GetPeak= 0
DSS Import FillOption= 0

--- REEDY BRANCH.g01 (geometry) ---

Geom Title=Geom 01 by CodeH2 for Windows
Program Version=3.10

River Reach=Reedy Branch    ,Reach - 1
Reach XY= 30
      1876669.71       766619.28      1877096.37       767009.25
      1877145.25       768213.56        1878099.       769442.44
      1878013.37       769680.81      1878245.75       770194.37
      1879333.87       770463.38      1880030.87       771123.63
      1880593.25       770775.19      1880984.62       771019.75
      1881216.88       771594.38      1881186.38       771942.88
      1880812.62       772131.88      1881189.25       772536.94
      1881108.25       773525.25        1880687.       774132.81
      1880371.13       774072.06      1880330.62         774465.
      1879828.25       775352.06      1879852.63       775582.94
      1880375.13       775955.62        1880687.       776571.31
      1879926.62       777798.62      1880383.25       778159.31
      1880306.13       778438.62      1880558.37       778828.44
        1881019.       779003.56      1881110.75       779291.19
      1881521.38       779591.38      1881628.63       780481.25

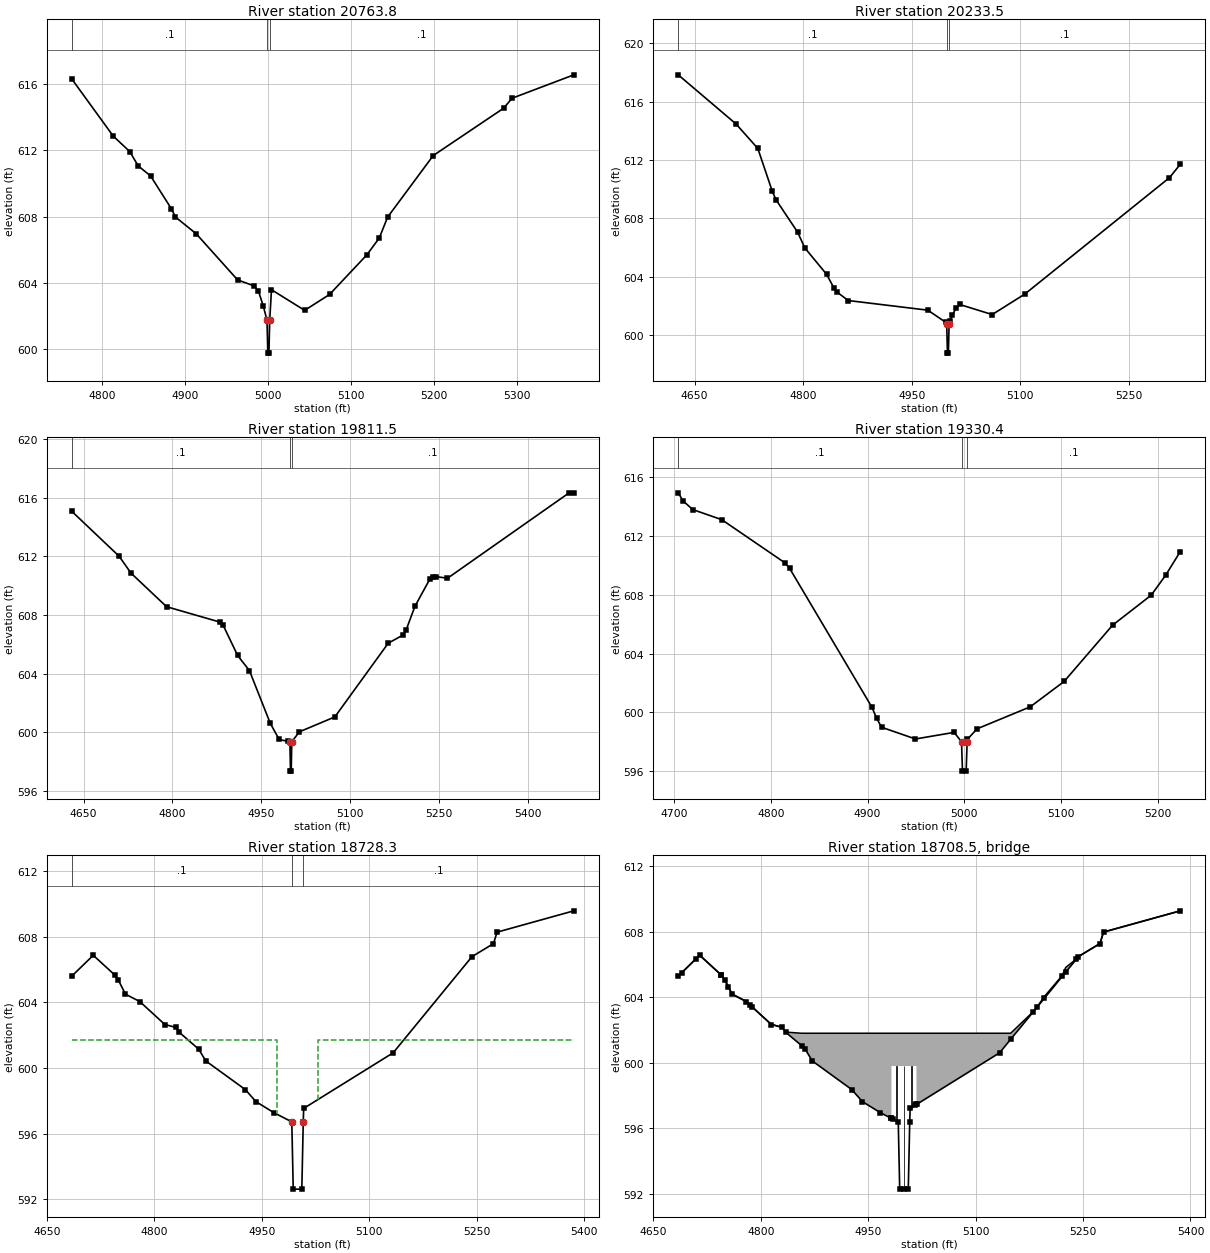
Type RM Length L Ch R = 1 ,20763.8 ,530.3,530.3,530.3
BEGIN DESCRIPTION:
Reedy Branch 42.0
END DESCRIPTION:
XS GIS Cut Line= 3
      1876489.07       766772.42      1876664.14       766622.08
      1876999.47       766455.14
#Sta/Elev= 26
    4763  616.33    4813  612.87    4833  611.93    4843  611.07    4858  610.46
    4883  608.48    4888  607.97    4913  606.96    4963  604.16    4983   603.8
    4988   603.5  4993.8   602.6  4998.4  601.73  4999.4  599.73  5000.7  599.73
  5001.7  601.73  5003.8  603.57  5043.8  602.32  5073.8  603.28  5118.8  605.68
  5133.8   606.7  5143.8  607.96  5198.8  611.69  5283.8  614.56  5293.8  615.16
  5368.4  616.58
#Mann= 3 , 1 , 0
    4763      .1       0  4998.4     .05       0  5001.7      .1       0
Bank Sta=4998.4,5001.7
XS Rating Curve= 0
Exp/Cntr=0.3,0.1

Type RM Length L Ch R = 1 ,20233.5 ,422,422,422
BEGIN DESCRIPTION:
Reedy Branch 41.0
END DESCRIPTION:
XS GIS Cut Line= 3
      1876697.85       767036.82      1877057.81       766918.29
      1877360.99        766832.7
#Sta/Elev= 25
  4627.3  617.83  4707.3  614.46  4737.3  612.79  4757.3  609.86  4762.3  609.29
  4792.3  607.06  4802.3  605.98  4832.3  604.18  4842.3  603.26  4847.3  602.94
  4862.3  602.38  4972.3  601.72  4997.3  600.88  4998.4  600.78  4999.4  598.78
  5000.7  598.78  5001.7  600.78  5002.3  600.99  5006.3  601.36  5011.3  601.88
  5016.3  602.11  5061.3  601.42  5106.3  602.82  5306.3  610.79  5321.3  611.71
#Mann= 3 , 1 , 0
  4627.3      .1       0  4998.4     .05       0  5001.7      .1       0
Bank Sta=4998.4,5001.7
XS Rating Curve= 0
Exp/Cntr=0.3,0.1

Type RM Length L Ch R = 1 ,19811.5 ,481.1,481.1,481.1
BEGIN DESCRIPTION:
Reedy Branch 40.0
END DESCRIPTION:
XS GIS Cut Line= 4
      1876771.56       767277.39      1877153.36        767319.6
      1877302.72       767334.31      1877550.34       767142.34
#Sta/Elev= 27
  4630.2  615.07  4710.2     612  4730.2  610.85  4790.2  608.56  4880.2  607.51
  4885.2  607.34  4910.2  605.23  4930.2  604.19  4965.2  600.61  4980.2   599.5
  4995.2  599.37  4998.4  599.34  4999.4  597.34  5000.6  597.34  5001.6  599.34
  5014.3  600.02  5074.3  601.04  5164.4  606.07  5189.4  606.63  5194.4  606.95
  5209.4  608.58  5234.4  610.43  5239.4  610.61  5244.4  610.62  5264.4   610.5
  5469.4  616.32  5477.7  616.33
#Mann= 3 , 1 , 0
  4630.2      .1       0  4998.4     .05       0  5001.6      .1       0
Bank Sta=4998.4,5001.6
XS Rating Curve= 0
Exp/Cntr=0.3,0.1

Type RM Length L Ch R = 1 ,19330.4 ,602.15,602.15,602.15
BEGIN DESCRIPTION:
Reedy Branch 39.0
END DESCRIPTION:
XS GIS Cut Line= 3
      1876867.47       767779.19      1877161.01       767778.24
      1877386.06       767777.33
#Sta/Elev= 23
  4704.5  614.95  4709.5   614.4  4719.5  613.81  4749.5  613.12  4814.5  610.19
  4819.5  609.81  4904.5  600.35  4909.5  599.58  4914.5  598.98  4949.5  598.18
  4989.5  598.63  4997.1  597.99  4998.1  595.99  5001.9  595.99  5002.9  597.99
  5003.1  598.15  5013.1  598.87  5068.1  600.37  5103.1   602.1  5153.1  605.93
  5193.1  607.98  5208.1  609.35  5223.1  610.95
#Mann= 3 , 1 , 0
  4704.5      .1       0  4997.1     .05       0  5002.9      .1       0
Bank Sta=4997.1,5002.9
XS Rating Curve= 0
Exp/Cntr=0.5,0.3

Type RM Length L Ch R = 1 ,18728.3 ,39.5,39.5,39.5
BEGIN DESCRIPTION:
Upstream Section of Bridge/Culvert/Weir
END DESCRIPTION:
XS GIS Cut Line= 3
      1876928.18       768502.79      1877191.11       768327.43
      1877521.82       768130.39
#Sta/Elev= 24
  4684.8   605.6  4714.8  606.87  4744.8  605.67  4749.8  605.36  4759.8   604.5
  4779.8  604.05  4814.8  602.65  4829.8  602.48  4834.8  602.18    4862  601.15
    4872  600.43    4927  598.69    4942  597.95    4967  597.28    4992  596.72
    4994  592.62    5006  592.62    5008  596.72  5008.6  597.54  5133.6  600.93
  5243.6  606.79  5273.6  607.58  5278.6  608.28  5385.8  609.58
#Mann= 3 , 1 , 0
  4684.8      .1       0    4992     .05       0    5008      .1       0
#XS Ineff= 2 , 0
       0    4972   601.7    5028       0   601.7
Permanent Ineff=
       F       F
Bank Sta=4992,5008
XS Rating Curve= 0
Exp/Cntr=0.5,0.3

Type RM Length L Ch R = 3 ,18708.5 ,,,
BEGIN DESCRIPTION:
Reedy Branch - Clark Rd
Structure ID: NCF-0082
Approximate Survey Structure
END DESCRIPTION:
Bridge Culvert--1,0,-1,-1, 0
Deck Dist Width WeirC Skew NumUp NumDn MinLoCord MaxHiCord MaxSubmerge Is_Ogee
10,19.5,2.6,0, 45, 45, , , 0.95, 0, 1,1,,
  4684.8  4689.8  4709.8  4714.8  4744.7  4744.8  4749.8  4754.8  4759.8  4779.8
  4784.8  4787.7  4814.8  4829.8  4834.8    4857    4862    4872    4927    4942
    4967 4982.41  4982.5  4984.2    4992    4994    5000    5006    5008  5008.6
  5015.7 5017.39  5017.5  5133.6  5148.9  5180.8  5185.8  5195.8  5220.8  5225.8
  5240.8  5243.6  5273.6  5278.6  5385.8
  605.28   605.5  606.35  606.56  605.36  605.36  605.05  604.65   604.2  603.74
  603.54  603.42  602.34  602.17  601.87   601.8   601.8   601.8   601.8   601.8
   601.8   601.8   601.8   601.8   601.8   601.8   601.8   601.8   601.8   601.8
   601.8   601.8   601.8   601.8   601.8  603.13   603.4  604.03  605.31  605.81
  606.33  606.48  607.27  607.97  609.26
  605.28  605.49  606.34  606.55  605.35  605.35  605.04  604.61  604.18  603.73
  603.53  603.41  602.33  602.16  601.86  601.05  600.83  600.11  598.37  597.63
  596.96  596.61   599.8   599.8   599.8   599.8   599.8   599.8   599.8   599.8
   599.8   599.8  597.46  600.61  601.43  603.12  603.39  603.92  605.26  605.52
  606.32  606.47  607.26  607.96  609.26
  4684.8  4689.8  4709.8  4714.8  4744.7  4744.8  4749.8  4754.8  4759.8  4779.8
  4784.8  4787.7  4814.8  4829.8  4834.8    4857    4862    4872    4927    4942
    4967 4982.41  4982.5  4984.2    4992    4994    5000    5006    5008  5008.6
  5015.7 5017.39  5017.5  5133.6  5148.9  5180.8  5185.8  5195.8  5220.8  5225.8
  5240.8  5243.6  5273.6  5278.6  5385.8
  605.28   605.5  606.35  606.56  605.36  605.36  605.05  604.65   604.2  603.74
  603.54  603.42  602.34  602.17  601.87   601.8   601.8   601.8   601.8   601.8
   601.8   601.8   601.8   601.8   601.8   601.8   601.8   601.8   601.8   601.8
   601.8   601.8   601.8   601.8   601.8  603.13   603.4  604.03  605.31  605.81
  606.33  606.48  607.27  607.97  609.26
  605.03  605.24  606.09   606.3   605.1   605.1  604.79  604.36  603.93  603.48
  603.28  603.16  602.08  601.91  601.61   600.8  600.58  599.86  598.12  597.38
  596.71  596.36  599.55  599.55  599.55  599.55  599.55  599.55  599.55  599.55
  599.55  599.55  597.21  600.36  601.18  602.87  603.14  603.67  605.01  605.27
  606.07  606.22  607.01  607.71  609.01
Pier Skew, UpSta & Num, DnSta & Num=  ,4989.5, 2 ,4989.5, 2 , 0 , 0 , 0 ,,
       1       1
  595.44   600.8
       1       1
  595.19  600.55
Pier Skew, UpSta & Num, DnSta & Num=  ,5000, 2 ,5000, 2 , 0 , 0 , 0 ,,
       1       1
   591.3   600.8
       1       1
  591.05  600.55
Pier Skew, UpSta & Num, DnSta & Num=  ,5010.5, 2 ,5010.5, 2 , 0 , 0 , 0 ,,
       1       1
  596.26   600.8
       1       1
  596.01  600.55
Abutment Skew #Up #Dn= , 2 , 2
  4982.3  4984.2
   599.8  596.57
  4982.3  4984.2
  599.55  596.32
Abutment Skew #Up #Dn= , 2 , 2
  5015.7 5017.59
  597.41   599.8
  5015.7 5017.59
  597.16  599.55
BR Coef= 1 , 1 , 0 ,1.25, 0 ,,,0.8,0,2,0,
WSPro=,,,, 1 ,,,, 0 ,,,, 0 ,,,,-1 ,-1 ,-1 , 0 , 0 , 0 , 0 , 0
BR U #Sta/Elev= 45
  4684.8  605.28  4689.8  605.49  4709.8  606.34  4714.8  606.55  4744.7  605.35
  4744.8  605.35  4749.8  605.04  4754.8  604.61  4759.8  604.18  4779.8  603.73
  4784.8  603.53  4787.7  603.41  4814.8  602.33  4829.8  602.16  4834.8  601.86
    4857  601.05    4862  600.83    4872  600.11    4927  598.37    4942  597.63
    4967  596.96 4982.41  596.61  4982.5  596.61  4984.2  596.57    4992   596.4
    4994   592.3    5000   592.3    5006   592.3    5008   596.4  5008.6  597.22
  5015.7  597.41 5017.39  597.46  5017.5  597.46  5133.6  600.61  5148.9  601.43
  5180.8  603.12  5185.8  603.39  5195.8  603.92  5220.8  605.26  5225.8  605.52
  5240.8  606.32  5243.6  606.47  5273.6  607.26  5278.6  607.96  5385.8  609.26
BR U #Mann= 3
  4684.8      .1    4992     .05    5008      .1
BR U Banks=4992,5008
BR D #Sta/Elev= 45
  4684.8  605.03  4689.8  605.24  4709.8  606.09  4714.8   606.3  4744.7   605.1
  4744.8   605.1  4749.8  604.79  4754.8  604.36  4759.8  603.93  4779.8  603.48
  4784.8  603.28  4787.7  603.16  4814.8  602.08  4829.8  601.91  4834.8  601.61
    4857   600.8    4862  600.58    4872  599.86    4927  598.12    4942  597.38
    4967  596.71 4982.41  596.36  4982.5  596.36  4984.2  596.32    4992  596.15
    4994  592.05    5000  592.05    5006  592.05    5008  596.15  5008.6  596.97
  5015.7  597.16 5017.39  597.21  5017.5  597.21  5133.6  600.36  5148.9  601.18
  5180.8  602.87  5185.8  603.14  5195.8  603.67  5220.8  605.01  5225.8  605.27
  5240.8  606.07  5243.6  606.22  5273.6  607.01  5278.6  607.71  5385.8  609.01
BR D #Mann= 3
  4684.8      .1    4992     .05    5008      .1
BR D Banks=4992,5008
BC Design=,, 0 ,, 0 ,,,,,,
BC HTab HWMax=609.58

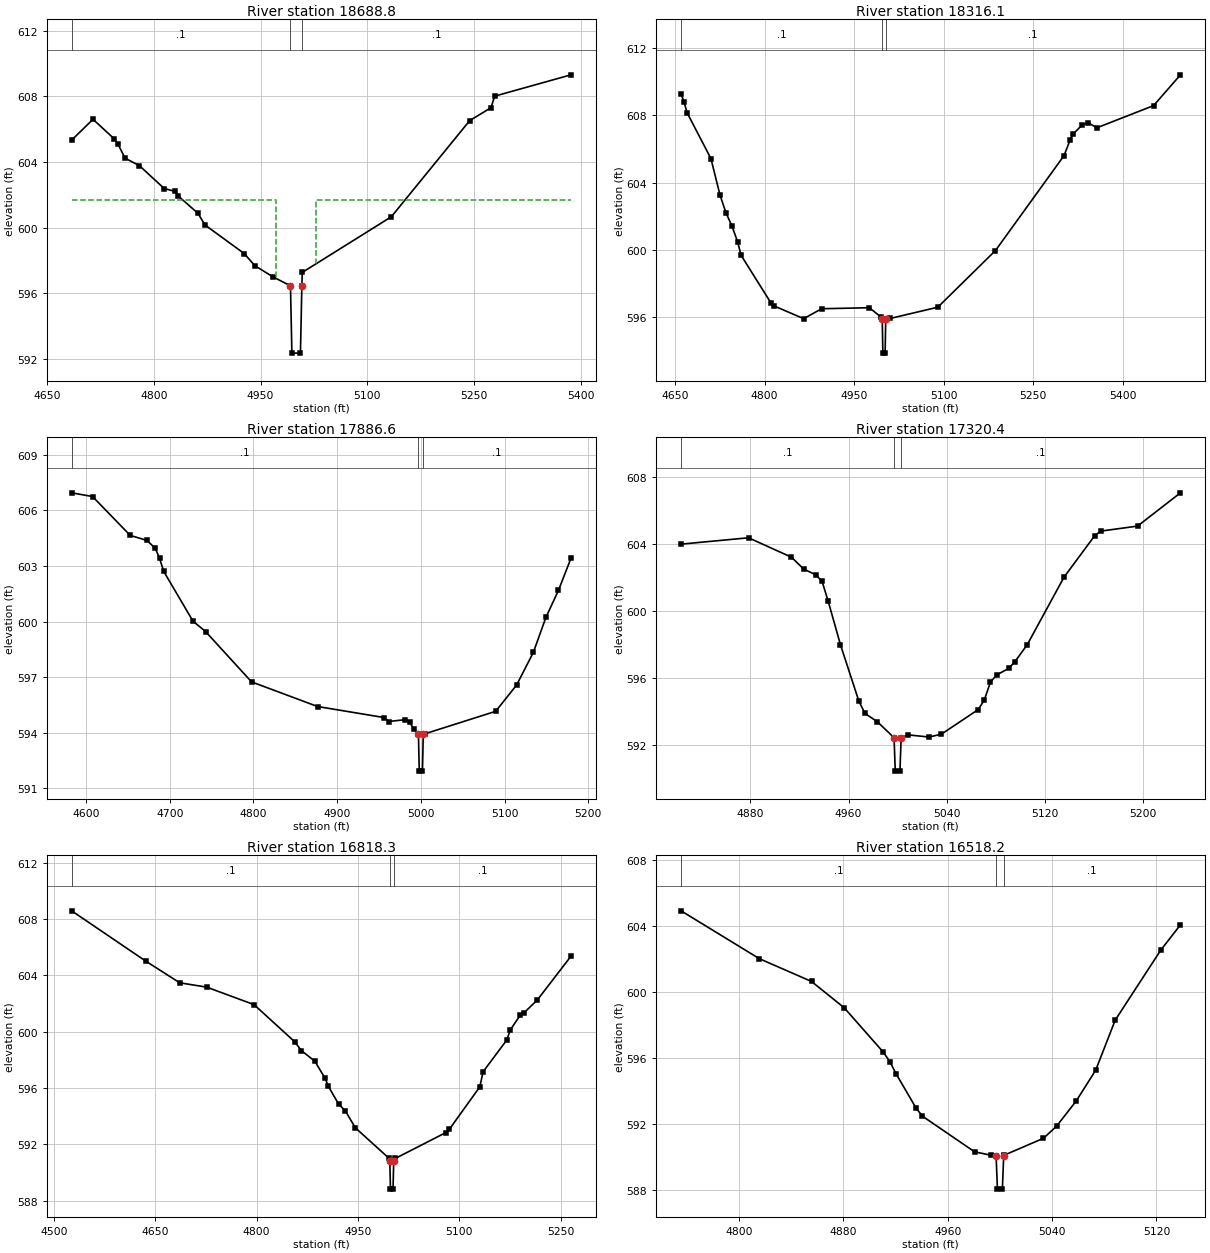
Type RM Length L Ch R = 1 ,18688.8 ,372.65,372.65,372.65
BEGIN DESCRIPTION:
Downstream Section of Bridge/Culvert/Weir
END DESCRIPTION:
XS GIS Cut Line= 3
      1876963.51       768520.44      1877226.45       768345.09
      1877557.15       768148.04
#Sta/Elev= 24
  4684.8  605.33  4714.8   606.6  4744.8   605.4  4749.8  605.09  4759.8  604.23
  4779.8  603.78  4814.8  602.38  4829.8  602.21  4834.8  601.91    4862  600.88
    4872  600.16    4927  598.42    4942  597.68    4967  597.01    4992  596.45
    4994  592.35    5006  592.35    5008  596.45  5008.6  597.27  5133.6  600.66
  5243.6  606.52  5273.6  607.31  5278.6  608.01  5385.8  609.31
#Mann= 3 , 1 , 0
  4684.8      .1       0    4992     .05       0    5008      .1       0
#XS Ineff= 2 , 0
       0    4972   601.7    5028       0   601.7
Permanent Ineff=
       F       F
Bank Sta=4992,5008
XS Rating Curve= 0
Exp/Cntr=0.5,0.3

Type RM Length L Ch R = 1 ,18316.1 ,429.5,429.5,429.5
BEGIN DESCRIPTION:
Reedy Branch 38.0
END DESCRIPTION:
XS GIS Cut Line= 5
      1877166.17       768737.31      1877266.55       768742.09
      1877470.59       768598.07      1877611.54       768491.69
      1877911.75       768414.55
#Sta/Elev= 30
    4660  609.27    4665  608.79    4670  608.16    4710  605.43    4725  603.29
    4735  602.22    4745  601.44    4755  600.45  4760.5  599.68  4810.5  596.85
  4815.5  596.67  4865.5  595.91  4895.5   596.5  4975.5  596.56  4995.5  595.99
  4997.1  595.86  4998.1  593.86  5001.9  593.86  5002.9  595.86  5010.2  595.92
  5090.2  596.59  5186.8  599.96  5301.8  605.61  5311.8  606.53  5316.8  606.88
  5331.8  607.42  5341.8  607.57  5356.8  607.26  5451.8  608.58  5496.8  610.41
#Mann= 3 , 1 , 0
    4660      .1       0  4997.1     .05       0  5002.9      .1       0
Bank Sta=4997.1,5002.9
XS Rating Curve= 0
Exp/Cntr=0.3,0.1

Type RM Length L Ch R = 1 ,17886.6 ,566.2,566.2,566.2
BEGIN DESCRIPTION:
Reedy Branch 37.0
END DESCRIPTION:
XS GIS Cut Line= 4
      1877411.87       769260.98      1877584.03       769022.95
      1877682.71       768949.69      1877836.47       768856.04
#Sta/Elev= 27
  4582.7  606.95  4607.7  606.75  4652.7  604.65  4672.7  604.38  4682.7  603.95
  4687.7  603.42  4692.7  602.71  4727.7  600.02  4742.7  599.46  4797.7  596.74
  4876.5  595.41  4956.5  594.81  4961.5   594.6  4981.5   594.7  4986.5  594.56
  4991.5   594.2  4997.1  593.92  4998.1  591.92  5001.9  591.92  5002.9  593.92
  5004.4  593.93  5089.4  595.15  5114.4  596.57  5134.4  598.33  5149.4  600.22
  5164.4  601.68  5179.4  603.42
#Mann= 3 , 1 , 0
  4582.7      .1       0  4997.1     .05       0  5002.9      .1       0
Bank Sta=4997.1,5002.9
XS Rating Curve= 0
Exp/Cntr=0.3,0.1

Type RM Length L Ch R = 1 ,17320.4 ,502.1,502.1,502.1
BEGIN DESCRIPTION:
Reedy Branch 36.0
END DESCRIPTION:
XS GIS Cut Line= 3
      1877863.36       769439.27      1878028.61       769351.01
      1878223.85       769249.71
#Sta/Elev= 30
  4823.4     604  4878.4  604.38  4913.4  603.22  4923.4  602.51  4933.4  602.16
  4938.4  601.77  4943.4  600.58  4953.4  597.98  4968.4  594.61  4973.4  593.87
  4983.4  593.38  4997.1  592.42  4998.1  590.42  5001.9  590.42  5002.9  592.42
  5008.4  592.59  5025.7  592.46  5035.7  592.63  5065.7   594.1  5070.7  594.67
  5075.7  595.74  5080.7  596.17  5090.7  596.57  5095.7  596.97  5105.7  597.98
  5135.7  602.02  5160.7   604.5  5165.7  604.78  5195.7  605.08  5230.7  607.07
#Mann= 3 , 1 , 0
  4823.4      .1       0  4997.1     .05       0  5002.9      .1       0
Bank Sta=4997.1,5002.9
XS Rating Curve= 0
Exp/Cntr=0.3,0.1

Type RM Length L Ch R = 1 ,16818.3 ,300.1,300.1,300.1
BEGIN DESCRIPTION:
Reedy Branch 35.0
END DESCRIPTION:
XS GIS Cut Line= 3
      1877589.24       769876.33      1878055.36        769765.7
      1878313.68       769795.56
#Sta/Elev= 29
  4526.2  608.57  4636.2  604.99  4686.2  603.46  4726.2  603.15  4796.2  601.91
  4856.2  599.28  4866.2  598.65  4886.2  597.89  4901.2  596.69  4906.2  596.11
  4921.2  594.86  4931.2  594.37  4946.2  593.16  4996.2  590.99  4997.1  590.81
  4998.1  588.81  5001.9  588.81  5002.9  590.81  5005.3  590.99  5080.3  592.83
  5085.3  593.06  5130.3  596.07  5135.3  597.15  5170.3   599.4  5175.3   600.1
  5190.3  601.17  5195.3  601.31  5215.3  602.23  5265.3  605.35
#Mann= 3 , 1 , 0
  4526.2      .1       0  4997.1     .05       0  5002.9      .1       0
Bank Sta=4997.1,5002.9
XS Rating Curve= 0
Exp/Cntr=0.3,0.1

Type RM Length L Ch R = 1 ,16518.2 ,366.3,366.3,366.3
BEGIN DESCRIPTION:
Reedy Branch 34.0
END DESCRIPTION:
XS GIS Cut Line= 3
      1877957.14       770187.31      1878141.36       770037.06
      1878281.82       770000.78
#Sta/Elev= 23
  4755.6  604.91  4815.6  602.01  4855.6  600.63  4880.6  599.04  4910.6  596.35
  4915.6  595.78  4920.6  595.01  4935.6  592.98  4940.6  592.47  4980.6  590.31
  4993.4   590.1  4997.1  590.05  4998.1  588.05  5001.9  588.05  5002.9  590.05
  5003.4  590.11  5033.4  591.13  5043.4  591.86  5058.4  593.38  5073.4  595.25
  5088.4  598.29  5123.4  602.54  5138.4  604.06
#Mann= 3 , 1 , 0
  4755.6      .1       0  4997.1     .05       0  5002.9      .1       0
Bank Sta=4997.1,5002.9
XS Rating Curve= 0
Exp/Cntr=0.3,0.1

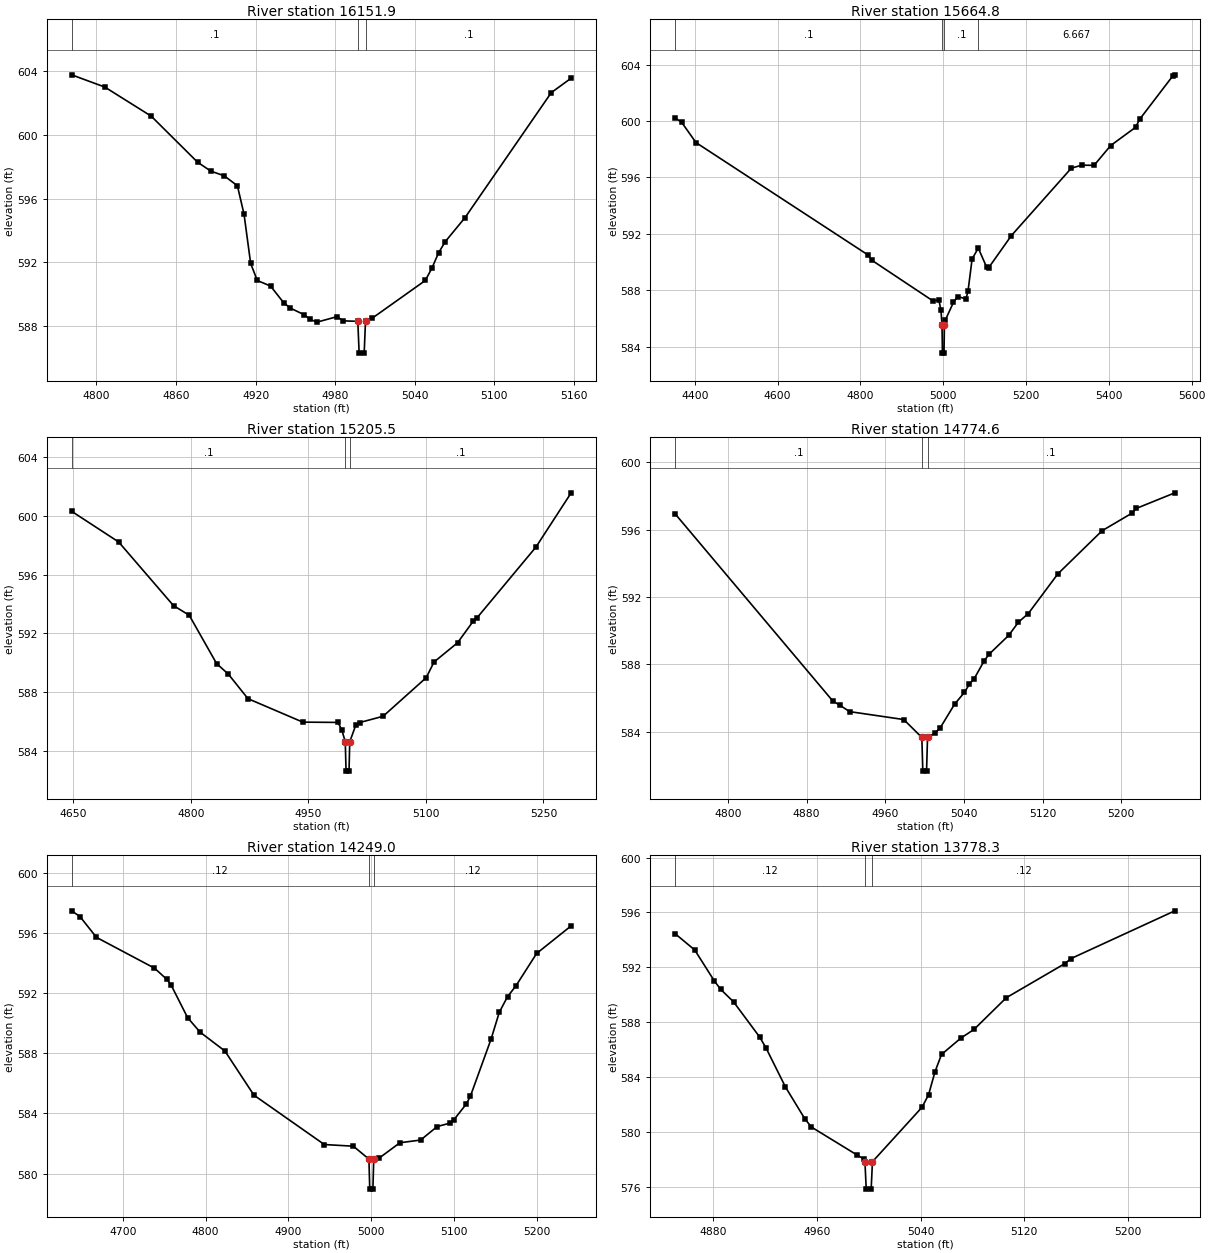
Type RM Length L Ch R = 1 ,16151.9 ,487.1,487.1,487.1
BEGIN DESCRIPTION:
Reedy Branch 33.0
END DESCRIPTION:
XS GIS Cut Line= 3
       1878263.4       770474.98      1878387.88       770285.49
      1878405.41       770136.53
#Sta/Elev= 30
  4781.3  603.79  4806.3  603.02  4841.3  601.19  4876.3  598.29  4886.3  597.73
  4896.3  597.44  4906.3  596.81  4911.3  595.02  4916.3  591.92  4921.3  590.85
  4931.3   590.5  4941.3  589.44  4946.3  589.11  4956.3  588.71  4961.3   588.4
  4966.3  588.23  4981.3  588.57  4986.3  588.31  4997.1  588.28  4998.1  586.28
  5001.9  586.28  5002.9  588.28    5008  588.48    5048  590.85    5053  591.63
    5058  592.59    5063  593.29    5078  594.81    5143  602.67    5158  603.58
#Mann= 3 , 1 , 0
  4781.3      .1       0  4997.1     .05       0  5002.9      .1       0
Bank Sta=4997.1,5002.9
XS Rating Curve= 0
Exp/Cntr=0.3,0.1

Type RM Length L Ch R = 1 ,15664.8 ,459.3,459.3,459.3
BEGIN DESCRIPTION:
Reedy Branch 32.0
END DESCRIPTION:
XS GIS Cut Line= 5
      1878845.01       770953.36      1878798.14       770468.98
      1878861.81       770327.53      1878936.16        770169.5
      1878742.29       769831.06
#Sta/Elev= 30
    4353  600.21    4368  599.92    4403  598.47    4818  590.52    4828  590.13
  4974.6  587.27  4989.6  587.32  4994.6  586.58  4997.1  585.56  4998.1  583.56
  5001.9  583.56  5002.9  585.56  5004.8  585.88  5024.8  587.16  5034.8  587.57
  5054.8   587.4  5059.8  587.93  5069.8  590.23  5084.7     591  5104.8  589.65
  5109.8  589.61  5164.8  591.89  5309.4  596.66  5334.4  596.87  5364.4  596.86
  5404.4  598.26  5464.4  599.55  5474.4  600.12  5554.4  603.19  5559.4  603.27
#Mann= 4 , 1 , 0
    4353      .1       0  4997.1     .05       0  5002.9      .1       0
  5084.7   6.667       0
Bank Sta=4997.1,5002.9
XS Rating Curve= 0
Exp/Cntr=0.3,0.1

Type RM Length L Ch R = 1 ,15205.5 ,430.9,430.9,430.9
BEGIN DESCRIPTION:
Reedy Branch 31.0
END DESCRIPTION:
XS GIS Cut Line= 3
      1879178.35       770778.88      1879272.67       770428.82
      1879466.46       770233.82
#Sta/Elev= 25
  4647.9  600.32  4707.9  598.23  4777.9  593.89  4797.9  593.24  4832.9  589.94
  4847.9  589.22  4872.9  587.55  4942.9  585.95  4987.9  585.93  4992.9  585.38
  4997.1  584.61  4998.1  582.61  5001.9  582.61  5002.8  584.61  5002.9  584.62
  5010.4  585.73  5015.4  585.92  5045.4  586.35  5100.4  588.98  5110.4  590.05
  5140.4  591.36  5160.4  592.83  5165.4  593.07  5240.4  597.88  5285.4  601.58
#Mann= 3 , 1 , 0
  4647.9      .1       0  4997.1     .05       0  5002.8      .1       0
Bank Sta=4997.1,5002.8
XS Rating Curve= 0
Exp/Cntr=0.3,0.1

Type RM Length L Ch R = 1 ,14774.6 ,525.6,525.6,525.6
BEGIN DESCRIPTION:
Reedy Branch 30.0
END DESCRIPTION:
XS GIS Cut Line= 4
      1879417.64       770779.45      1879548.47       770675.24
      1879628.12       770640.94      1879862.61       770543.19
#Sta/Elev= 25
  4746.4  596.92  4906.4  585.84  4913.7  585.58  4923.7   585.2  4978.7  584.73
  4997.1  583.67  4998.1  581.67  5001.9  581.67  5002.9  583.67  5010.4  583.93
  5015.4   584.2  5030.4  585.64  5040.4  586.34  5045.4  586.82  5050.4  587.16
  5060.4   588.2  5065.4   588.6  5085.4  589.72  5095.4  590.51  5105.4  591.02
  5135.4  593.37  5180.4  595.93  5210.4  596.96  5215.4  597.26  5254.4  598.18
#Mann= 3 , 1 , 0
  4746.4      .1       0  4997.1     .05       0  5002.9      .1       0
Bank Sta=4997.1,5002.9
XS Rating Curve= 0
Exp/Cntr=0.3,0.1

Type RM Length L Ch R = 1 ,14249.0 ,470.7,470.7,470.7
BEGIN DESCRIPTION:
Reedy Branch 29.0
END DESCRIPTION:
XS GIS Cut Line= 3
      1879685.02       771336.42       1879918.6       771047.98
       1880062.3       770866.22
#Sta/Elev= 30
  4638.3   597.5  4648.3  597.12  4668.3  595.73  4738.3  593.68  4753.3  592.93
  4758.3  592.56  4778.3  590.38  4793.3  589.42  4823.3  588.16  4858.3  585.22
  4943.3  581.93  4978.3  581.82  4997.1  580.96  4998.1  578.96  5001.9  578.96
  5002.9  580.96  5009.5  581.03  5034.5  582.05  5059.5  582.23  5079.5  583.13
  5094.5  583.35  5099.5  583.57  5114.5  584.62  5119.5  585.14  5144.5  588.95
  5154.5  590.75  5164.5  591.79  5174.5   592.5  5199.5  594.66  5241.2   596.5
#Mann= 3 , 1 , 0
  4638.3     .12       0  4997.1     .05       0  5002.9     .12       0
Bank Sta=4997.1,5002.9
XS Rating Curve= 0
Exp/Cntr=0.3,0.1

Type RM Length L Ch R = 1 ,13778.3 ,658,658,658
BEGIN DESCRIPTION:
Reedy Branch 28.0
END DESCRIPTION:
XS GIS Cut Line= 3
      1880414.97       771049.53      1880296.98       770973.45
      1880083.75       770852.78
#Sta/Elev= 26
  4850.8  594.44  4865.8  593.26  4880.8  591.02  4885.8  590.39  4895.8  589.47
  4915.8  586.92  4920.8  586.11  4935.8  583.26  4950.8  580.93  4955.8  580.34
  4991.2  578.29  4996.2  578.01  4997.1  577.81  4998.1  575.81  5001.9  575.81
  5002.9  577.81  5041.2  581.79  5046.2   582.7  5051.2  584.39  5056.2  585.64
  5071.2  586.84  5081.2  587.46  5106.2  589.78  5151.2  592.26  5156.2  592.64
  5236.2  596.12
#Mann= 3 , 1 , 0
  4850.8     .12       0  4997.1     .05       0  5002.9     .12       0
Bank Sta=4997.1,5002.9
XS Rating Curve= 0
Exp/Cntr=0.3,0.1

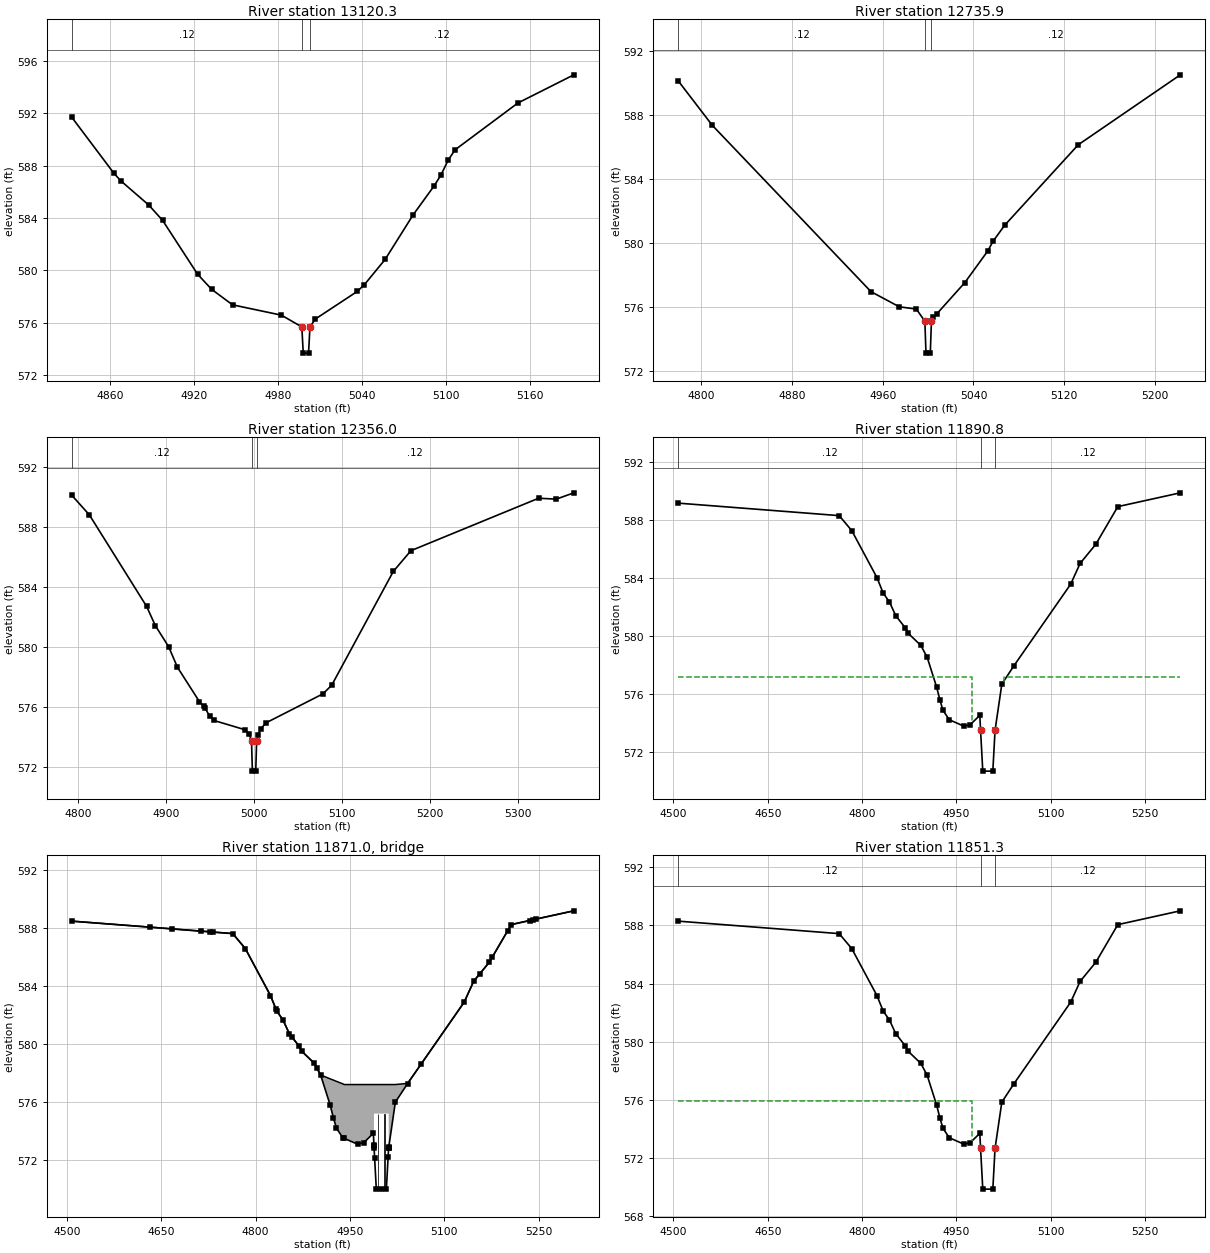
Type RM Length L Ch R = 1 ,13120.3 ,384.4,384.4,384.4
BEGIN DESCRIPTION:
Reedy Branch 27.0
END DESCRIPTION:
XS GIS Cut Line= 3
      1880675.42        771067.1      1880782.37        770929.5
      1880896.99       770784.38
#Sta/Elev= 24
  4832.5   591.7  4862.5  587.44  4867.5  586.85  4887.5     585  4897.5  583.82
  4922.5  579.71  4932.5  578.56  4947.5  577.37  4982.5  576.58  4997.1  575.68
  4998.1  573.68  5001.9  573.68  5002.9  575.68  5006.7  576.28  5036.7  578.39
  5041.7  578.89  5056.7  580.84  5076.7  584.24  5091.7  586.45  5096.7   587.3
  5101.7  588.41  5106.7  589.21  5151.7  592.79  5191.7  594.94
#Mann= 3 , 1 , 0
  4832.5     .12       0  4997.1     .05       0  5002.9     .12       0
Bank Sta=4997.1,5002.9
XS Rating Curve= 0
Exp/Cntr=0.3,0.1

Type RM Length L Ch R = 1 ,12735.9 ,379.9,379.9,379.9
BEGIN DESCRIPTION:
Reedy Branch 26.0
END DESCRIPTION:
XS GIS Cut Line= 3
      1880780.23       771216.69      1881004.05       771174.11
      1881214.22       771128.95
#Sta/Elev= 17
  4779.6  590.14  4809.6  587.36  4949.6  576.94  4974.6  575.99  4989.6  575.85
  4997.1  575.09  4998.1  573.09  5001.9  573.09  5002.9  575.09  5004.6  575.36
  5007.4  575.53  5032.4  577.51  5052.4  579.47  5057.4  580.11  5067.4  581.09
  5132.4  586.14  5222.4  590.52
#Mann= 3 , 1 , 0
  4779.6     .12       0  4997.1     .05       0  5002.9     .12       0
Bank Sta=4997.1,5002.9
XS Rating Curve= 0
Exp/Cntr=0.3,0.1

Type RM Length L Ch R = 1 ,12356.0 ,465.25,465.25,465.25
BEGIN DESCRIPTION:
Reedy Branch 25.0
END DESCRIPTION:
XS GIS Cut Line= 4
      1880931.83       771612.55       1881068.6       771547.74
      1881107.24       771497.07      1881332.64       771222.77
#Sta/Elev= 27
    4793   590.1    4813  588.79    4878   582.7    4888  581.41    4903  580.02
    4913  578.65    4938  576.36    4943  576.06  4944.4  575.93  4949.4  575.42
  4954.4  575.11  4989.4   574.5  4994.4  574.24  4997.1  573.74  4998.1  571.74
  5001.9  571.74  5002.9  573.74  5004.4  574.16  5008.1  574.57  5013.1  574.94
  5078.1  576.88  5088.1  577.45  5158.1  585.03  5178.1  586.41  5323.1   589.9
  5343.1  589.84  5363.1  590.26
#Mann= 3 , 1 , 0
    4793     .12       0  4997.1     .05       0  5002.9     .12       0
Bank Sta=4997.1,5002.9
XS Rating Curve= 0
Exp/Cntr=0.5,0.3

Type RM Length L Ch R = 1 ,11890.8 ,39.5,39.5,39.5
BEGIN DESCRIPTION:
Upstream Section of Bridge/Culvert/Weir
END DESCRIPTION:
XS GIS Cut Line= 3
        1880715.       771889.84      1881213.54       771888.36
      1881513.59       771885.75
#Sta/Elev= 29
  4507.6  589.15  4763.6  588.29  4783.6  587.26  4823.6  584.03  4833.6  582.96
  4843.6  582.34  4853.6   581.4  4868.6  580.57  4873.6  580.18  4893.6  579.35
  4903.6  578.53  4918.6  576.49  4923.6  575.63  4928.6   574.9  4938.6  574.24
  4962.3  573.79  4972.3  573.91  4987.3  574.54  4988.5   573.5    4992   570.7
    5008   570.7  5011.5   573.5  5022.3  576.69  5041.8  577.97  5131.8  583.57
  5146.8     585  5171.8  586.32  5206.8  588.91  5306.2  589.86
#Mann= 3 , 1 , 0
  4507.6     .12       0  4988.5     .05       0  5011.5     .12       0
#XS Ineff= 2 , 0
       0    4975   577.2    5025       0   577.2
Permanent Ineff=
       F       F
Bank Sta=4988.5,5011.5
XS Rating Curve= 0
Exp/Cntr=0.5,0.3

Type RM Length L Ch R = 3 ,11871.0 ,,,
BEGIN DESCRIPTION:
Reedy Branch - Quakenbush Rd 2
Structure ID: NCF-0085
Approximate Survey Structure
END DESCRIPTION:
Bridge Culvert--1,0,-1,-1, 0
Deck Dist Width WeirC Skew NumUp NumDn MinLoCord MaxHiCord MaxSubmerge Is_Ogee
10,19.5,2.6,0, 52, 52, , , 0.95, 0, 1,1,,
  4507.6  4632.6  4667.6  4712.6  4727.6  4732.6  4763.6  4783.6  4823.6  4832.6
  4833.6  4843.6  4853.6  4857.6  4868.6  4873.6  4893.6  4897.6  4903.6  4918.6
  4923.6  4928.6  4938.6  4941.2  4962.3  4972.3  4987.3 4988.21  4988.3  4988.5
  4989.3    4992    5000    5008  5010.8  5011.5 5011.69  5011.8  5022.3  5041.8
  5063.2  5131.8  5146.8  5156.2  5171.8  5176.2  5201.2  5206.8  5236.2  5241.2
  5246.2  5306.2
  588.45  588.04  587.92  587.77  587.72   587.7   587.6  586.57  583.34  582.38
  582.27  581.65  580.71  580.49  579.88  579.49  578.66  578.33  577.86  577.59
  577.51  577.42  577.25   577.2   577.2   577.2   577.2   577.2   577.2   577.2
   577.2   577.2   577.2   577.2   577.2   577.2   577.2   577.2   577.2  577.28
  578.61  582.88  584.31  584.81  585.63  585.96  587.81  588.22   588.5  588.55
   588.6  589.16
  588.45  588.03  587.91  587.76  587.71  587.69  587.59  586.56  583.33  582.37
  582.26  581.64   580.7  580.48  579.87  579.48  578.65  578.32  577.83  575.79
  574.93   574.2  573.54  573.49  573.09  573.21  573.84  573.05   575.2   575.2
   575.2   575.2   575.2   575.2   575.2   575.2   575.2  572.89  575.99  577.27
   578.6  582.87   584.3   584.8  585.62  585.95   587.8  588.21  588.49  588.54
  588.59  589.16
  4507.6  4632.6  4667.6  4712.6  4727.6  4732.6  4763.6  4783.6  4823.6  4832.6
  4833.6  4843.6  4853.6  4857.6  4868.6  4873.6  4893.6  4897.6  4903.6  4918.6
  4923.6  4928.6  4938.6  4941.2  4962.3  4972.3  4987.3 4988.21  4988.3  4988.5
  4989.3    4992    5000    5008  5010.8  5011.5 5011.69  5011.8  5022.3  5041.8
  5063.2  5131.8  5146.8  5156.2  5171.8  5176.2  5201.2  5206.8  5236.2  5241.2
  5246.2  5306.2
  588.45  588.04  587.92  587.77  587.72   587.7   587.6  586.57  583.34  582.38
  582.27  581.65  580.71  580.49  579.88  579.49  578.66  578.33  577.86  577.59
  577.51  577.42  577.25   577.2   577.2   577.2   577.2   577.2   577.2   577.2
   577.2   577.2   577.2   577.2   577.2   577.2   577.2   577.2   577.2  577.28
  578.61  582.88  584.31  584.81  585.63  585.96  587.81  588.22   588.5  588.55
   588.6  589.16
   588.2  587.78  587.66  587.51  587.46  587.44  587.34  586.31  583.08  582.12
  582.01  581.39  580.45  580.23  579.62  579.23   578.4  578.07  577.58  575.54
  574.68  573.95  573.29  573.24  572.84  572.96  573.59   572.8  574.95  574.95
  574.95  574.95  574.95  574.95  574.95  574.95  574.95  572.64  575.74  577.02
  578.35  582.62  584.05  584.55  585.37   585.7  587.55  587.96  588.24  588.29
  588.34  588.91
Pier Skew, UpSta & Num, DnSta & Num=  ,4994.7, 2 ,4994.7, 2 , 0 , 0 , 0 ,,
       1       1
     569   576.2
       1       1
  568.75  575.95
Pier Skew, UpSta & Num, DnSta & Num=  ,5005.4, 2 ,5005.4, 2 , 0 , 0 , 0 ,,
       1       1
     569   576.2
       1       1
  568.75  575.95
Abutment Skew #Up #Dn= , 2 , 2
  4988.1  4989.3
   575.2  572.16
  4988.1  4989.3
  574.95  571.91
Abutment Skew #Up #Dn= , 2 , 2
  5010.8 5011.89
  572.24   575.2
  5010.8 5011.89
  571.99  574.95
BR Coef= 1 , 1 , 0 ,1.25, 0 ,,,0.8,0,2,0,
WSPro=,,,, 1 ,,,, 0 ,,,, 0 ,,,,-1 ,-1 ,-1 , 0 , 0 , 0 , 0 , 0
BR U #Sta/Elev= 52
  4507.6  588.45  4632.6  588.03  4667.6  587.91  4712.6  587.76  4727.6  587.71
  4732.6  587.69  4763.6  587.59  4783.6  586.56  4823.6  583.33  4832.6  582.37
  4833.6  582.26  4843.6  581.64  4853.6   580.7  4857.6  580.48  4868.6  579.87
  4873.6  579.48  4893.6  578.65  4897.6  578.32  4903.6  577.83  4918.6  575.79
  4923.6  574.93  4928.6   574.2  4938.6  573.54  4941.2  573.49  4962.3  573.09
  4972.3  573.21  4987.3  573.84 4988.21  573.05  4988.3  572.97  4988.5   572.8
  4989.3  572.16    4992     570    5000     570    5008     570  5010.8  572.24
  5011.5   572.8 5011.69  572.86  5011.8  572.89  5022.3  575.99  5041.8  577.27
  5063.2   578.6  5131.8  582.87  5146.8   584.3  5156.2   584.8  5171.8  585.62
  5176.2  585.95  5201.2   587.8  5206.8  588.21  5236.2  588.49  5241.2  588.54
  5246.2  588.59  5306.2  589.16
BR U #Mann= 3
  4507.6     .12  4988.5     .05  5011.5     .12
BR U Banks=4988.5,5011.5
BR D #Sta/Elev= 52
  4507.6   588.2  4632.6  587.78  4667.6  587.66  4712.6  587.51  4727.6  587.46
  4732.6  587.44  4763.6  587.34  4783.6  586.31  4823.6  583.08  4832.6  582.12
  4833.6  582.01  4843.6  581.39  4853.6  580.45  4857.6  580.23  4868.6  579.62
  4873.6  579.23  4893.6   578.4  4897.6  578.07  4903.6  577.58  4918.6  575.54
  4923.6  574.68  4928.6  573.95  4938.6  573.29  4941.2  573.24  4962.3  572.84
  4972.3  572.96  4987.3  573.59 4988.21   572.8  4988.3  572.72  4988.5  572.55
  4989.3  571.91    4992  569.75    5000  569.75    5008  569.75  5010.8  571.99
  5011.5  572.55 5011.69  572.61  5011.8  572.64  5022.3  575.74  5041.8  577.02
  5063.2  578.35  5131.8  582.62  5146.8  584.05  5156.2  584.55  5171.8  585.37
  5176.2   585.7  5201.2  587.55  5206.8  587.96  5236.2  588.24  5241.2  588.29
  5246.2  588.34  5306.2  588.91
BR D #Mann= 3
  4507.6     .12  4988.5     .05  5011.5     .12
BR D Banks=4988.5,5011.5
BC Design=,, 0 ,, 0 ,,,,,,
BC HTab HWMax=589.86

Type RM Length L Ch R = 1 ,11851.3 ,428.65,428.65,428.65
BEGIN DESCRIPTION:
Downstream Section of Bridge/Culvert/Weir
END DESCRIPTION:
XS GIS Cut Line= 3
      1880697.35       771925.17      1881195.88        771923.7
      1881495.93       771921.09
#Sta/Elev= 29
  4507.6   588.3  4763.6  587.44  4783.6  586.41  4823.6  583.18  4833.6  582.11
  4843.6  581.49  4853.6  580.55  4868.6  579.72  4873.6  579.33  4893.6   578.5
  4903.6  577.68  4918.6  575.64  4923.6  574.78  4928.6  574.05  4938.6  573.39
  4962.3  572.94  4972.3  573.06  4987.3  573.69  4988.5  572.65    4992  569.85
    5008  569.85  5011.5  572.65  5022.3  575.84  5041.8  577.12  5131.8  582.72
  5146.8  584.15  5171.8  585.47  5206.8  588.06  5306.2  589.01
#Mann= 3 , 1 , 0
  4507.6     .12       0  4988.5     .05       0  5011.5     .12       0
#XS Ineff= 2 , 0
       0    4975  575.92    5025       0  575.92
Permanent Ineff=
       F       F
Bank Sta=4988.5,5011.5
XS Rating Curve= 0
Exp/Cntr=0.5,0.3