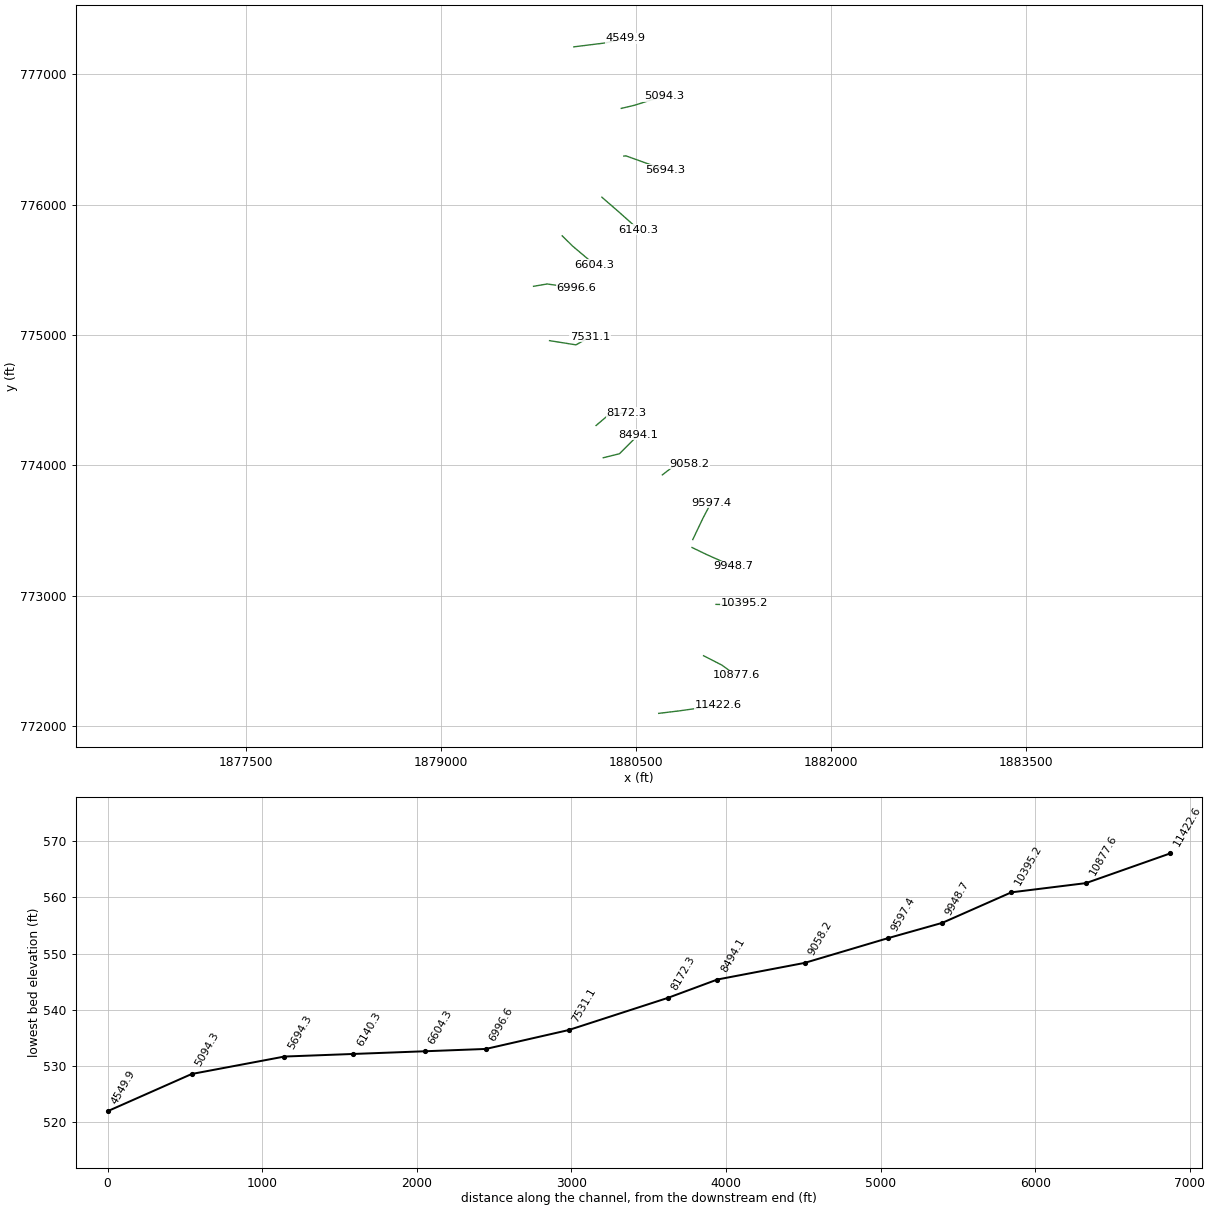
HEC-RAS study REEDY BRANCH.PRJ: Reedy Branch

--- REEDY BRANCH.g01 (geometry) --- (continued)

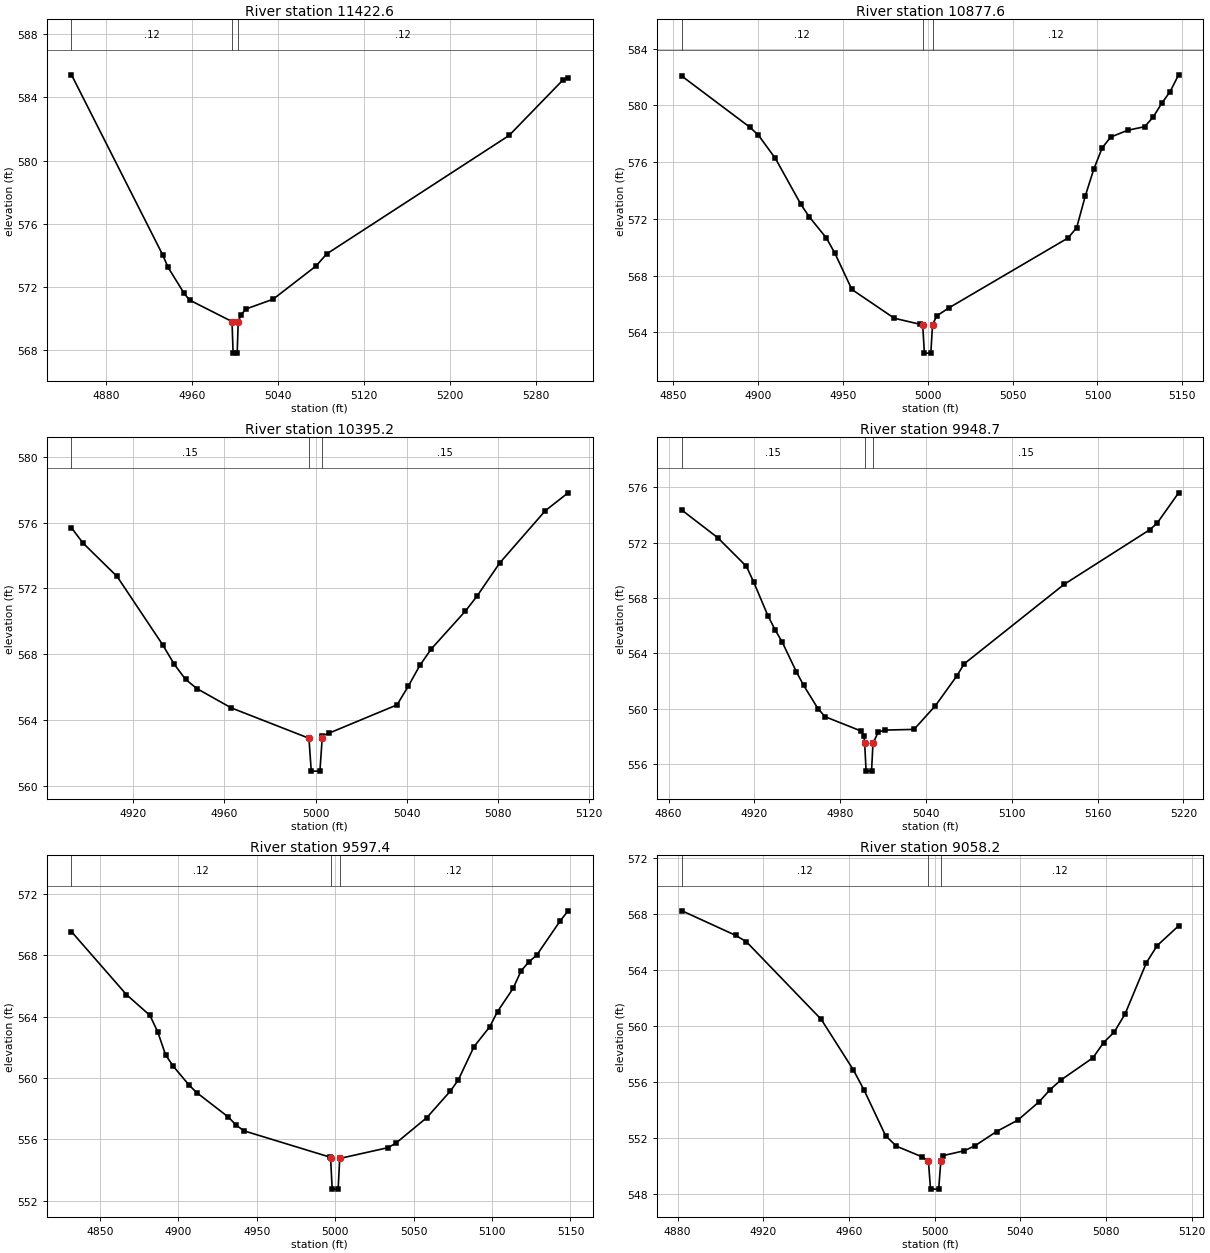
Type RM Length L Ch R = 1 ,11422.6 ,545,545,545
BEGIN DESCRIPTION:
Reedy Branch 24.0
END DESCRIPTION:
XS GIS Cut Line= 3
      1880677.38       772097.16      1880833.97       772116.24
      1881136.06        772158.7
#Sta/Elev= 17
  4847.5  585.43  4932.5  574.03  4937.5  573.24  4952.5  571.59  4957.5  571.17
  4997.1  569.81  4998.1  567.81  5001.9  567.81  5002.9  569.81  5005.3  570.23
  5010.3  570.61  5035.3  571.22  5075.3  573.32  5085.3  574.09  5255.3  581.59
  5305.3  585.09  5310.3  585.26
#Mann= 3 , 1 , 0
  4847.5     .12       0  4997.1     .05       0  5002.9     .12       0
Bank Sta=4997.1,5002.9
XS Rating Curve= 0
Exp/Cntr=0.3,0.1

Type RM Length L Ch R = 1 ,10877.6 ,482.4,482.4,482.4
BEGIN DESCRIPTION:
Reedy Branch 23.0
END DESCRIPTION:
XS GIS Cut Line= 3
      1881022.37       772539.27      1881162.66       772467.87
      1881272.05       772388.78
#Sta/Elev= 29
  4855.4  582.06  4895.4  578.46  4900.4   577.9  4910.4  576.26  4925.4  573.02
  4930.4  572.13  4940.4  570.65  4945.4  569.58  4955.4  567.02  4980.4  564.99
  4995.4  564.57  4997.1  564.53  4998.1  562.53  5001.9  562.53  5002.9  564.53
  5005.4  565.16  5012.8  565.74  5082.8  570.66  5087.8  571.39  5092.8   573.6
  5097.8  575.49  5102.8  577.01  5107.8  577.77  5117.8  578.25  5127.8   578.5
  5132.8  579.18  5137.8  580.14  5142.8  580.98  5147.8  582.16
#Mann= 3 , 1 , 0
  4855.4     .12       0  4997.1     .05       0  5002.9     .12       0
Bank Sta=4997.1,5002.9
XS Rating Curve= 0
Exp/Cntr=0.3,0.1

Type RM Length L Ch R = 1 ,10395.2 ,446.5,446.5,446.5
BEGIN DESCRIPTION:
Reedy Branch 22.0
END DESCRIPTION:
XS GIS Cut Line= 3
      1881118.78       772933.05      1881231.46       772930.33
      1881335.09       772947.15
#Sta/Elev= 23
    4893  575.69    4898  574.77    4913  572.73    4933  568.57    4938   567.4
    4943  566.47    4948  565.91    4963  564.74  4997.1  562.89  4998.1  560.89
  5001.9  560.89  5002.9  562.89    5003  563.04  5005.7  563.19  5035.7  564.92
  5040.7  566.07  5045.7  567.32  5050.7  568.32  5065.7  570.63  5070.7  571.52
  5080.7  573.55  5100.7  576.73  5110.7  577.82
#Mann= 3 , 1 , 0
    4893     .15       0  4997.1     .05       0  5002.9     .15       0
Bank Sta=4997.1,5002.9
XS Rating Curve= 0
Exp/Cntr=0.3,0.1

Type RM Length L Ch R = 1 ,9948.7  ,351.3,351.3,351.3
BEGIN DESCRIPTION:
Reedy Branch 21.0
END DESCRIPTION:
XS GIS Cut Line= 3
      1880933.31        773369.5        1881048.       773314.44
      1881248.96       773224.93
#Sta/Elev= 27
  4869.4  574.35  4894.4  572.36  4914.4  570.29  4919.4  569.18  4929.4  566.73
  4934.4  565.71  4939.4  564.82  4949.4  562.65  4954.4  561.68  4964.4     560
  4969.4  559.41  4994.4  558.38  4996.6     558  4997.1  557.47  4998.1  555.47
  5001.9  555.47  5002.9  557.47  5006.6  558.31  5011.6  558.44  5031.6  558.49
  5046.6  560.21  5061.6  562.37  5066.6  563.23  5136.6  568.99  5196.6  572.95
  5201.6  573.42  5216.6  575.61
#Mann= 3 , 1 , 0
  4869.4     .15       0  4997.1     .05       0  5002.9     .15       0
Bank Sta=4997.1,5002.9
XS Rating Curve= 0
Exp/Cntr=0.3,0.1

Type RM Length L Ch R = 1 ,9597.4  ,539.2,539.2,539.2
BEGIN DESCRIPTION:
Reedy Branch 20.0
END DESCRIPTION:
XS GIS Cut Line= 3
      1880939.58       773430.17      1881015.52       773589.63
      1881080.49       773713.62
#Sta/Elev= 30
  4831.9  569.54  4866.9  565.44  4881.9  564.08  4886.9     563  4891.9   561.5
  4896.9  560.75  4906.9  559.53  4911.9  559.03  4931.9  557.45  4936.9  556.92
  4941.9  556.55  4996.9  554.83  4997.1  554.75  4998.1  552.75  5001.9  552.75
  5002.9  554.75  5033.5  555.45  5038.5  555.73  5058.5  557.42  5073.5  559.15
  5078.5  559.87  5088.5  562.04  5098.5  563.33  5103.5  564.33  5113.5  565.85
  5118.5  566.98  5123.5  567.57  5128.5  568.01  5143.5  570.25  5148.5   570.9
#Mann= 3 , 1 , 0
  4831.9     .12       0  4997.1     .05       0  5002.9     .12       0
Bank Sta=4997.1,5002.9
XS Rating Curve= 0
Exp/Cntr=0.3,0.1

Type RM Length L Ch R = 1 ,9058.2  ,564.1,564.1,564.1
BEGIN DESCRIPTION:
Reedy Branch 19.0
END DESCRIPTION:
XS GIS Cut Line= 3
      1880705.54       773926.24      1880793.84       773994.76
      1880912.59       774012.28
#Sta/Elev= 28
  4882.1  568.21  4907.1  566.46  4912.1  566.01  4947.1  560.46  4962.1  556.85
  4967.1  555.41  4977.1  552.17  4982.1  551.42  4993.9  550.67  4997.1  550.35
  4998.1  548.35  5001.9  548.35  5002.9  550.35  5003.9  550.74  5013.9  551.09
  5018.9  551.45  5028.9  552.46  5038.9  553.28  5048.9   554.6  5053.9  555.45
  5058.9  556.13  5073.9  557.72  5078.9  558.81  5083.9  559.57  5088.9  560.85
  5098.9  564.52  5103.9  565.73  5113.9  567.14
#Mann= 3 , 1 , 0
  4882.1     .12       0  4997.1     .05       0  5002.9     .12       0
Bank Sta=4997.1,5002.9
XS Rating Curve= 0
Exp/Cntr=0.3,0.1

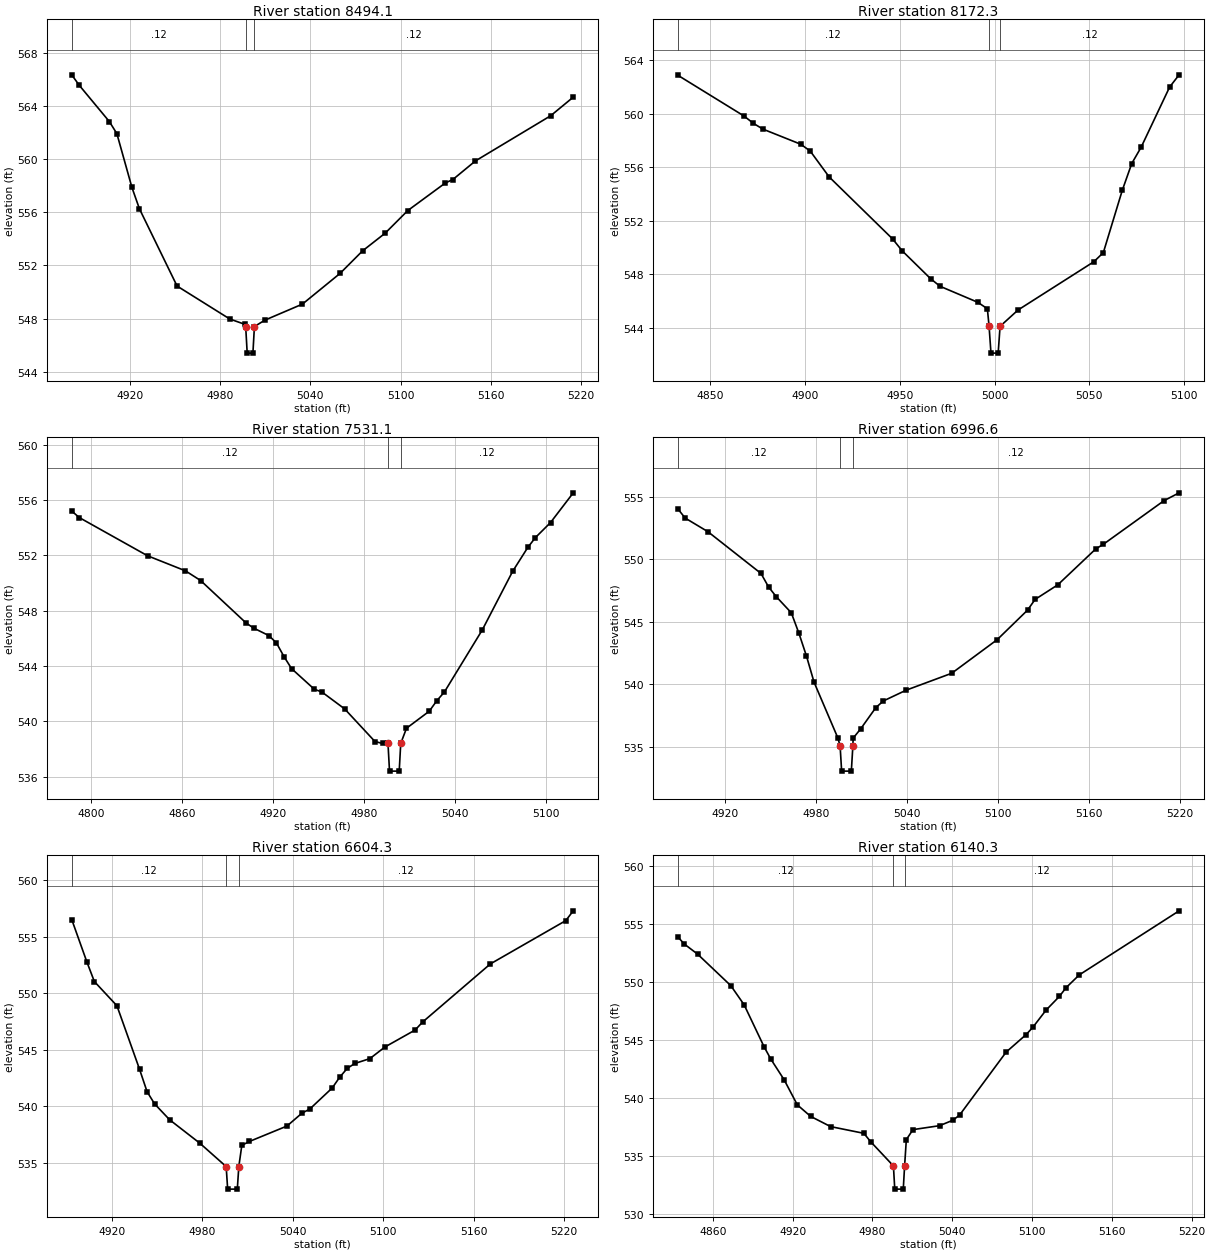
Type RM Length L Ch R = 1 ,8494.1  ,321.8,321.8,321.8
BEGIN DESCRIPTION:
Reedy Branch 18.0
END DESCRIPTION:
XS GIS Cut Line= 3
      1880250.75       774057.64      1880375.33        774088.4
      1880520.51       774233.11
#Sta/Elev= 24
  4881.5  566.35  4886.5  565.56  4906.5  562.83  4911.5  561.92  4921.5  557.87
  4926.5  556.26  4951.5  550.45  4986.5  547.97  4996.5  547.57  4997.1   547.4
  4998.1   545.4  5001.9   545.4  5002.9   547.4  5009.8  547.88  5034.8  549.09
  5059.8   551.4  5074.8   553.1  5089.8  554.43  5104.8  556.13  5129.8  558.21
  5134.8  558.47  5149.8  559.87  5199.8  563.27  5214.8  564.67
#Mann= 3 , 1 , 0
  4881.5     .12       0  4997.1     .05       0  5002.9     .12       0
Bank Sta=4997.1,5002.9
XS Rating Curve= 0
Exp/Cntr=0.3,0.1

Type RM Length L Ch R = 1 ,8172.3  ,641.2,641.2,641.2
BEGIN DESCRIPTION:
Reedy Branch 17.0
END DESCRIPTION:
XS GIS Cut Line= 4
       1880195.7       774305.25      1880282.32       774378.56
      1880346.66       774394.16      1880431.23       774402.96
#Sta/Elev= 25
  4832.7  562.87  4867.7  559.82  4872.7  559.27  4877.7  558.84  4897.7  557.71
  4902.7   557.2  4912.7  555.27  4946.2  550.64  4951.2  549.76  4966.2  547.68
  4971.2  547.11  4991.2  545.91  4996.2  545.43  4997.1  544.12  4998.1  542.12
  5001.9  542.12  5002.9  544.12  5012.4  545.34  5052.4  548.94  5057.4  549.62
  5067.4  554.27  5072.4  556.27  5077.4   557.5  5092.4  561.98  5097.4  562.89
#Mann= 3 , 1 , 0
  4832.7     .12       0  4997.1     .05       0  5002.9     .12       0
Bank Sta=4997.1,5002.9
XS Rating Curve= 0
Exp/Cntr=0.3,0.1

Type RM Length L Ch R = 1 ,7531.1  ,534.5,534.5,534.5
BEGIN DESCRIPTION:
Reedy Branch 16.0
END DESCRIPTION:
XS GIS Cut Line= 3
      1879837.65       774955.78       1880040.9       774923.52
      1880149.83       774984.84
#Sta/Elev= 30
  4787.2  555.21  4792.2  554.74  4837.2  551.98  4862.2  550.89  4872.2  550.19
  4902.2  547.12  4907.2  546.75  4917.2  546.21  4922.2  545.68  4927.2  544.69
  4932.2  543.82  4947.2  542.33  4952.2  542.13  4967.2  540.91  4987.2  538.55
  4992.2  538.41  4995.8  538.41  4996.8  536.41  5003.2  536.41  5004.2  538.41
    5008  539.51    5023  540.74    5028   541.5    5033  542.13    5058  546.62
    5078  550.85    5088  552.58    5093  553.29    5103  554.38    5118  556.53
#Mann= 3 , 1 , 0
  4787.2     .12       0  4995.8     .05       0  5004.2     .12       0
Bank Sta=4995.8,5004.2
XS Rating Curve= 0
Exp/Cntr=0.3,0.1

Type RM Length L Ch R = 1 ,6996.6  ,392.3,392.3,392.3
BEGIN DESCRIPTION:
Reedy Branch 15.0
END DESCRIPTION:
XS GIS Cut Line= 3
      1879714.41       775372.62      1879818.69       775390.41
      1880041.56       775359.45
#Sta/Elev= 29
  4888.6  554.07  4893.6  553.31  4908.6  552.22  4943.6  548.88  4948.6   547.8
  4953.6  547.03  4963.6  545.73  4968.6   544.1  4973.6  542.27  4978.6  540.18
  4994.4  535.69  4995.8  535.06  4996.8  533.06  5003.2  533.06  5004.2  535.06
  5004.4   535.7  5009.4  536.45  5019.4  538.15  5024.4  538.68  5039.4  539.54
  5069.4  540.89  5099.4  543.58  5119.4  545.94  5124.4   546.8  5139.4  547.97
  5164.4  550.84  5169.4  551.21  5209.4   554.7  5219.4  555.33
#Mann= 3 , 1 , 0
  4888.6     .12       0  4995.8     .05       0  5004.2     .12       0
Bank Sta=4995.8,5004.2
XS Rating Curve= 0
Exp/Cntr=0.3,0.1

Type RM Length L Ch R = 1 ,6604.3  ,464,464,464
BEGIN DESCRIPTION:
Reedy Branch 14.0
END DESCRIPTION:
XS GIS Cut Line= 3
      1879935.04       775759.42       1880015.6       775680.28
      1880184.31       775539.12
#Sta/Elev= 29
  4893.3  556.53  4903.3  552.79  4908.3  551.04  4923.3  548.89  4938.3  543.27
  4943.3  541.28  4948.3   540.2  4958.3  538.79  4978.3  536.72  4995.8  534.65
  4996.8  532.65  5003.2  532.65  5004.2  534.65  5006.2  536.53  5011.2  536.87
  5036.2  538.24  5046.2  539.39  5051.2  539.73  5066.2  541.61  5071.2  542.57
  5076.2  543.35  5081.2  543.78  5091.2  544.21  5101.2  545.24  5121.2  546.74
  5126.2  547.45  5171.2   552.6  5221.2  556.43  5226.2   557.3
#Mann= 3 , 1 , 0
  4893.3     .12       0  4995.8     .05       0  5004.2     .12       0
Bank Sta=4995.8,5004.2
XS Rating Curve= 0
Exp/Cntr=0.3,0.1

Type RM Length L Ch R = 1 ,6140.3  ,446,446,446
BEGIN DESCRIPTION:
Reedy Branch 13.0
END DESCRIPTION:
XS GIS Cut Line= 3
       1880240.3       776055.73      1880370.28       775943.23
      1880523.63        775807.2
#Sta/Elev= 30
  4833.6  553.94  4838.6   553.3  4848.6  552.43  4873.6  549.71  4883.6  548.06
  4898.6  544.44  4903.6  543.39  4913.6  541.61  4923.6  539.43  4933.6  538.44
  4948.6  537.56  4973.6  536.98  4978.6  536.27  4995.8  534.17  4996.8  532.17
  5003.2  532.17  5004.2  534.17  5005.5  536.44  5010.5   537.3  5030.5  537.64
  5040.5  538.11  5045.5  538.55  5080.5  543.98  5095.5  545.49  5100.5  546.11
  5110.5   547.6  5120.5  548.78  5125.5  549.53  5135.5  550.64  5210.5  556.16
#Mann= 3 , 1 , 0
  4833.6     .12       0  4995.8     .05       0  5004.2     .12       0
Bank Sta=4995.8,5004.2
XS Rating Curve= 0
Exp/Cntr=0.3,0.1

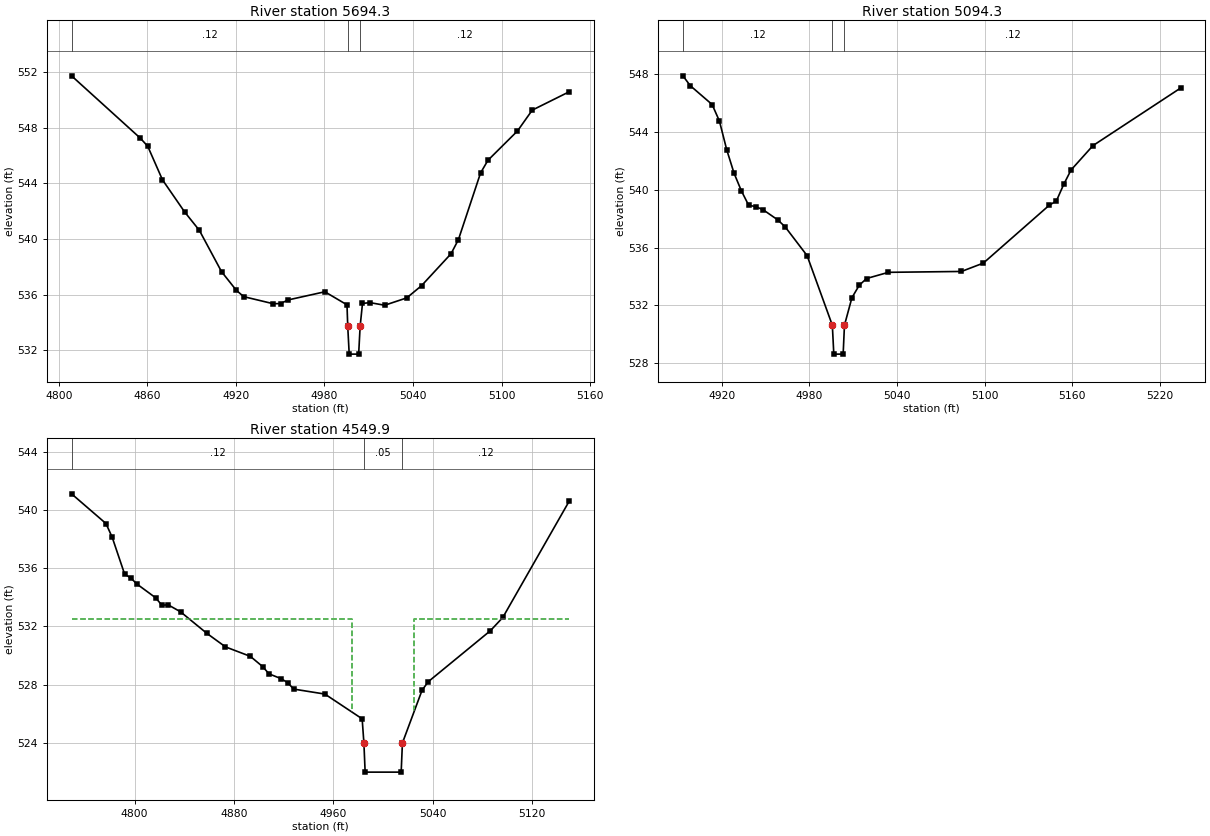
Type RM Length L Ch R = 1 ,5694.3  ,600,600,600
BEGIN DESCRIPTION:
Reedy Branch 12.0
END DESCRIPTION:
XS GIS Cut Line= 4
      1880408.73       776371.57      1880425.23       776372.95
      1880590.43       776313.81      1880728.05        776267.9
#Sta/Elev= 30
  4808.7  551.75  4855.3  547.26  4860.3  546.68  4870.3  544.26  4885.3  541.95
  4895.3  540.62  4910.3  537.65  4920.3  536.31  4925.3  535.85  4945.3  535.34
  4950.3  535.35  4955.3  535.61  4980.3   536.2  4995.3  535.26  4995.8  533.71
  4996.8  531.71  5003.2  531.71  5004.2  533.71  5005.8  535.36  5010.8  535.42
  5020.8  535.23  5035.8  535.76  5045.8  536.64  5065.8  538.94  5070.8  539.96
  5085.8  544.76  5090.8  545.67  5110.8  547.78  5120.8  549.28  5145.8   550.6
#Mann= 3 , 1 , 0
  4808.7     .12       0  4995.8     .05       0  5004.2     .12       0
Bank Sta=4995.8,5004.2
XS Rating Curve= 0
Exp/Cntr=0.3,0.1

Type RM Length L Ch R = 1 ,5094.3  ,544.4,544.4,544.4
BEGIN DESCRIPTION:
Reedy Branch 11.0
END DESCRIPTION:
XS GIS Cut Line= 3
      1880389.71       776737.17      1880492.59       776761.45
      1880716.57       776832.55
#Sta/Elev= 30
  4893.5   547.9  4898.5  547.22  4913.5  545.91  4918.5  544.76  4923.5  542.77
  4928.5  541.15  4933.5  539.93  4938.5  538.93  4943.5  538.83  4948.5  538.61
  4958.5  537.91  4963.5  537.43  4978.5  535.44  4995.8  530.61  4996.8  528.61
  5003.2  528.61  5004.1  530.61  5004.2  530.65  5009.2  532.52  5014.2  533.38
  5019.2  533.85  5034.2  534.28  5084.2  534.34  5099.2  534.92  5144.2  538.92
  5149.2  539.23  5154.2  540.37  5159.2  541.37  5174.2  543.06  5234.2  547.05
#Mann= 3 , 1 , 0
  4893.5     .12       0  4995.8     .05       0  5004.1     .12       0
Bank Sta=4995.8,5004.1
XS Rating Curve= 0
Exp/Cntr=0.5,0.3

Type RM Length L Ch R = 1 ,4549.9  ,84,84,84
BEGIN DESCRIPTION:
Upstream Section of Bridge/Culvert/Weir
END DESCRIPTION:
XS GIS Cut Line= 3
      1880024.27       777209.14      1880267.91       777239.33
      1880418.89       777274.41
#Sta/Elev= 29
  4749.2   541.1  4776.9  539.06  4781.9  538.12  4791.9  535.59  4796.9  535.32
  4801.9   534.9  4816.9  533.96  4821.9  533.45  4826.9  533.48  4836.9     533
  4858.1  531.52  4873.1  530.59  4893.1  529.94  4903.1  529.23  4908.1  528.74
  4918.1   528.4  4923.1  528.13  4928.1  527.69  4953.1  527.35  4983.1  525.65
  4984.5  523.99  4985.5  521.99  5014.5  521.99  5015.5  523.99  5031.3  527.61
  5036.3   528.2  5086.3   531.7  5096.3  532.61  5149.7  540.59
#Mann= 3 , 1 , 0
  4749.2     .12       0  4984.5     .05       0  5015.5     .12       0
#XS Ineff= 2 , 0
       0    4975   532.5    5025       0   532.5
Permanent Ineff=
       F       F
Bank Sta=4984.5,5015.5
XS Rating Curve= 0
Exp/Cntr=0.5,0.3