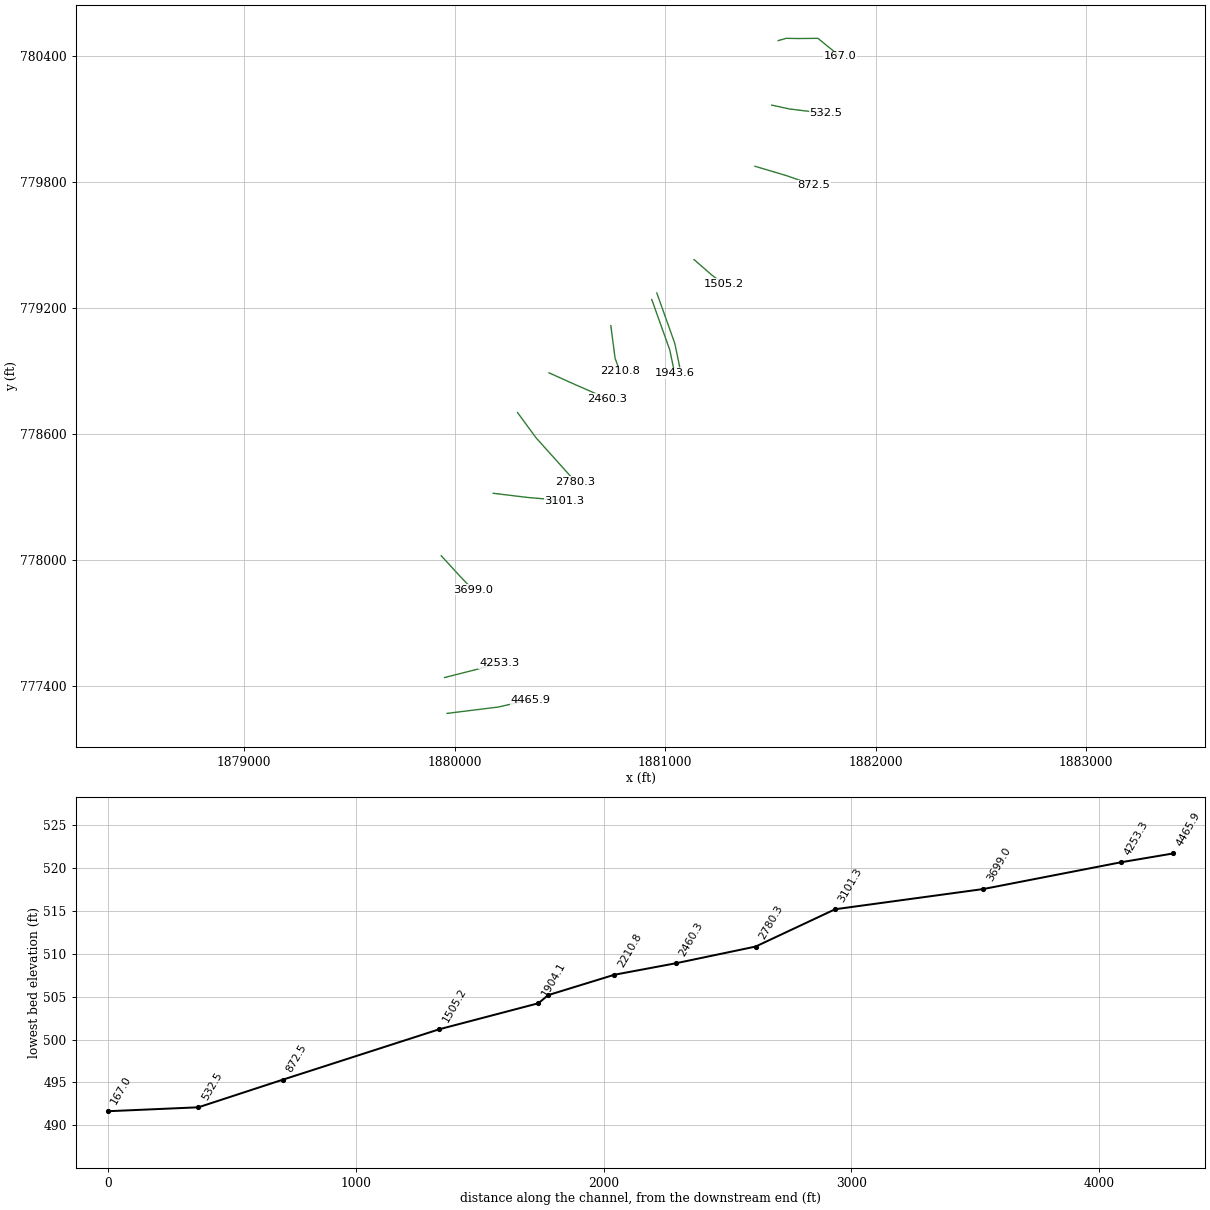
HEC-RAS study REEDY BRANCH.PRJ: Reedy Branch

--- REEDY BRANCH.g01 (geometry) --- (continued)

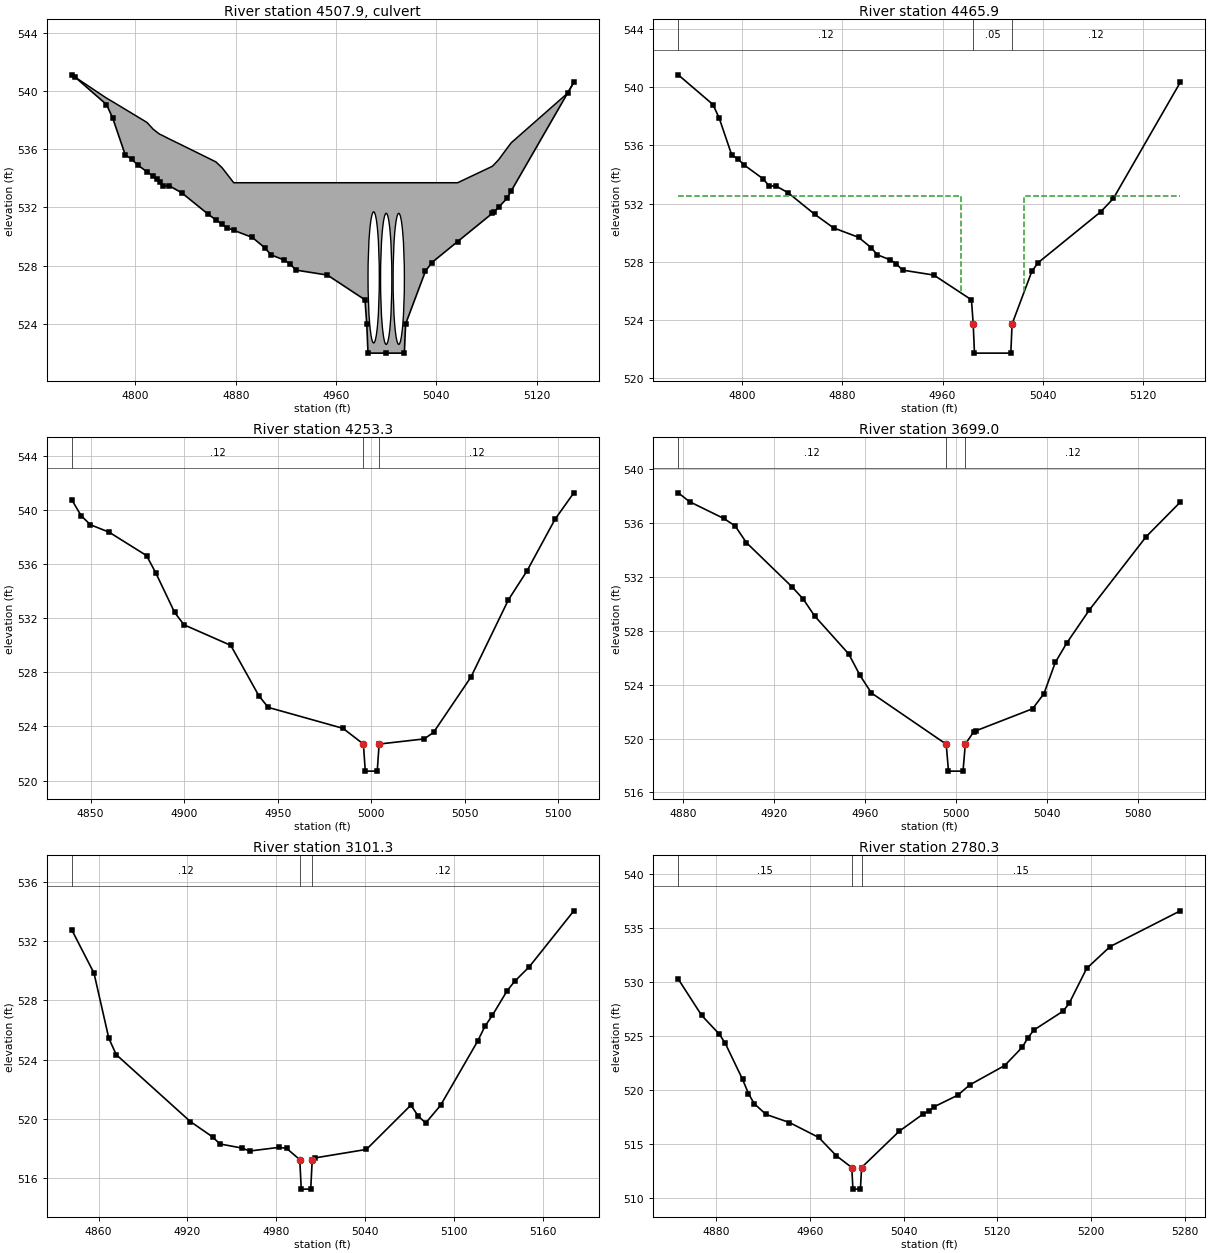
Type RM Length L Ch R = 2 ,4507.9  ,,,
BEGIN DESCRIPTION:
Reedy Branch - Quakenbush Rd 1
Structure ID: NCF-0083
Approximate Survey Structure
END DESCRIPTION:
Bridge Culvert--1,0,-1,-1, 0
Deck Dist Width WeirC Skew NumUp NumDn MinLoCord MaxHiCord MaxSubmerge Is_Ogee
10,64,3,0, 42, 42, , , 0.95, 0, 1,1,,
  4749.2  4751.9  4776.9  4781.9  4791.9  4796.9  4801.9  4809.2  4814.2  4816.9
  4819.2  4821.9  4826.9  4836.9  4858.1  4864.2  4869.2  4873.1  4878.4  4893.1
  4903.1  4908.1  4918.1  4923.1  4928.1  4953.1  4983.1  4984.5  4985.5    5000
  5014.5  5015.5  5031.3  5036.3    5057  5084.7  5086.3  5089.7  5096.3  5099.7
  5144.7  5149.7
  541.11  540.95  539.51  539.26  538.74  538.48  538.22  537.84  537.37  537.19
  537.04  536.93  536.71  536.29  535.39  535.13  534.72  534.29   533.7   533.7
   533.7   533.7   533.7   533.7   533.7   533.7   533.7   533.7   533.7   533.7
   533.7   533.7   533.7   533.7   533.7  534.83  534.97  535.28  536.05  536.44
  539.85   540.6
  541.11  540.95  539.07  538.13   535.6  535.33  534.91  534.45  534.14  533.97
  533.74  533.46  533.49  533.01  531.53  531.15  530.84   530.6  530.43  529.95
  529.24  528.75  528.41  528.14   527.7  527.36  525.66     524     522     522
     522     524  527.62  528.21  529.66   531.6  531.71  532.02  532.62  533.13
  539.85   540.6
  4749.2  4751.9  4776.9  4781.9  4791.9  4796.9  4801.9  4809.2  4814.2  4816.9
  4819.2  4821.9  4826.9  4836.9  4858.1  4864.2  4869.2  4873.1  4878.4  4893.1
  4903.1  4908.1  4918.1  4923.1  4928.1  4953.1  4983.1  4984.5  4985.5    5000
  5014.5  5015.5  5031.3  5036.3    5057  5084.7  5086.3  5089.7  5096.3  5099.7
  5144.7  5149.7
  540.95  540.81  539.51  539.26  538.74  538.48  538.22  537.84  537.37  537.19
  537.04  536.93  536.71  536.29  535.39  535.13  534.72  534.29   533.7   533.7
   533.7   533.7   533.7   533.7   533.7   533.7   533.7   533.7   533.7   533.7
   533.7   533.7   533.7   533.7   533.7  534.83  534.97  535.28  536.05  536.44
   539.8  540.44
  540.79  540.63  538.75  537.81  535.28  535.01  534.59  534.13  533.82  533.65
  533.42  533.14  533.17  532.69  531.21  530.83  530.52  530.28  530.11  529.63
  528.92  528.43  528.09  527.82  527.38  527.04  525.34  523.68  521.68  521.68
  521.68  523.68   527.3  527.89  529.34  531.28  531.39   531.7   532.3  532.81
  539.53  540.28
BR Coef= 1 , 0 , 0 ,1.25, 0 ,,,0.8,-1,2,0,
WSPro=,,,, 1 ,,,, 0 ,,,, 0 ,,,,-1 ,-1 ,-1 , 0 , 0 , 0 , 0 , 0
Culvert=1,9,,64,0.024,0.7,1,2,2,522.7,4990.02,522.28,4990.02,Culvert #1  , 0 ,10
Culvert Bottom n=0.024
Culvert=1,9,,64,0.024,0.7,1,2,2,522.6,5000.02,522.28,5000.02,Culvert #2  , 0 ,10
Culvert Bottom n=0.024
Culvert=1,9,,64,0.024,0.7,1,2,2,522.6,5010.02,522.28,5010.02,Culvert #3  , 0 ,10
Culvert Bottom n=0.024
BR U #Sta/Elev= 42
  4749.2  541.11  4751.9  540.95  4776.9  539.07  4781.9  538.13  4791.9   535.6
  4796.9  535.33  4801.9  534.91  4809.2  534.45  4814.2  534.14  4816.9  533.97
  4819.2  533.74  4821.9  533.46  4826.9  533.49  4836.9  533.01  4858.1  531.53
  4864.2  531.15  4869.2  530.84  4873.1   530.6  4878.4  530.43  4893.1  529.95
  4903.1  529.24  4908.1  528.75  4918.1  528.41  4923.1  528.14  4928.1   527.7
  4953.1  527.36  4983.1  525.66  4984.5     524  4985.5     522    5000     522
  5014.5     522  5015.5     524  5031.3  527.62  5036.3  528.21    5057  529.66
  5084.7   531.6  5086.3  531.71  5089.7  532.02  5096.3  532.62  5099.7  533.13
  5144.7  539.85  5149.7   540.6
BR U #Mann= 3
  4749.2     .12  4984.5     .05  5015.5     .12
BR U Banks=4984.5,5015.5
BR D #Sta/Elev= 42
  4749.2  540.79  4751.9  540.63  4776.9  538.75  4781.9  537.81  4791.9  535.28
  4796.9  535.01  4801.9  534.59  4809.2  534.13  4814.2  533.82  4816.9  533.65
  4819.2  533.42  4821.9  533.14  4826.9  533.17  4836.9  532.69  4858.1  531.21
  4864.2  530.83  4869.2  530.52  4873.1  530.28  4878.4  530.11  4893.1  529.63
  4903.1  528.92  4908.1  528.43  4918.1  528.09  4923.1  527.82  4928.1  527.38
  4953.1  527.04  4983.1  525.34  4984.5  523.68  4985.5  521.68    5000  521.68
  5014.5  521.68  5015.5  523.68  5031.3   527.3  5036.3  527.89    5057  529.34
  5084.7  531.28  5086.3  531.39  5089.7   531.7  5096.3   532.3  5099.7  532.81
  5144.7  539.53  5149.7  540.28
BR D #Mann= 3
  4749.2     .12  4984.5     .05  5015.5     .12
BR D Banks=4984.5,5015.5
BC Design=,, 0 ,, 0 ,,,,,,
BC HTab HWMax=541.1

Type RM Length L Ch R = 1 ,4465.9  ,212.6,212.6,212.6
BEGIN DESCRIPTION:
Downstream Section of Bridge/Culvert/Weir
END DESCRIPTION:
XS GIS Cut Line= 3
      1879964.84        777268.5      1880208.47       777298.69
      1880359.45       777333.77
#Sta/Elev= 29
  4749.2  540.85  4776.9  538.81  4781.9  537.87  4791.9  535.34  4796.9  535.07
  4801.9  534.65  4816.9  533.71  4821.9   533.2  4826.9  533.23  4836.9  532.75
  4858.1  531.27  4873.1  530.34  4893.1  529.69  4903.1  528.98  4908.1  528.49
  4918.1  528.15  4923.1  527.88  4928.1  527.44  4953.1   527.1  4983.1   525.4
  4984.5  523.74  4985.5  521.74  5014.5  521.74  5015.5  523.74  5031.3  527.36
  5036.3  527.95  5086.3  531.45  5096.3  532.36  5149.7  540.34
#Mann= 3 , 1 , 0
  4749.2     .12       0  4984.5     .05       0  5015.5     .12       0
#XS Ineff= 2 , 0
       0    4975   532.5    5025       0   532.5
Permanent Ineff=
       F       F
Bank Sta=4984.5,5015.5
XS Rating Curve= 0
Exp/Cntr=0.5,0.3

Type RM Length L Ch R = 1 ,4253.3  ,554.3,554.3,554.3
BEGIN DESCRIPTION:
Reedy Branch 10.0
END DESCRIPTION:
XS GIS Cut Line= 3
      1879952.65       777438.95        1880111.       777479.38
      1880212.06       777507.77
#Sta/Elev= 23
  4839.9  540.75  4844.9  539.57  4849.9   538.9  4859.9  538.35  4879.9  536.62
  4884.9  535.32  4894.9  532.42  4899.9  531.51  4924.9  529.99  4939.9  526.27
  4944.9  525.41  4984.9  523.86  4995.8   522.7  4996.8   520.7  5003.2   520.7
  5004.2   522.7  5028.3  523.08  5033.3  523.56  5053.3  527.65  5073.3  533.35
  5083.3   535.5  5098.3  539.32  5108.3  541.26
#Mann= 3 , 1 , 0
  4839.9     .12       0  4995.8     .05       0  5004.2     .12       0
Bank Sta=4995.8,5004.2
XS Rating Curve= 0
Exp/Cntr=0.3,0.1

Type RM Length L Ch R = 1 ,3699.0  ,597.7,597.7,597.7
BEGIN DESCRIPTION:
Reedy Branch 9.0
END DESCRIPTION:
XS GIS Cut Line= 3
      1879937.03       778018.77      1880025.38       777922.12
       1880087.5       777857.07
#Sta/Elev= 24
  4877.9  538.24  4882.9  537.58  4897.9  536.34  4902.9  535.79  4907.9  534.54
  4927.9  531.27  4932.9  530.35  4937.9   529.1  4952.9  526.28  4957.9  524.68
  4962.9  523.38  4995.8  519.58  4996.8  517.58  5003.2  517.58  5004.2  519.58
  5007.9   520.5  5008.8  520.57  5033.8  522.21  5038.8  523.33  5043.8  525.65
  5048.8  527.08  5058.8  529.55  5083.8  534.99  5098.8  537.55
#Mann= 3 , 1 , 0
  4877.9     .12       0  4995.8     .05       0  5004.2     .12       0
Bank Sta=4995.8,5004.2
XS Rating Curve= 0
Exp/Cntr=0.3,0.1

Type RM Length L Ch R = 1 ,3101.3  ,321,321,321
BEGIN DESCRIPTION:
Reedy Branch 8.0
END DESCRIPTION:
XS GIS Cut Line= 3
      1880184.31       778316.07      1880347.04       778296.37
      1880521.37       778281.32
#Sta/Elev= 28
  4841.9  532.78  4856.9  529.85  4866.9  525.44  4871.9  524.33  4921.9   519.8
  4936.9  518.76  4941.9  518.28  4956.9     518  4961.9   517.8  4981.9  518.05
  4986.9  517.98  4995.8  517.22  4996.8  515.22  5003.2  515.22  5004.2  517.22
  5005.8  517.33  5040.8  517.91  5070.8  520.91  5075.8  520.16  5080.8   519.7
  5090.8  520.89  5115.8  525.23  5120.8  526.25  5125.8  526.99  5135.8  528.66
  5140.8  529.29  5150.8  530.29  5180.8  534.07
#Mann= 3 , 1 , 0
  4841.9     .12       0  4995.8     .05       0  5004.2     .12       0
Bank Sta=4995.8,5004.2
XS Rating Curve= 0
Exp/Cntr=0.3,0.1

Type RM Length L Ch R = 1 ,2780.3  ,320,320,320
BEGIN DESCRIPTION:
Reedy Branch 7.0
END DESCRIPTION:
XS GIS Cut Line= 3
      1880299.53        778700.3       1880387.4       778580.12
       1880574.2       778371.64
#Sta/Elev= 30
  4847.6  530.29  4867.6  526.93  4882.6   525.2  4887.6  524.38  4902.6     521
  4907.6  519.69  4912.6  518.75  4922.6  517.77  4942.6  517.02  4967.6  515.64
  4982.6  513.95  4995.8  512.86  4996.8  510.86  5003.2  510.86  5004.2  512.86
  5036.4  516.22  5056.4  517.78  5061.4  518.07  5066.4  518.49  5086.4  519.55
  5096.4  520.49  5126.4  522.29  5141.4  523.98  5146.4  524.88  5151.4  525.58
  5176.4  527.33  5181.4  528.03  5196.4  531.27  5216.4  533.29  5276.4   536.6
#Mann= 3 , 1 , 0
  4847.6     .15       0  4995.8    .045       0  5004.2     .15       0
Bank Sta=4995.8,5004.2
XS Rating Curve= 0
Exp/Cntr=0.3,0.1

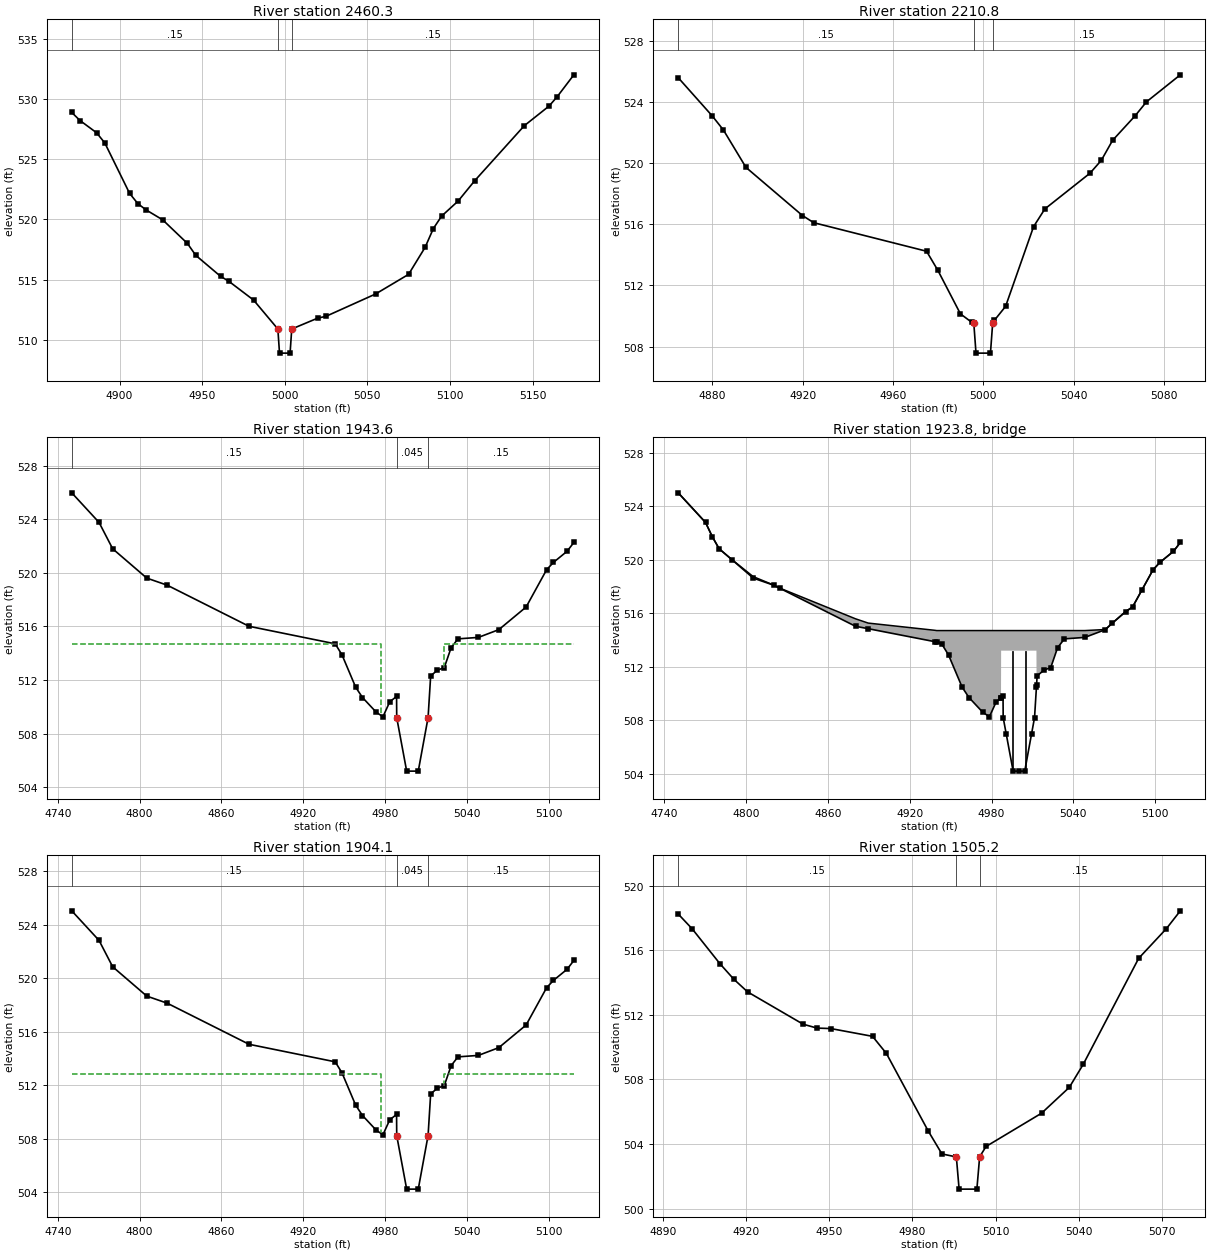
Type RM Length L Ch R = 1 ,2460.3  ,249.5,249.5,249.5
BEGIN DESCRIPTION:
Reedy Branch 6.0
END DESCRIPTION:
XS GIS Cut Line= 3
      1880448.89       778889.62      1880570.86       778834.51
      1880726.57       778766.39
#Sta/Elev= 30
  4871.1  528.87  4876.1   528.2  4886.1  527.19  4891.1  526.34  4906.1  522.16
  4911.1  521.31  4916.1  520.79  4926.1  519.97  4941.1  518.01  4946.1  517.03
  4961.1  515.29  4966.1  514.88  4981.1  513.32  4995.8  510.92  4996.8  508.92
  5003.2  508.92  5004.2  510.92  5019.9  511.82  5024.9  511.97  5054.9  513.82
  5074.9  515.45  5084.9  517.69  5089.9  519.25  5094.9  520.28  5104.9  521.53
  5114.9  523.21  5144.9  527.77  5159.9   529.4  5164.9  530.19  5174.9  531.99
#Mann= 3 , 1 , 0
  4871.1     .15       0  4995.8    .045       0  5004.2     .15       0
Bank Sta=4995.8,5004.2
XS Rating Curve= 0
Exp/Cntr=0.3,0.1

Type RM Length L Ch R = 1 ,2210.8  ,267.25,267.25,267.25
BEGIN DESCRIPTION:
Reedy Branch 5.0
END DESCRIPTION:
XS GIS Cut Line= 3
      1880742.59       779114.07      1880762.88       778958.04
      1880785.91        778897.2
#Sta/Elev= 24
  4864.9   525.6  4879.9  523.11  4884.9  522.18  4894.9  519.73  4919.9  516.58
  4924.9  516.11  4974.9  514.24  4979.9  512.99  4989.9  510.14  4994.9  509.59
  4995.8  509.57  4996.8  507.57  5003.2  507.57  5004.2  509.57  5004.9  509.71
  5009.9  510.63  5022.3  515.85  5027.3  517.01  5047.3  519.35  5052.3  520.19
  5057.3   521.5  5067.3  523.11  5072.3  524.02  5087.3  525.79
#Mann= 3 , 1 , 0
  4864.9     .15       0  4995.8    .045       0  5004.2     .15       0
Bank Sta=4995.8,5004.2
XS Rating Curve= 0
Exp/Cntr=0.5,0.3

Type RM Length L Ch R = 1 ,1943.6  ,39.5,39.5,39.5
BEGIN DESCRIPTION:
Upstream Section of Bridge/Culvert/Weir
END DESCRIPTION:
XS GIS Cut Line= 3
      1880936.98        779238.5      1881022.54       778998.51
      1881045.69       778887.49
#Sta/Elev= 30
  4750.2  525.98  4770.2  523.77  4780.2   521.8  4805.2  519.61  4820.2  519.08
  4880.2  516.01  4943.4   514.7  4948.4  513.87  4958.4  511.46  4963.4  510.69
  4973.4   509.6  4978.4  509.25  4983.4  510.37  4988.4  510.77  4988.5  509.19
  4995.8  505.19  5004.3  505.19  5011.5  509.19  5013.4  512.31  5018.4  512.73
  5023.4  512.93  5028.4  514.41  5033.4  515.07  5048.4  515.18  5063.4  515.76
  5083.4  517.45  5098.4  520.23  5103.4  520.78  5113.4  521.61  5118.4  522.27
#Mann= 3 , 1 , 0
  4750.2     .15       0  4988.5    .045       0  5011.5     .15       0
#XS Ineff= 2 , 0
       0    4977   514.7    5023       0   514.7
Permanent Ineff=
       F       F
Bank Sta=4988.5,5011.5
XS Rating Curve= 0
Exp/Cntr=0.5,0.3

Type RM Length L Ch R = 3 ,1923.8  ,,,
BEGIN DESCRIPTION:
Reedy Branch - Holman Mill Rd
Structure ID: NCF-0084
Approximate Survey Structure
END DESCRIPTION:
Bridge Culvert--1,0,-1,-1, 0
Deck Dist Width WeirC Skew NumUp NumDn MinLoCord MaxHiCord MaxSubmerge Is_Ogee
10,19.5,2.6,0, 46, 46, , , 0.95, 0, 1,1,,
  4750.2  4770.2  4775.2  4780.2  4789.5  4805.2  4820.2  4824.5  4880.2  4889.5
  4938.4  4939.8  4943.4  4948.4  4958.4  4963.4  4973.4  4978.4  4983.4 4986.91
    4987  4988.4  4988.5  4990.8  4995.8    5000  5004.3  5009.3  5011.5 5012.89
    5013  5013.4  5018.4  5023.4  5028.4  5033.4  5048.4  5063.4  5068.4  5078.4
  5083.4  5090.2  5098.4  5103.4  5113.4  5118.4
  524.99  522.78  521.71  520.81  520.01  518.73   518.1  517.88  515.58  515.26
  514.72   514.7   514.7   514.7   514.7   514.7   514.7   514.7   514.7   514.7
   514.7   514.7   514.7   514.7   514.7   514.7   514.7   514.7   514.7   514.7
   514.7   514.7   514.7   514.7   514.7   514.7   514.7  514.78  515.25  516.13
  516.47  517.73  519.24  519.79  520.62  521.28
  524.99  522.78  521.71  520.81     520  518.62  518.09  517.87  515.02  514.84
  513.87  513.83  513.71  512.88  510.47   509.7  508.61  508.26  509.38  509.66
   513.2   513.2   513.2   513.2   513.2   513.2   513.2   513.2   513.2   513.2
  510.66  511.32  511.74  511.94  513.42  514.08  514.19  514.77  515.24  516.12
  516.46  517.72  519.24  519.79  520.62  521.28
  4750.2  4770.2  4775.2  4780.2  4789.5  4805.2  4820.2  4824.5  4880.2  4889.5
  4938.4  4939.8  4943.4  4948.4  4958.4  4963.4  4973.4  4978.4  4983.4 4986.91
    4987  4988.4  4988.5  4990.8  4995.8    5000  5004.3  5009.3  5011.5 5012.89
    5013  5013.4  5018.4  5023.4  5028.4  5033.4  5048.4  5063.4  5068.4  5078.4
  5083.4  5090.2  5098.4  5103.4  5113.4  5118.4
  524.99  522.78  521.71  520.81  520.01  518.73   518.1  517.88  515.58  515.26
  514.72   514.7   514.7   514.7   514.7   514.7   514.7   514.7   514.7   514.7
   514.7   514.7   514.7   514.7   514.7   514.7   514.7   514.7   514.7   514.7
   514.7   514.7   514.7   514.7   514.7   514.7   514.7  514.78  515.25  516.13
  516.47  517.73  519.24  519.79  520.62  521.28
  524.74  522.53  521.46  520.56  519.75  518.37  517.84  517.62  514.77  514.59
  513.62  513.58  513.46  512.63  510.22  509.45  508.36  508.01  509.13  509.41
  512.95  512.95  512.95  512.95  512.95  512.95  512.95  512.95  512.95  512.95
  510.41  511.07  511.49  511.69  513.17  513.83  513.94  514.52  514.99  515.87
  516.21  517.47  518.99  519.54  520.37  521.03
Pier Skew, UpSta & Num, DnSta & Num=  ,4995.4, 2 ,4995.4, 2 , 0 , 0 , 0 ,,
       1       1
   503.2   514.2
       1       1
  502.95  513.95
Pier Skew, UpSta & Num, DnSta & Num=  ,5004.7, 2 ,5004.7, 2 , 0 , 0 , 0 ,,
       1       1
   503.2   514.2
       1       1
  502.95  513.95
Abutment Skew #Up #Dn= , 2 , 2
  4986.8  4990.8
   513.2  506.94
  4986.8  4990.8
  512.95  506.69
Abutment Skew #Up #Dn= , 2 , 2
  5009.3 5013.09
  506.98   513.2
  5009.3 5013.09
  506.73  512.95
BR Coef= 1 , 1 , 0 ,1.25, 0 ,,,0.8,0,2,0,
WSPro=,,,, 1 ,,,, 0 ,,,, 0 ,,,,-1 ,-1 ,-1 , 0 , 0 , 0 , 0 , 0
BR U #Sta/Elev= 46
  4750.2  524.99  4770.2  522.78  4775.2  521.71  4780.2  520.81  4789.5     520
  4805.2  518.62  4820.2  518.09  4824.5  517.87  4880.2  515.02  4889.5  514.84
  4938.4  513.87  4939.8  513.83  4943.4  513.71  4948.4  512.88  4958.4  510.47
  4963.4   509.7  4973.4  508.61  4978.4  508.26  4983.4  509.38 4986.91  509.66
    4987  509.67  4988.4  509.78  4988.5   508.2  4990.8  506.94  4995.8   504.2
    5000   504.2  5004.3   504.2  5009.3  506.98  5011.5   508.2 5012.89  510.48
    5013  510.66  5013.4  511.32  5018.4  511.74  5023.4  511.94  5028.4  513.42
  5033.4  514.08  5048.4  514.19  5063.4  514.77  5068.4  515.24  5078.4  516.12
  5083.4  516.46  5090.2  517.72  5098.4  519.24  5103.4  519.79  5113.4  520.62
  5118.4  521.28
BR U #Mann= 3
  4750.2     .15  4988.5    .045  5011.5     .15
BR U Banks=4988.5,5011.5
BR D #Sta/Elev= 46
  4750.2  524.74  4770.2  522.53  4775.2  521.46  4780.2  520.56  4789.5  519.75
  4805.2  518.37  4820.2  517.84  4824.5  517.62  4880.2  514.77  4889.5  514.59
  4938.4  513.62  4939.8  513.58  4943.4  513.46  4948.4  512.63  4958.4  510.22
  4963.4  509.45  4973.4  508.36  4978.4  508.01  4983.4  509.13 4986.91  509.41
    4987  509.42  4988.4  509.53  4988.5  507.95  4990.8  506.69  4995.8  503.95
    5000  503.95  5004.3  503.95  5009.3  506.73  5011.5  507.95 5012.89  510.23
    5013  510.41  5013.4  511.07  5018.4  511.49  5023.4  511.69  5028.4  513.17
  5033.4  513.83  5048.4  513.94  5063.4  514.52  5068.4  514.99  5078.4  515.87
  5083.4  516.21  5090.2  517.47  5098.4  518.99  5103.4  519.54  5113.4  520.37
  5118.4  521.03
BR D #Mann= 3
  4750.2     .15  4988.5    .045  5011.5     .15
BR D Banks=4988.5,5011.5
BC Design=,, 0 ,, 0 ,,,,,,
BC HTab HWMax=525.98

Type RM Length L Ch R = 1 ,1904.1  ,398.85,398.85,398.85
BEGIN DESCRIPTION:
Downstream Section of Bridge/Culvert/Weir
END DESCRIPTION:
XS GIS Cut Line= 3
      1880960.71       779270.09      1881046.26       779030.09
      1881069.42       778919.07
#Sta/Elev= 30
  4750.2  525.03  4770.2  522.82  4780.2  520.85  4805.2  518.66  4820.2  518.13
  4880.2  515.06  4943.4  513.75  4948.4  512.92  4958.4  510.51  4963.4  509.74
  4973.4  508.65  4978.4   508.3  4983.4  509.42  4988.4  509.82  4988.5  508.24
  4995.8  504.24  5004.3  504.24  5011.5  508.24  5013.4  511.36  5018.4  511.78
  5023.4  511.98  5028.4  513.46  5033.4  514.12  5048.4  514.23  5063.4  514.81
  5083.4   516.5  5098.4  519.28  5103.4  519.83  5113.4  520.66  5118.4  521.32
#Mann= 3 , 1 , 0
  4750.2     .15       0  4988.5    .045       0  5011.5     .15       0
#XS Ineff= 2 , 0
       0    4977  512.86    5023       0  512.86
Permanent Ineff=
       F       F
Bank Sta=4988.5,5011.5
XS Rating Curve= 0
Exp/Cntr=0.5,0.3

Type RM Length L Ch R = 1 ,1505.2  ,632.7,632.7,632.7
BEGIN DESCRIPTION:
Reedy Branch 4.0
END DESCRIPTION:
XS GIS Cut Line= 3
      1881137.99       779428.55      1881221.52       779355.53
      1881277.06         779313.
#Sta/Elev= 24
  4895.6  518.24  4900.6  517.33  4910.6  515.17  4915.6  514.21  4920.6  513.42
  4940.6  511.42  4945.6  511.18  4950.6  511.15  4965.6  510.67  4970.6  509.61
  4985.6  504.83  4990.6  503.39  4995.6  503.21  4995.8  503.21  4996.8  501.21
  5003.2  501.21  5004.2  503.21  5006.5  503.85  5026.5  505.91  5036.5  507.51
  5041.5  508.93  5061.5   515.5  5071.5  517.34  5076.5  518.44
#Mann= 3 , 1 , 0
  4895.6     .15       0  4995.8    .045       0  5004.2     .15       0
Bank Sta=4995.8,5004.2
XS Rating Curve= 0
Exp/Cntr=0.3,0.1

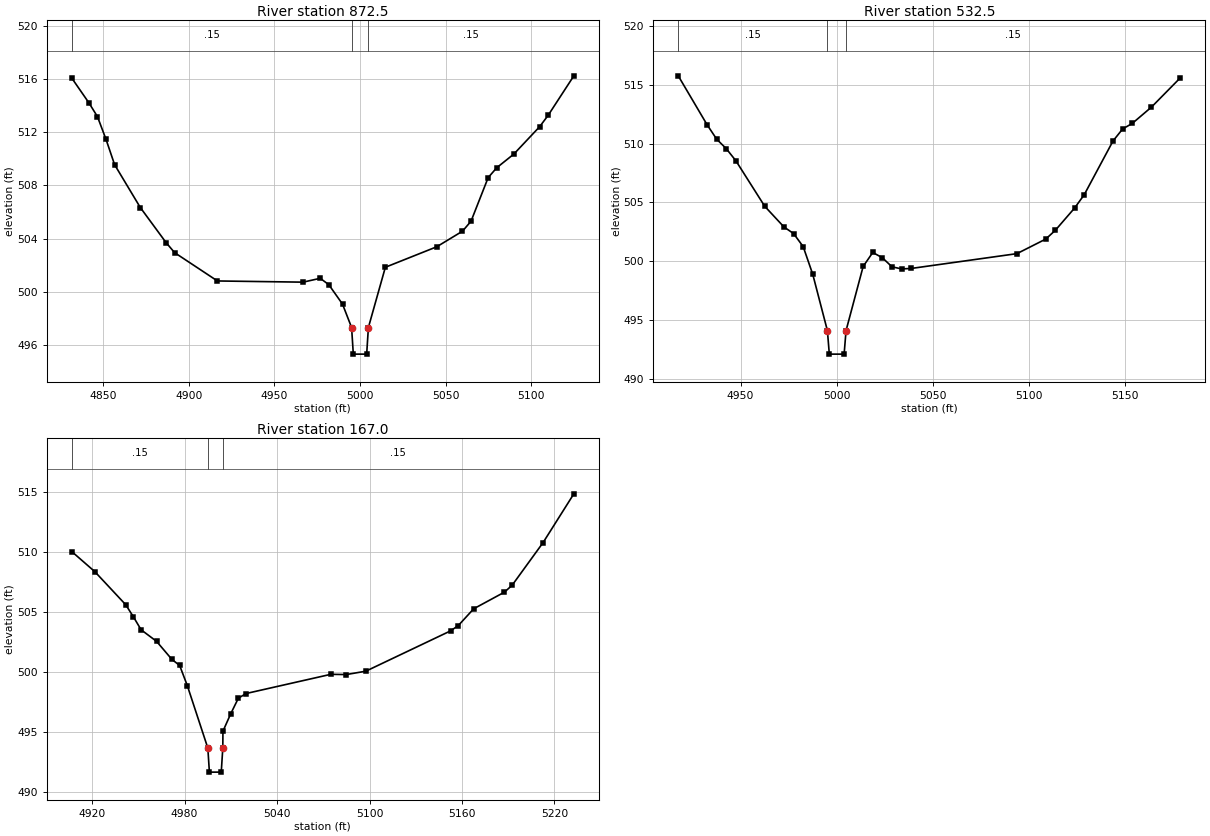
Type RM Length L Ch R = 1 ,872.5   ,340,340,340
BEGIN DESCRIPTION:
Reedy Branch 3.0
END DESCRIPTION:
XS GIS Cut Line= 3
      1881427.21       779872.74      1881578.65       779827.63
      1881705.86       779782.51
#Sta/Elev= 27
  4831.8  516.06  4841.8   514.2  4846.8  513.16  4851.8  511.45  4856.8  509.55
  4871.8  506.33  4886.8   503.7  4891.8  502.94  4916.8  500.81  4966.8  500.72
  4976.8  501.01  4981.8  500.53  4989.8  499.07  4995.1  497.31  4996.1  495.31
  5003.9  495.31  5004.9  497.31  5014.8  501.84  5044.8  503.38  5059.8  504.55
  5064.8   505.3  5074.8  508.58  5079.8  509.32  5089.8  510.35  5104.8   512.4
  5109.8  513.26  5124.8  516.23
#Mann= 3 , 1 , 0
  4831.8     .15       0  4995.1    .045       0  5004.9     .15       0
Bank Sta=4995.1,5004.9
XS Rating Curve= 0
Exp/Cntr=0.3,0.1

Type RM Length L Ch R = 1 ,532.5   ,365.5,365.5,365.5
BEGIN DESCRIPTION:
Reedy Branch 2.0
END DESCRIPTION:
XS GIS Cut Line= 3
      1881506.68       780163.87      1881590.88       780145.62
      1881764.59       780124.04
#Sta/Elev= 30
  4917.6  515.77  4932.6  511.61  4937.6  510.38  4942.6  509.57  4947.6  508.54
  4962.6  504.67  4972.6  502.91  4977.6  502.35  4982.6  501.24  4987.6  498.87
  4995.2  494.09  4996.2  492.09  5003.9  492.09  5004.9  494.09  5013.8  499.55
  5018.8  500.74  5023.8  500.29  5028.8  499.52  5033.8  499.34  5038.8  499.38
  5093.8  500.64  5108.8  501.88  5113.8  502.63  5123.8  504.52  5128.8  505.65
  5143.8  510.23  5148.8  511.25  5153.8  511.72  5163.8  513.11  5178.8   515.6
#Mann= 3 , 1 , 0
  4917.6     .15       0  4995.2    .045       0  5004.9     .15       0
Bank Sta=4995.2,5004.9
XS Rating Curve= 0
Exp/Cntr=0.3,0.1

Type RM Length L Ch R = 1 ,167.0   ,0,0,0
BEGIN DESCRIPTION:
Reedy Branch 1.0
END DESCRIPTION:
XS GIS Cut Line= 5
      1881537.08       780470.82      1881575.63       780481.73
      1881633.69       780480.74      1881726.42       780481.73
      1881830.97       780396.43
#Sta/Elev= 27
  4906.8  510.01  4921.8  508.33  4941.8  505.58  4946.8  504.57  4951.8  503.49
  4961.8  502.53  4971.8  501.02  4976.8  500.52  4981.8  498.83  4995.1  493.63
  4996.1  491.63  5003.8  491.63  5004.8  493.63  5004.9  495.04  5009.9  496.48
  5014.9  497.79  5019.9  498.18  5074.9  499.78  5084.9  499.76  5097.6  500.04
  5152.6   503.4  5157.6  503.84  5167.6  505.24  5187.6  506.63  5192.6  507.21
  5212.6  510.75  5232.6  514.82
#Mann= 3 , 1 , 0
  4906.8     .15       0  4995.1    .045       0  5004.8     .15       0
Bank Sta=4995.1,5004.8
XS Rating Curve= 0
Exp/Cntr=0.3,0.1

Chan Stop Cuts=-1